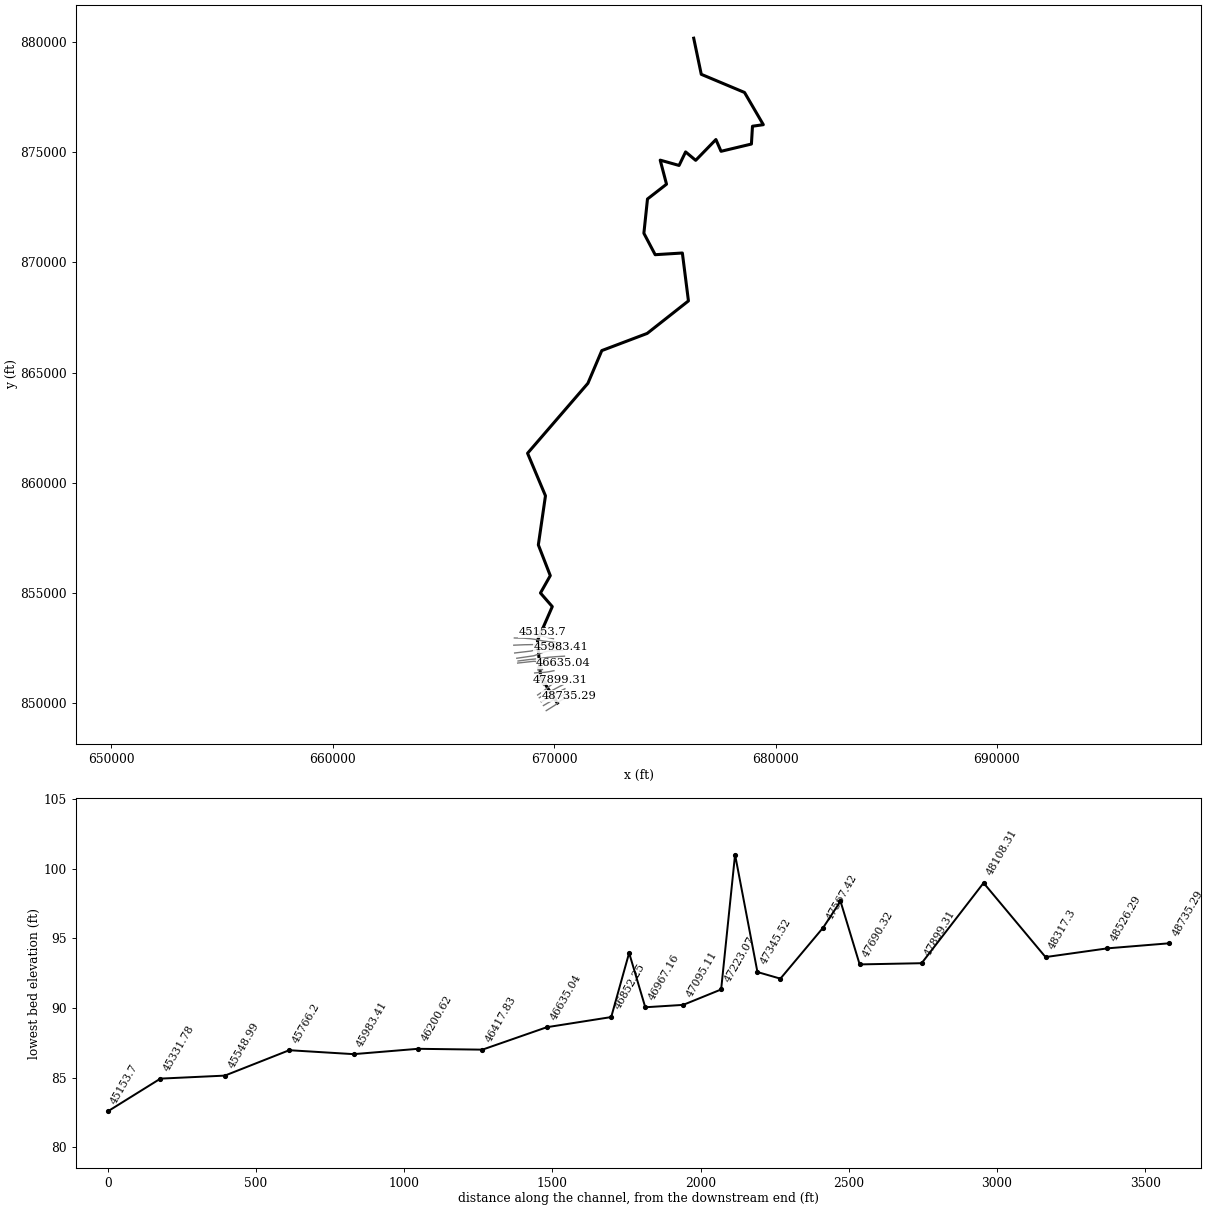
--- 13716_ras.prj (project) ---

Proj Title=13716
Current Plan=p01
Default Exp/Contr=0.3,0.1
English Units
Geom File=g01
Flow File=f01
Plan File=p01
Y Axis Title=Elevation
X Axis Title(PF)=Main Channel Distance
X Axis Title(XS)=Station
BEGIN DESCRIPTION:
RFD model 13716 exported to HEC-RAS
END DESCRIPTION:

--- 13716_ras.p01 (plan) ---

Plan Title=Plan 01
Program Version=4.10
Short Identifier=Plan 01
Geom File=g01
Flow File=f01
Subcritical Flow
Calc Critical at every XS
Secant Critical Depth

--- 13716_ras.f01 (steady flow) ---

Flow Title=Flow 01
Program Version=5.01
Number of Profiles= 6
Profile Names=10yr,25yr,50yr,100yr,100plus,500yr
River Rch & RM=13716,139,48735.29
 6070.83 9922.0413624.3817019.6224848.65 26343.9
River Rch & RM=13716,139,48526.29
  6082.8 9943.0813654.62 17058.924905.9926401.21
River Rch & RM=13716,139, 48317.3
 6085.26 9947.4113660.8517067.0124917.8326413.09
River Rch & RM=13716,139,48108.31
 6087.43 9951.2313666.3617074.1724928.2926423.57
River Rch & RM=13716,139,47899.31
 6103.28 9979.1213706.4617126.2725004.3626499.65
River Rch & RM=13716,139,47690.32
  6111.1  9992.913726.2917152.0525041.9926537.31
River Rch & RM=13716,139,47625.68
 6111.97 9994.44 13728.517154.9225046.1826541.49
River Rch & RM=13716,139,47567.42
 6112.84 9995.9613730.6917157.7725050.3426545.68
River Rch & RM=13716,139,47422.97
 6113.57 9997.2413732.5317160.1625053.8326549.16
River Rch & RM=13716,139,47270.02
  6115.310000.2913736.9317165.8825062.1826557.53
River Rch & RM=13716,139,47095.11
 6118.3510005.6713744.6617175.9125076.8426572.16
River Rch & RM=13716,139,46967.16
 6120.3810009.24 13749.8 17182.625086.5926581.92
River Rch & RM=13716,139,46635.04
12195.48 20310.328250.9535671.8452080.8950902.57
River Rch & RM=13716,139,46417.83
12210.8820337.2628289.6835722.1152154.2950968.42
River Rch & RM=13716,139,46200.62
12212.5120340.13 28293.835727.4652162.0950975.43
River Rch & RM=13716,139,45983.41
12214.5220343.6428298.8735734.0452171.6950984.06
River Rch & RM=13716,139, 45766.2
12219.9520353.1528312.5235751.7552197.5551007.26
River Rch & RM=13716,139,45548.99
12230.4520371.53 28338.935785.9752247.5251052.03
River Rch & RM=13716,139,45331.78
12232.8620375.7428344.9535793.8152258.9751062.27
River Rch & RM=13716,139, 45153.7
 12235.420380.1828351.3235802.0752271.0251073.05
River Rch & RM=13716,139,45006.78
12253.8420412.4528397.6735862.2152358.8251151.74
River Rch & RM=13716,139,44759.99
12257.6420419.1128407.2235874.5852376.8951167.91
River Rch & RM=13716,139, 44513.2
12267.0620435.5528430.8135905.1552421.5251207.77
River Rch & RM=13716,139,44266.41
12269.2320439.3328436.2335912.1752431.7751216.92
River Rch & RM=13716,139,44019.62
12290.2520475.9528488.6835980.0652530.8951305.21
River Rch & RM=13716,139,43772.83
12664.5121119.3229402.6537154.4354245.4752801.97
River Rch & RM=13716,139,43526.04
12666.4121122.6529407.41 37160.654254.4752809.95
River Rch & RM=13716,139,43032.46
12669.08 21127.329414.0837169.2354267.0752821.13
River Rch & RM=13716,139,42538.89
12765.2421295.0829654.62 37480.854721.9853224.88
River Rch & RM=13716,139, 42292.1
12767.2921298.6529659.7237487.39 54731.653233.37
River Rch & RM=13716,139, 42046.5
12777.9221317.1229686.1437521.5554781.4653277.39
River Rch & RM=13716,139, 41800.9
12784.0521327.7929701.4137541.2954810.2953302.84
River Rch & RM=13716,139, 41555.3
12800.4221356.1829741.9737593.6854886.7753370.15
River Rch & RM=13716,139, 41309.7
12804.9121363.9929753.1337608.0954907.81 53388.7
River Rch & RM=13716,139, 40818.5
12817.17 21385.329783.6437647.54 54965.453439.55
River Rch & RM=13716,139, 40572.9
12819.3621389.1129789.0737654.5554975.6453448.56
River Rch & RM=13716,139, 40327.3
13065.8321816.7630400.1238443.7256127.83 54461.1
River Rch & RM=13716,139, 40081.7
13100.8821877.4730486.7838555.55 56291.154604.02
River Rch & RM=13716,139, 39836.1
13110.42   2189430510.3738585.9856335.5354642.87
River Rch & RM=13716,139, 39590.5
13140.9421946.7330585.5338682.8356476.94 54766.2
River Rch & RM=13716,139, 39344.9
13141.9721948.5230588.0838686.1256481.7354770.39
River Rch & RM=13716,139,39251.54
13143.7821951.6430592.5438691.8756490.1354777.73
River Rch & RM=13716,139,39176.43
13144.8121953.4330595.0938695.1656494.9354781.93
River Rch & RM=13716,139,38928.47
13161.8821982.8830637.05 38749.256573.8454850.63
River Rch & RM=13716,139,38680.51
13163.97 21986.530642.1938755.82 56583.554859.01
River Rch & RM=13716,139,38432.56
13173.9522003.6830666.6338787.26 56629.454898.85
River Rch & RM=13716,139, 38184.6
13177.7622010.2430675.9638799.2556646.9154914.04
River Rch & RM=13716,139,37936.64
13198.3322045.6230726.2438863.8956741.2854995.77
River Rch & RM=13716,139,37688.69
13204.9322056.9830742.3738884.6256771.5455021.95
River Rch & RM=13716,139,37440.73
13216.9222077.6630771.8338922.5456826.9155070.11
River Rch & RM=13716,139,37192.78
13219.6822082.4130778.5938931.2456839.61 55081.1
River Rch & RM=13716,139,36944.82
13231.2122102.21 30806.738967.3456892.3255126.62
River Rch & RM=13716,139,36448.91
13335.4122282.03 31062.839297.1457373.8355545.09
River Rch & RM=13716,139,36200.95
13343.6822296.2731083.0539323.1657411.8255577.95
River Rch & RM=13716,139,35952.99
13350.6522308.2631100.0939345.07 57443.855605.59
River Rch & RM=13716,139,35705.04
13405.3722402.4131233.9439517.1757695.0755822.86
River Rch & RM=13716,139,35457.08
13410.67 22411.531246.8439533.7357719.2555843.68
River Rch & RM=13716,139,35209.13
13425.5322436.9931283.0139580.1457787.0155901.97
River Rch & RM=13716,139,34961.17
13427.7922440.87 31288.5 39587.257797.3155910.82
River Rch & RM=13716,139,34713.21
13441.5722464.5231322.0639630.2657860.1855964.92
River Rch & RM=13716,139,34465.26
13451.7122481.8731346.66 39661.857906.2356004.44
River Rch & RM=13716,139, 34217.3
13452.5122483.24 31348.6 39664.357909.8856007.56
River Rch & RM=13716,139,33969.34
13455.9822489.1831357.0239675.0957925.6356021.08
River Rch & RM=13716,139,33721.39
13485.7322540.1231429.2139767.6358060.7556136.97
River Rch & RM=13716,139,33473.43
 13488.822545.3731436.6539777.1858074.6856148.92
River Rch & RM=13716,139,33225.48
13500.7322565.8331465.6839814.4358129.0756195.66
River Rch & RM=13716,139,32977.52
13504.4522572.2131474.7239826.0358146.01 56210.2
River Rch & RM=13716,139,32729.56
13512.56 22586.131494.42 39851.358182.8956241.87
River Rch & RM=13716,139,32481.61
13525.5122608.2631525.8139891.5458241.6556292.21
River Rch & RM=13716,139,32233.65
13534.3422623.4331547.3639919.2158282.0456326.98
River Rch & RM=13716,139,31985.69
13538.8422631.1531558.3139933.2758302.5756344.62
River Rch & RM=13716,139,31737.74
 13541.122635.03 31563.839940.3158312.8556353.43
River Rch & RM=13716,139,31241.83
13573.2122690.13   31642 40040.758459.4256479.42
River Rch & RM=13716,139,30745.91
13607.6222749.6431726.8940150.1658619.2356618.25
River Rch & RM=13716,139,30424.63
 13609.322752.5531731.0340155.4858627.0156624.97
River Rch & RM=13716,139,30264.91
13609.9522753.6631732.6240157.53   5863056627.56
River Rch & RM=13716,139,30032.11
13613.9622760.5931742.4840170.2258648.5356643.61
River Rch & RM=13716,139, 29799.3
13618.2322767.9631752.9840183.7458668.27 56660.7
River Rch & RM=13716,139,29566.49
 13621.822774.13 31761.840195.14 58684.956675.19
River Rch & RM=13716,139,29100.88
13638.3622802.9731803.0940248.56 58762.956743.48
River Rch & RM=13716,139,28868.08
13640.2422806.2531807.7840254.6358771.7656751.24
River Rch & RM=13716,139,28635.27
13640.8722807.3431809.3440256.6658774.7256753.83
River Rch & RM=13716,139,28402.46
13664.6122848.3331867.75 40331.958884.5756848.98
River Rch & RM=13716,139,28169.66
13676.1222868.3831896.4840369.0858938.8656896.52
River Rch & RM=13716,139,27936.85
13680.9922876.8731908.6440384.8258961.8456916.68
River Rch & RM=13716,139,27704.05
13693.4922898.59 31939.740424.9659020.4556967.82
River Rch & RM=13716,139,26966.68
13706.7622921.6331972.6540467.5459082.6157022.04
River Rch & RM=13716,139,26285.09
13714.3822934.9131991.6740492.1659118.5657053.53
River Rch & RM=13716,139,25590.32
13724.1922952.0432016.24   4052459165.04 57094.3
River Rch & RM=13716,139,24846.39
13734.7622970.4832042.6840558.2559215.0457138.16
River Rch & RM=13716,139,24598.41
13757.5223009.9332099.0240630.9759321.2157230.48
River Rch & RM=13716,139,24350.44
13773.2923037.2532138.0340681.3359394.7557294.39
River Rch & RM=13716,139,24102.46
13776.9323043.58 32147.140693.0559411.8657309.34
River Rch & RM=13716,139,23606.51
   1378823062.8332174.6440728.6659463.8457354.68
River Rch & RM=13716,139,23110.55
13796.6323077.8632196.15 40756.559504.4857390.21
River Rch & RM=13716,139,22862.58
13797.7523079.8132198.9540760.1259509.7857394.85
River Rch & RM=13716,139, 22614.6
 13801.623086.5232208.58 40772.659527.9957410.82
River Rch & RM=13716,139,22366.63
13808.0423097.7732224.71 40793.559558.5257437.59
River Rch & RM=13716,139,21870.67
13811.6423104.0532233.7240805.1759575.5557452.52
River Rch & RM=13716,139,21126.74
13861.87 23191.732359.4140968.01 59813.357660.86
River Rch & RM=13716,139,19937.49
13913.3223281.7332488.7241135.7860058.2457876.09
River Rch & RM=13716,139,19464.29
13921.3623295.8232508.9941162.1160096.6957909.96
River Rch & RM=13716,139,19185.71
13921.9723296.8932510.5341164.1160099.5957912.52
River Rch & RM=13716,139,18953.92
13924.7723301.7932517.5941173.29   6011357924.33
River Rch & RM=13716,139,18722.13
 13987.423411.7232675.7841378.8460413.1158188.86
River Rch & RM=13716,139,18490.34
13990.7923417.6732684.3441389.9860429.38 58203.2
River Rch & RM=13716,139,18258.55
13992.8123421.24 32689.5 41396.760439.1858211.91
River Rch & RM=13716,139,18026.76
 13997.223428.99 32700.7 41411.360460.5158230.86
River Rch & RM=13716,139,17794.96
14000.7523435.2732709.7841423.15 60477.858246.22
River Rch & RM=13716,139,17563.17
14002.0623437.5832713.1141427.4860484.1358251.85
River Rch & RM=13716,139,17331.38
14002.8923439.0432715.2341430.2560488.1758255.43
River Rch & RM=13716,139,17068.72
14033.3923492.9132793.0441531.7160636.2958386.96
River Rch & RM=13716,139,16797.06
 14039.423503.5532808.43 41551.860665.6358413.04
River Rch & RM=13716,139,16519.49
15331.6925796.8536131.3445895.7467007.7964035.84
River Rch & RM=13716,139,   15916
15338.5825809.1236149.1545919.0767041.8464065.93
River Rch & RM=13716,139, 14921.8
15347.9125825.74 36173.345950.7367088.0764106.87
River Rch & RM=13716,139,13993.43
15392.62 25905.836289.9646103.9667311.7964305.95
River Rch & RM=13716,139,13463.89
 15400.425919.6536310.07 46130.367350.2464339.93
River Rch & RM=13716,139, 12530.5
15416.6825948.7336352.3946185.8167431.29 64411.8
River Rch & RM=13716,139,11782.57
15432.0525976.0836392.0746237.7667507.1364478.72
River Rch & RM=13716,139,11230.54
15436.11 25983.336402.5546251.4967527.1764496.44
River Rch & RM=13716,139,10785.32
15469.08 26041.936487.5546362.7267689.5864639.52
River Rch & RM=13716,139,10536.01
 15486.726073.0636532.6246421.5467775.45 64714.7
River Rch & RM=13716,139, 9289.45
15513.8826120.9936601.8346511.7567907.1664829.62
River Rch & RM=13716,139,9040.139
15514.4626122.0136603.3146513.6767909.9664832.08
River Rch & RM=13716,139,8790.827
15515.8426124.4636606.8546518.2967916.7164837.96
River Rch & RM=13716,139,8454.191
15517.4626127.3236610.9846523.6867924.5764844.84
River Rch & RM=13716,139,8309.827
15521.2526133.9636620.54 46536.167942.7164860.54
River Rch & RM=13716,139, 8066.22
15522.1926135.6236622.92 46539.267947.2464864.47
River Rch & RM=13716,139,7335.398
15647.37 26355.336939.1946950.3368547.4865384.42
River Rch & RM=13716,139,6604.576
15650.6926361.1236947.55 46961.268563.3565398.12
River Rch & RM=13716,139,5119.691
15661.8526380.6736975.66 46997.768616.64 65444.1
Boundary for River Rch & Prof#=13716,139,1
Up Type= 0
Dn Type= 2
Boundary for River Rch & Prof#=13716,139,2
Up Type= 0
Dn Type= 2
Boundary for River Rch & Prof#=13716,139,2
Up Type= 0
Dn Type= 2
Boundary for River Rch & Prof#=13716,139,2
Up Type= 0
Dn Type= 2
Boundary for River Rch & Prof#=13716,139,2
Up Type= 0
Dn Type= 2
Boundary for River Rch & Prof#=13716,139,2
Up Type= 0
Dn Type= 2

--- 13716_ras.g01 (geometry) ---

Geom Title=13716
Program Version=4.10

River Reach=13716,139
Reach XY= 30
670147.809288313 850013.69061173669392.291804153851194.902934666
669249.087434531852852.983131998669918.691356005 854390.95553552
669384.854061575 855007.41263076669828.273578107855795.224126256
669288.872381352857189.574998767669610.794284188859416.284663802
668802.558665017861346.580289758671526.795265506864518.231421097
672154.636308138866003.049783931674203.408719166866781.841400394
676066.888260713868256.570457663675792.534951176870429.283134324
674564.765525622870352.541072232674054.779872598871324.924376069
674217.789614126872879.066304549675077.189295181873550.137260826
674791.516549756874641.433620363675643.887614225874400.622758239
675938.950369927875014.691256389676394.644394127874632.656204112
677307.575385838875576.112233743677539.346219167875042.258067074
678910.963677071875371.898680873678959.092458805876179.761384522
679448.200385838876249.289317055678599.355016263877711.259154569
676646.230016257878534.175821229676305.084182884 880172.19665456

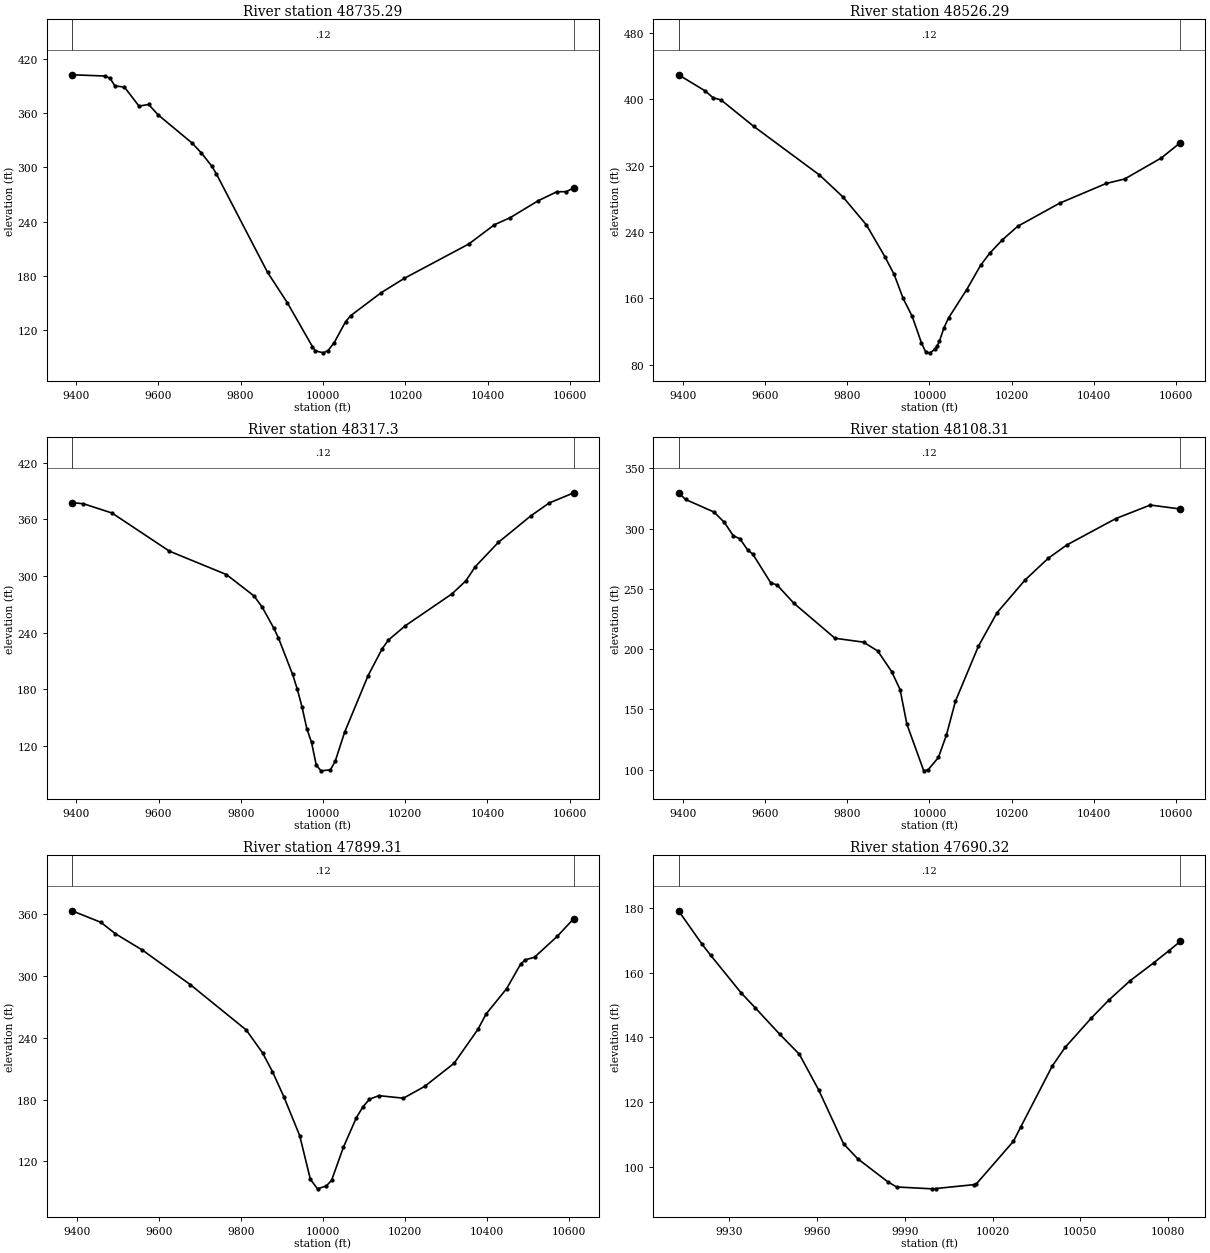
Type RM Length L Ch R = 1 ,48735.29,208.994500,208.994500,208.994500
XS GIS Cut Line= 6
669645.565832642849671.884746585670031.012230316849913.148746437
 670113.03076225849977.673931263670185.043416823850053.783964165
670265.983501894850112.322073569670661.611457744850335.457808772
#Sta/Elev= 30
9390.744402.51039471.491401.12989483.121398.4691 9494.75390.23289518.013388.8386
9553.222367.84499576.694369.60919600.167357.96499682.486326.7861 9704.32316.1824
 9730.07301.35129741.246292.67149865.441183.75879913.317150.24229974.503 101.432
 9981.1496.9165310000.89 94.6395 10012.497.20548 10027.4106.041510054.91129.1626
10067.55135.907110141.88161.402410197.77177.186110354.34215.207310416.27236.4708
10454.89244.344310521.74262.821910567.95273.003410590.51273.069310609.24  277.32
#Mann= 3 , 0 , 0
9390.744    0.12       09390.744    0.12       010609.24    0.12       0
#XS Ineff= 2 , 0
       0                               0
Bank Sta=9390.744,10609.24
Exp/Cntr=0.3,0.1

Type RM Length L Ch R = 1 ,48526.29,208.994400,208.994400,208.994400
XS GIS Cut Line= 6
669518.549731506849902.648541121669766.721823609850047.993283139
669901.127347429850122.828411541669980.390966113850163.107998021
670179.905076058850257.844075078670595.559479198850475.962329309
#Sta/Elev= 30
 9389.68429.45749453.696410.27339473.484401.87949493.271399.04299572.421 367.347
9732.539308.66169789.767282.12829846.678248.51769891.546 210.271 9913.98188.9499
9936.151159.79499958.224138.10719980.297106.71549991.33394.74171   1000194.27559
10013.3898.52538 10019.2103.0907 10024.4108.446310035.42124.548710046.45136.2237
10090.82170.609710124.28199.602210146.67 214.36610177.47230.496410214.62246.7671
10316.54274.622410429.78298.405810474.81303.826310564.42329.288110610.32347.6217
#Mann= 3 , 0 , 0
 9389.68    0.12       0 9389.68    0.12       010610.32    0.12       0
#XS Ineff= 2 , 0
       0                               0
Bank Sta=9389.68,10610.32
Exp/Cntr=0.3,0.1

Type RM Length L Ch R = 1 , 48317.3,208.994400,208.994400,208.994400
XS GIS Cut Line= 6
669421.104794558 850071.73134377669687.854468989850229.190099433
669948.265200275850377.716716986670025.552377557850421.588039045
670301.345986159  850568.1053081670488.943724094850663.301503411
#Sta/Elev= 30
9389.454377.84589417.202376.63129486.875366.77799626.222326.43639764.997301.6363
9832.043279.05089852.227267.05199880.119245.00569891.631234.50269926.168195.7436
 9937.68179.98859949.192161.04389960.704138.30999972.217123.72769983.72999.64427
9995.24193.6486510018.2494.7084710029.74103.748210052.74134.603210109.89 194.613
10143.86222.822110159.09232.180710200.48 247.42610313.72281.108610347.69 294.876
10370.33309.851110426.69335.681610505.19363.598610550.05377.353510610.54388.2747
#Mann= 3 , 0 , 0
9389.454    0.12       09389.454    0.12       010610.54    0.12       0
#XS Ineff= 2 , 0
       0                               0
Bank Sta=9389.454,10610.54
Exp/Cntr=0.3,0.1

Type RM Length L Ch R = 1 ,48108.31,208.994500,208.994500,208.994500
XS GIS Cut Line= 6
669331.884597233850255.873688486669639.200694485 850448.16807975
669742.781848293850508.786917794669973.006400036850621.464979314
670247.921984588850768.780644848 670400.08367942 850846.00830371
#Sta/Elev= 30
9389.285329.6521 9406.49 324.0989475.534313.68839500.752305.1371 9522.72293.8724
9538.457291.61119557.309  282.319569.905278.82719613.866254.90549628.886253.2133
9670.423237.89319770.111208.9622 9839.63205.7243 9874.32198.34759908.138181.2618
9928.613 166.3229945.062137.73679986.18698.967249997.227100.0211 10021.8 110.037
10041.28128.568810063.43156.855310119.25202.357110164.48230.101510232.55257.2098
10289.28275.351910334.66286.401410453.83308.268910537.74319.489510610.72316.1803
#Mann= 3 , 0 , 0
9389.285    0.12       09389.285    0.12       010610.72    0.12       0
#XS Ineff= 2 , 0
       0                               0
Bank Sta=9389.285,10610.72
Exp/Cntr=0.3,0.1

Type RM Length L Ch R = 1 ,47899.31,208.994400,208.994400,208.994400
XS GIS Cut Line= 6
669256.190760134850381.010000771 669519.04531515850559.577386912
669830.954008648850810.509193473669945.589913888850895.518952089
670107.895660172850996.522775328670260.989854063851074.887142046
#Sta/Elev= 30
9387.917363.47369458.048352.26439493.823341.10989559.504325.26589676.281291.7227
  9812.7247.6685 9852.52225.44819876.801207.12569904.389182.89869943.291144.8479
9969.226102.51319986.75693.20965 10008.196.02617   10021101.438310049.93 133.701
10081.57162.4336 10097.4172.850810113.51180.324910136.37 183.78910196.29181.3189
10247.95192.734110320.05215.305710378.38 248.43510397.95263.147410448.12 287.826
10482.12311.581710493.46315.766610516.13318.344710572.05338.843310612.08  355.95
#Mann= 3 , 0 , 0
9387.917    0.12       09387.917    0.12       010612.08    0.12       0
#XS Ineff= 2 , 0
       0                               0
Bank Sta=9387.917,10612.08
Exp/Cntr=0.3,0.1

Type RM Length L Ch R = 1 ,47690.32,64.633300,64.633300,64.633300
XS GIS Cut Line= 2
669537.734321356850818.979493544669651.015571326850947.885743558
#Sta/Elev= 26
9912.594179.14989920.609168.84169923.601 165.3629933.921153.83229938.749149.2028
9947.234140.91849953.898134.77889960.547123.66129969.047 107.0429973.859  102.44
9984.19695.276799987.172 93.70399999.34593.1232710000.4893.21022 10013.8 94.4335
10014.4994.6927610027.11107.823210029.64112.286910040.42131.145610044.79136.8662
10053.74145.940310059.94151.691210067.05157.512610075.09163.045110080.36166.8341
 10084.2169.6876
#Mann= 3 , 0 , 0
9912.594    0.12       09912.594    0.12       0 10084.2    0.12       0
#XS Ineff= 2 , 0
       0                               0
Bank Sta=9912.594,10084.2
Exp/Cntr=0.3,0.1

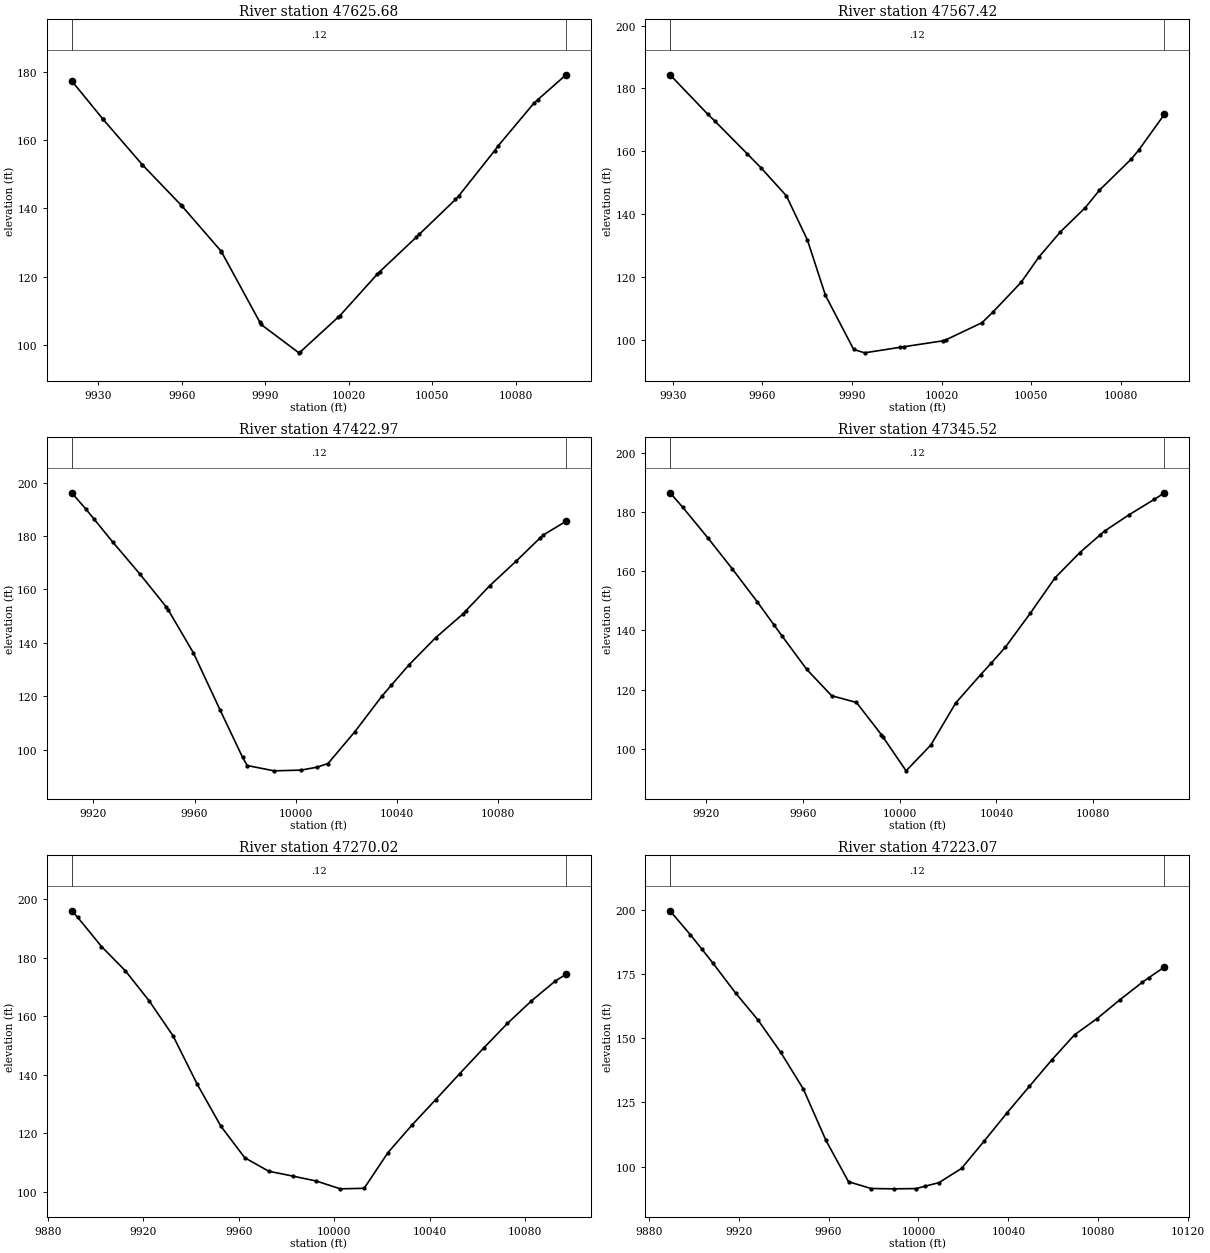
Type RM Length L Ch R = 1 ,47625.68,58.267200,58.267200,58.267200
XS GIS Cut Line= 2
669486.953071356850867.156576887669613.255154669850992.156576887
#Sta/Elev= 26
9920.413177.32459931.563166.19389931.734166.02879945.779152.77569945.804152.7526
9959.873140.81399959.995140.70389973.942127.60029974.211127.31339988.012106.6768
9988.427105.997310002.0897.6557910002.6497.9648810016.15108.062610016.86108.5815
10030.22  120.6810031.07121.378710044.29131.541710045.29  132.3310058.36142.5771
10059.51143.598710072.43156.874810073.72158.2995 10086.5170.732910087.94171.8061
10098.11179.1003
#Mann= 3 , 0 , 0
9920.413    0.12       09920.413    0.12       010098.11    0.12       0
#XS Ineff= 2 , 0
       0                               0
Bank Sta=9920.413,10098.11
Exp/Cntr=0.3,0.1

Type RM Length L Ch R = 1 ,47567.42,144.451100,144.451100,144.451100
XS GIS Cut Line= 2
669445.286404669 850915.33366023669571.588487983851022.104493544
#Sta/Elev= 24
9929.113 184.3259941.833 171.6799944.086169.61629954.927 159.1699959.576154.6695
9968.021145.80039975.066131.74549981.116114.06879990.55596.84844 9994.2195.76708
10006.05 97.5277 10007.397.70141 10020.499.5939110021.5399.9643810033.49105.3713
10037.02108.632610046.59118.246410052.51126.262710059.68134.2607   10068141.9661
10072.78147.568910083.49157.553610085.87160.2862 10094.5171.7197
#Mann= 3 , 0 , 0
9929.113    0.12       09929.113    0.12       0 10094.5    0.12       0
#XS Ineff= 2 , 0
       0                               0
Bank Sta=9929.113,10094.5
Exp/Cntr=0.3,0.1

Type RM Length L Ch R = 1 ,47422.97,77.449000,77.449000,77.449000
XS GIS Cut Line= 2
669339.817654639851052.052410215669523.411404669 851118.45866023
#Sta/Elev= 27
9911.502196.18989917.013190.18769920.168186.54749927.647177.82029938.281165.9483
9948.915153.38339949.568152.44049959.549136.29169970.183114.72659978.96897.18172
9980.81794.085269991.45192.1013410002.0992.3759110008.3793.4603810012.7294.84862
10023.35106.775910033.99120.046310037.77124.200910044.62131.703410055.26141.9619
10065.89150.727810067.17152.036510076.52161.328510087.16170.726710096.57179.3623
10097.79180.411410106.74185.5398
#Mann= 3 , 0 , 0
9911.502    0.12       09911.502    0.12       010106.74    0.12       0
#XS Ineff= 2 , 0
       0                               0
Bank Sta=9911.502,10106.74
Exp/Cntr=0.3,0.1

Type RM Length L Ch R = 1 ,47345.52,75.497500,75.497500,75.497500
XS GIS Cut Line= 2
669309.869738013851135.385743544669509.088488013 851180.95866023
#Sta/Elev= 26
9905.049186.41949910.312181.5303 9920.57171.31769930.829160.70299941.087149.6509
9948.163141.68529951.345138.10329961.604126.78099971.862117.9317 9982.12115.6456
9992.379104.83469993.007104.092110002.6492.57605 10012.9101.332810023.15115.4813
10033.41124.977610037.85128.936410043.67 134.30410053.93145.710510064.19 157.709
10074.45166.226210082.69172.0876 10084.7173.512310094.96179.067410105.22 184.187
10109.41186.3646
#Mann= 3 , 0 , 0
9905.049    0.12       09905.049    0.12       010109.41    0.12       0
#XS Ineff= 2 , 0
       0                               0
Bank Sta=9905.049,10109.41
Exp/Cntr=0.3,0.1

Type RM Length L Ch R = 1 ,47270.02,46.947000,46.947000,46.947000
XS GIS Cut Line= 2
669282.525987983851233.041993558669489.557237983 851227.83366023
#Sta/Elev= 23
9890.009 196.0539892.483193.86059902.487183.8373 9912.49175.54289922.493165.2189
9932.496153.26059942.499 136.9079952.502122.40959962.506111.62879972.509107.0292
9982.512105.36889992.515103.659810002.52100.997310012.52101.178710022.52 113.411
10032.53122.783110042.53131.532310052.53140.353610062.54149.074810072.54157.5617
10082.54165.197210092.55172.018710097.11174.3501
#Mann= 3 , 0 , 0
9890.009    0.12       09890.009    0.12       010097.11    0.12       0
#XS Ineff= 2 , 0
       0                               0
Bank Sta=9890.009,10097.11
Exp/Cntr=0.3,0.1

Type RM Length L Ch R = 1 ,47223.07,127.958000,127.958000,127.958000
XS GIS Cut Line= 2
669276.015571326851286.427410215669494.765571326851264.291993558
#Sta/Elev= 26
9889.508199.56579898.538190.26549903.686184.63699908.589179.1934 9918.64167.5991
9928.691156.98999938.742 144.4719948.793130.19979958.844110.21989968.89594.09207
9978.94791.452729988.99891.326689999.04991.4257610003.0192.38234 10009.193.73218
10019.1599.27082 10029.2109.891510039.25  120.76 10049.3131.193510059.36141.5747
10069.41151.289610079.46  157.6210089.51164.871610099.56171.734910102.34173.4337
10109.37177.6827
#Mann= 3 , 0 , 0
9889.508    0.12       09889.508    0.12       010109.37    0.12       0
#XS Ineff= 2 , 0
       0                               0
Bank Sta=9889.508,10109.37
Exp/Cntr=0.3,0.1

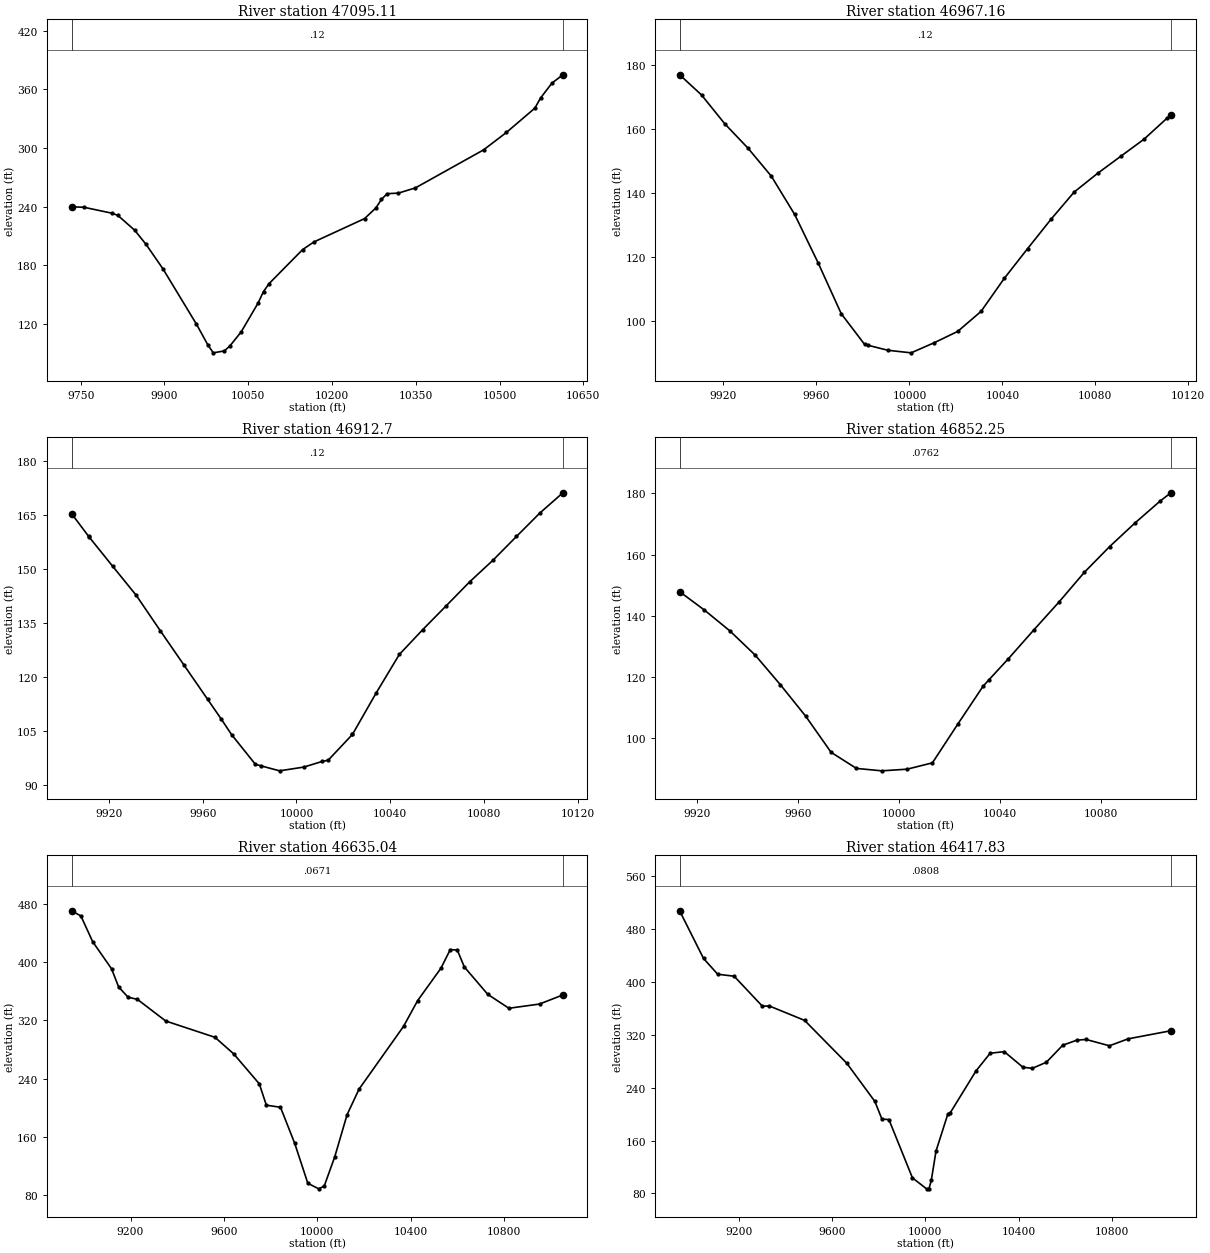
Type RM Length L Ch R = 1 ,47095.11,127.958100,127.958100,127.958100
XS GIS Cut Line= 6
669122.760182573851379.673272646 669308.91319773851402.313685007
669467.218028786851401.951946657669591.989095462851411.842507672
669783.112699358851440.568120977669994.271364521851482.909275724
#Sta/Elev= 30
9733.614239.74279756.112239.17499806.644233.05729816.721230.81229846.953215.5448
9867.102 201.1519897.208176.24259957.304119.5339 9977.3198.712239987.31390.22092
10007.3292.1994410017.3297.3956610037.32111.655610067.32140.870710077.32152.9812
10087.33161.118710147.46 195.94310167.56203.726610258.21227.600410278.39238.4555
10288.48247.200410298.56253.111410318.84253.712810349.25259.037710471.34297.9572
10512.13315.750310563.13340.650310573.33350.986810593.73366.302210613.38 374.826
#Mann= 3 , 0 , 0
9733.614    0.12       09733.614    0.12       010613.38    0.12       0
#XS Ineff= 2 , 0
       09770.366                       0
Bank Sta=9733.614,10613.38
Exp/Cntr=0.3,0.1

Type RM Length L Ch R = 1 ,46967.16,54.453600,54.453600,54.453600
XS GIS Cut Line= 2
669265.598904669851519.500326887669476.536404669851533.823243544
#Sta/Elev= 24
9901.123177.08699910.545170.77569920.568161.73799930.591154.08349940.614145.3201
9950.637133.3548 9960.66118.32439970.683102.28779980.70692.705799982.30492.39871
9990.72990.8536710000.7590.0494210010.7893.24378 10020.896.7609310030.82103.0109
10040.84113.368910050.87 122.67610060.89131.822310070.91 140.38410080.94146.2059
10090.96151.576510100.98156.931310111.01163.603810112.55164.3468
#Mann= 3 , 0 , 0
9901.123    0.12       09901.123    0.12       010112.55    0.12       0
#XS Ineff= 2 , 0
       0                               0
Bank Sta=9901.123,10112.55
Exp/Cntr=0.3,0.1

Type RM Length L Ch R = 1 , 46912.7,60.448500,60.448500,60.448500
XS GIS Cut Line= 4
669257.786404639851596.323243544669337.213488013851582.000326887
669374.973904639851571.583660215669464.817654639851570.281576902
#Sta/Elev= 27
9903.981165.41639911.311159.05139911.437158.94719921.472150.83489931.633 142.672
9941.795132.93149951.956123.34989962.117113.76829967.786108.42269972.278104.0189
 9982.4495.768149984.68995.366089992.76693.9480910003.1494.9941710011.0196.57374
10013.51 96.890810023.86104.051210023.89104.071610033.89115.449810043.89126.2739
10053.89133.179610063.89139.791410073.89146.437410083.89152.476810093.89159.0582
10103.89165.579110113.71171.1945
#Mann= 3 , 0 , 0
9903.981    0.12       09903.981    0.12       010113.71    0.12       0
#XS Ineff= 2 , 0
       0                               0
Bank Sta=9903.981,10113.71
Exp/Cntr=0.3,0.1

Type RM Length L Ch R = 1 ,46852.25,217.210700,217.210700,217.210700
XS GIS Cut Line= 2
669255.182237983851643.198243544669449.192654639 851630.17741023
#Sta/Elev= 22
9913.144147.91789922.984141.87649933.007135.10659943.029127.19229953.052117.4652
9963.074107.16339973.09795.397519983.11990.141469993.14289.3462810003.1689.88626
10013.1991.9618310023.21104.591210033.23116.992310035.57119.111310043.25125.9888
10053.28135.3641 10063.3 144.53610073.32154.237910083.34162.660610093.37170.3657
10103.39177.581910107.59180.2277
#Mann= 3 , 0 , 0
9913.144  0.0762       09913.144  0.0762       010107.59  0.0762       0
#XS Ineff= 2 , 0
       0                               0
Bank Sta=9913.144,10107.59
Exp/Cntr=0.3,0.1

Type RM Length L Ch R = 1 ,46635.04,217.210600,217.210600,217.210600
XS GIS Cut Line= 6
668355.360577487851830.132495701669087.957275242851910.584905054
669273.756855665851891.849993241669475.045068164851794.620885354
669648.678390014851762.414753611670424.473692128851819.119686499
#Sta/Elev= 30
8947.292470.54718987.366 463.4059037.913428.0397 9118.79390.85579149.116365.8167
9189.439351.88889229.761348.81849350.728319.14969561.748296.7634 9641.85274.0874
9751.901232.82089781.982203.52329842.628200.65679903.471 151.1559959.70296.26597
10006.62 88.618710030.0692.5014310074.95132.428410127.91190.407810179.12225.4969
   10370311.830110430.01347.022910530.11391.644410570.18417.296310600.28416.5472
10630.42393.334510730.88355.733310821.44336.634310952.46 342.42811052.72354.9733
#Mann= 3 , 0 , 0
8947.292  0.0671       08947.292  0.0671       011052.72  0.0671       0
#XS Ineff= 2 , 0
       0                               0
Bank Sta=8947.292,11052.72
Exp/Cntr=0.3,0.1

Type RM Length L Ch R = 1 ,46417.83,217.210700,217.210700,217.210700
XS GIS Cut Line= 6
668373.271188845851922.911220492668857.647024603851986.310733777
669314.670041638852031.317870775669712.252978504  852088.5760982
670047.952922105852117.683706446670468.442166785852142.992093887
#Sta/Elev= 30
8946.134507.90959048.816435.69749109.379411.87259180.036408.86249301.017363.5073
9331.241363.78929482.281341.99819663.221277.15679783.747219.30869813.878192.6282
 9844.01191.91039944.842103.624410005.5887.0095410015.7187.0333610025.8499.91073
 10046.1144.299410096.76 200.20110106.89202.008110217.82265.630510278.27292.2395
 10338.6294.701810418.97271.056410459.12269.426410519.31278.575710589.53304.3701
 10649.7312.006810689.79313.1231   10790303.559310870.15314.065711053.88326.3465
#Mann= 3 , 0 , 0
8946.134  0.0808       08946.134  0.0808       011053.88  0.0808       0
#XS Ineff= 2 , 0
       0                               0
Bank Sta=8946.134,11053.88
Exp/Cntr=0.3,0.1

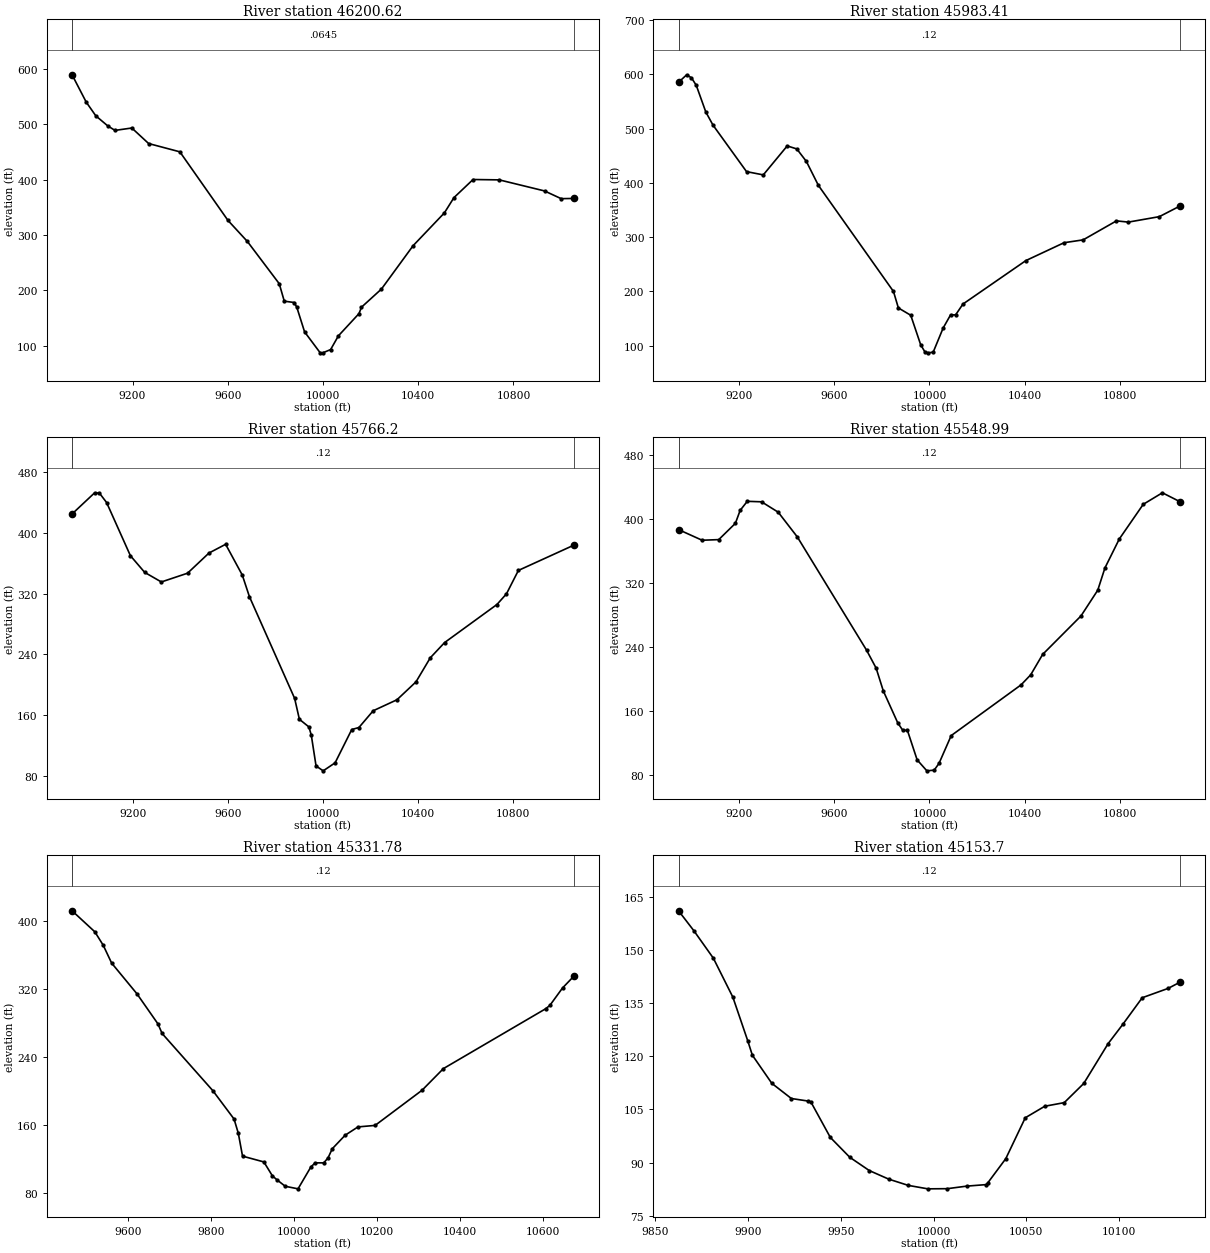
Type RM Length L Ch R = 1 ,46200.62,217.210600,217.210600,217.210600
XS GIS Cut Line= 6
668316.145678197852047.847410092669090.275983045852161.272602375
669519.008467206852321.663475055669726.010984188852370.794133997
669968.275947546852396.233139252670378.279750952852403.182351083
#Sta/Elev= 30
8946.042589.54229005.412540.21659045.762515.38049096.199497.07239126.462489.0436
9197.074493.36299267.687465.28859398.824 450.3119600.968326.36349682.482  288.32
 9816.37211.97469837.475180.42939879.684178.00719890.393169.07679922.773124.9504
9988.26987.16829    9999 87.070210032.12 92.960210064.98 117.87910151.22157.9052
 10161.8169.545210245.62202.333510378.73280.734310510.03339.975510550.26367.5668
 10630.5 400.28910740.62399.621610930.66379.643811000.66365.671711053.94 366.079
#Mann= 3 , 0 , 0
8946.042  0.0645       08946.042  0.0645       011053.94  0.0645       0
#XS Ineff= 2 , 0
       0                               0
Bank Sta=8946.042,11053.94
Exp/Cntr=0.3,0.1

Type RM Length L Ch R = 1 ,45983.41,217.210700,217.210700,217.210700
XS GIS Cut Line= 6
668220.972278227852286.613475161668956.380891058852374.432972483
669423.437342576852498.424359669669613.857583612852532.841115366
669893.053254962 852552.10752996670303.173145919 852543.70243378
#Sta/Elev= 30
8945.873585.19878980.098 599.0929000.213593.48399020.329579.69489060.561530.4364
9090.735506.27399231.547420.62739301.953414.61729402.533468.00819442.765462.4384
9483.074439.34489533.516395.20929848.912199.77629869.488169.41659921.448155.9274
9963.226101.61079981.24788.149079994.71886.68708 10015.787.8506210057.66 132.463
10089.11156.8358 10109.8156.537710140.85176.6071 10405.2256.689910565.68289.6397
10645.76294.854110785.76329.869310835.77327.599410965.85337.646311054.08357.5659
#Mann= 3 , 0 , 0
8945.873    0.12       08945.873    0.12       011054.08    0.12       0
#XS Ineff= 2 , 0
       0                               0
Bank Sta=8945.873,11054.08
Exp/Cntr=0.3,0.1

Type RM Length L Ch R = 1 , 45766.2,217.210600,217.210600,217.210600
XS GIS Cut Line= 6
668180.076927432852640.611777655668658.960612715852660.630515239
669098.749519924852668.499455171669340.059875147852660.796610934
669819.346609456852659.993156395670287.610692497852632.686809439
#Sta/Elev= 30
8945.469424.73949040.506452.6043 9060.53452.13289090.566   439.89190.674369.8691
9250.712347.92229320.756335.32959430.823346.84859520.849373.36339590.869384.8657
9660.888344.41559690.897 315.9939880.906182.23549900.909154.75139940.914144.7101
9950.921133.94069970.94293.3729710000.9886.9692310051.0197.4981810121.04141.3176
10151.04143.914710211.05165.957810311.05180.436410391.05 203.99510451.05235.6014
10511.06255.6031 10731.2305.685310771.23319.693710821.34350.496111054.51 383.736
#Mann= 3 , 0 , 0
8945.469    0.12       08945.469    0.12       011054.51    0.12       0
#XS Ineff= 2 , 0
       0                               0
Bank Sta=8945.469,11054.51
Exp/Cntr=0.3,0.1

Type RM Length L Ch R = 1 ,45548.99,217.210700,217.210700,217.210700
XS GIS Cut Line= 6
668205.903607718852967.377506914668614.471615081852958.477081418
  668947.1411129852932.193813151669132.704171766852905.680394338
669551.021005244 852824.55069308670299.909812643852733.770756753
#Sta/Elev= 30
8944.748387.08819043.848 373.751 9113.85374.53879183.872394.91899203.885411.1318
9233.904422.47889293.941421.84599363.999408.84939444.153377.98079735.443 236.246
9775.767 213.7399806.113185.10159866.865145.13739887.191136.19429907.563135.6385
9948.30798.88651 9989.2885.14751   1002086.0205210040.4694.5498510091.62129.2806
 10385.6192.789210425.95205.327110476.32230.886110637.45 279.01310707.94311.2037
10738.15339.072910798.57375.306310899.28418.705110979.84433.155911055.27421.7579
#Mann= 3 , 0 , 0
8944.748    0.12       08944.748    0.12       011055.27    0.12       0
#XS Ineff= 2 , 0
       0                               0
Bank Sta=8944.748,11055.27
Exp/Cntr=0.3,0.1

Type RM Length L Ch R = 1 ,45331.78,178.082600,178.082600,178.082600
XS GIS Cut Line= 6
668790.585248952 853188.94211307668879.453617736853176.626922191
  669009.7596677  853155.0450736669212.771284389853114.141295871
 669704.11699543852993.275298625669971.772731507852934.312808251
#Sta/Elev= 30
9465.268412.27079520.202 387.4629540.393371.63849560.607350.68289621.425314.6428
9672.106279.18089682.242267.80119804.407200.50659855.542167.10619865.769150.4379
9875.996123.42419927.341116.61099947.925100.22889958.21695.84866  9978.887.95497
 10009.784.9316110040.65110.701810050.96 115.51410071.59115.506610081.91 121.295
10092.22132.140410123.17 148.05410154.11157.829910195.37159.602310308.53201.0051
10359.94 226.47810606.04296.859210616.26300.767510646.91321.372210674.25335.2791
#Mann= 3 , 0 , 0
9465.268    0.12       09465.268    0.12       010674.25    0.12       0
#XS Ineff= 2 , 0
       0                               0
Bank Sta=9465.268,10674.25
Exp/Cntr=0.3,0.1

Type RM Length L Ch R = 1 , 45153.7,43.658200,43.658200,43.658200
XS GIS Cut Line= 2
669217.133889884853306.512714148669474.535216182853222.990159914
#Sta/Elev= 30
9862.452161.13929870.722155.50069881.236 147.7379891.749136.73399899.754124.4443
9902.262120.33649912.775112.37919923.289108.09929932.154107.39129933.802107.1471
9944.31597.102269954.82891.482999965.34287.736399975.85585.309239986.36883.54765
9996.88282.5767410007.3982.6210510017.9183.3445310028.4283.7746810029.3584.34484
10038.9391.0975510049.45102.655110059.96105.910510070.47106.931310080.99112.3509
10094.15123.617910102.01129.020610112.53136.570710126.55139.221410133.07141.0161
#Mann= 3 , 0 , 0
9862.452    0.12       09862.452    0.12       010133.07    0.12       0
#XS Ineff= 2 , 0
       0                               0
Bank Sta=9862.452,10133.07
Exp/Cntr=0.3,0.1