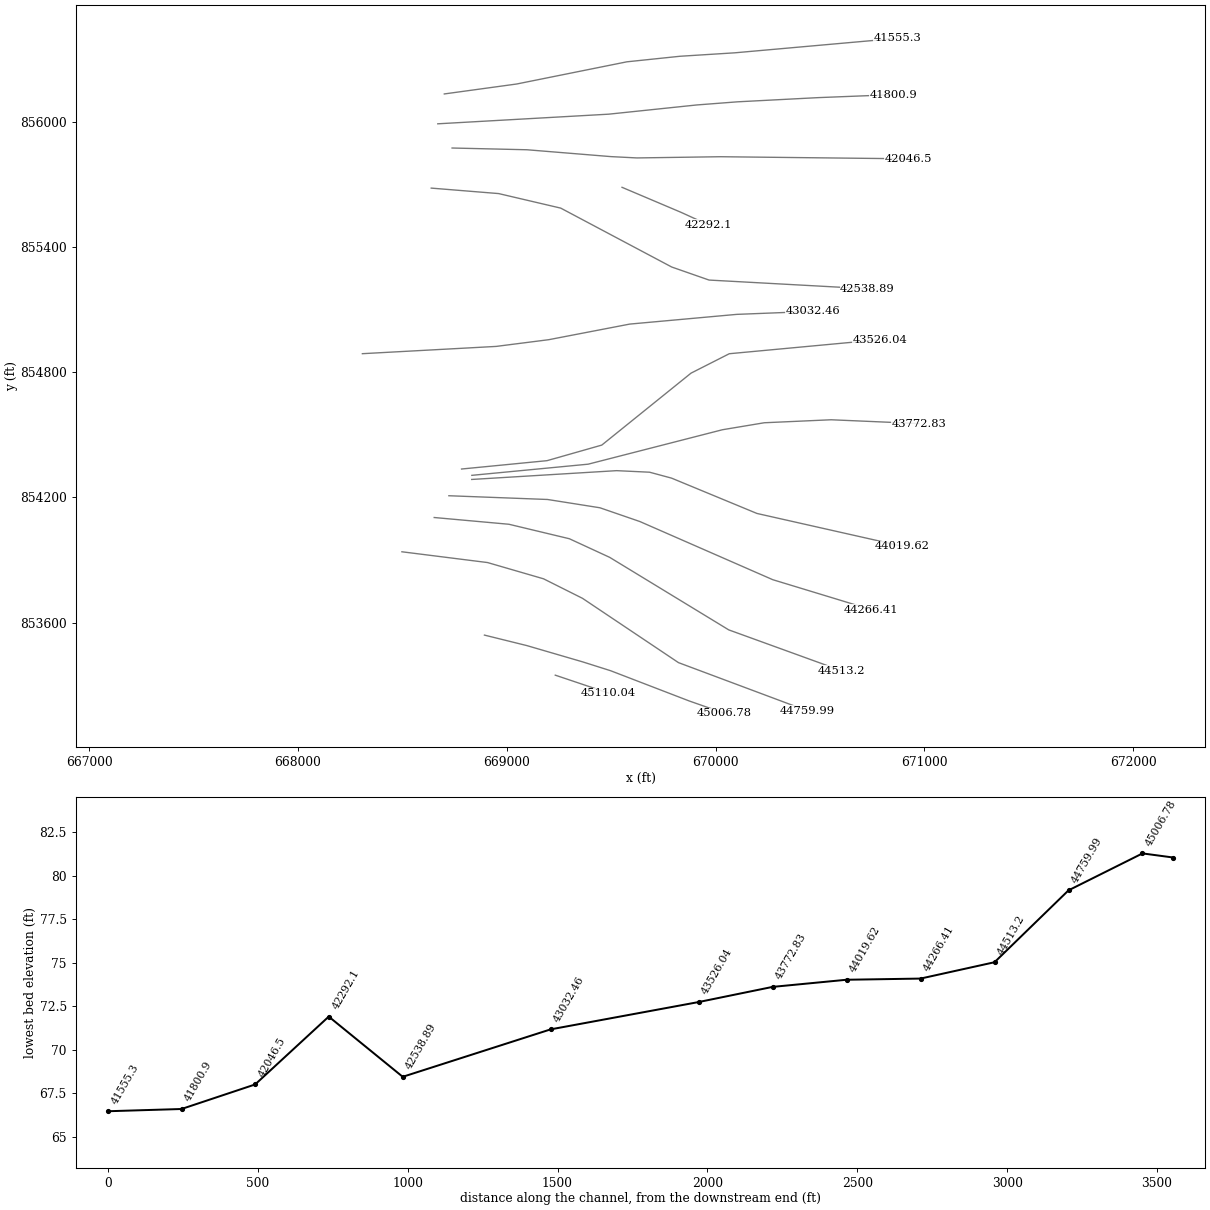
HEC-RAS study 13716_ras.prj: 13716

--- 13716_ras.g01 (geometry) --- (continued)

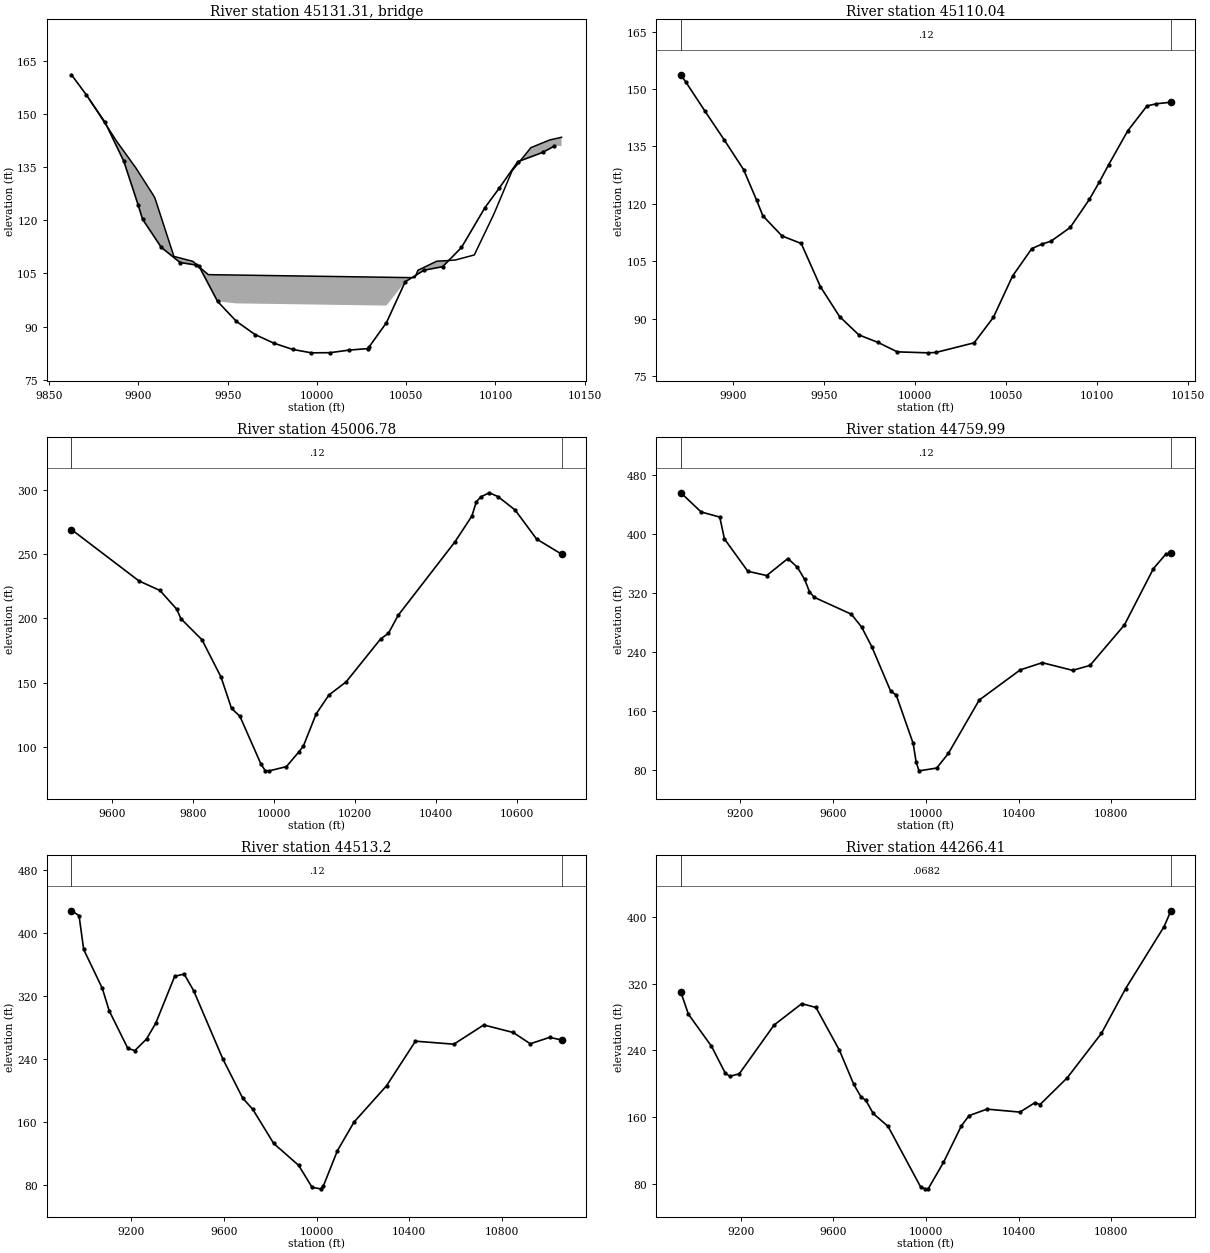
Type RM Length L Ch R = 3 ,45131.31,,,
BEGIN DESCRIPTION:
END DESCRIPTION:
Bridge Culvert--1,0,-1,-1, 0
Deck Dist Width WeirC Skew NumUp NumDn MinLoCord MaxHiCord MaxSubmerge Is_Ogee
8.213650,27.230900,2.6,0, 30, 30, , , 0.95, 0, 0,0,,
 9872.64 9877.32 9878.77 9887.95 9898.58 9908.25 9909.21 9919.84 9928.06 9929.02
 9929.02 9930.45 9938.76 9939.1010054.9310056.5210060.9110060.9110067.0310069.16
10072.2010077.5810088.1610098.7510099.8610109.3310119.9210130.3710130.5010137.06
  154.02  150.49  149.36  142.22  134.78  127.17  126.31  109.83  108.74  108.62
  108.62  108.43  104.83  104.67  103.81  105.88  106.96  106.96  108.45  108.53
  108.61  108.81  110.23  121.37  122.64  133.98  140.57  142.71  142.73  143.48
 -845.98 -849.51 -850.64 -857.78 -865.22 -872.83 -873.69 -890.17 -891.26 -891.38
  100.62  100.43   96.83   96.67   95.81   97.88   98.96 -893.04 -891.55 -891.47
 -891.39 -891.19 -889.77 -878.63 -877.36 -866.02 -859.43 -857.29 -857.27 -856.52
 9872.64 9877.32 9878.77 9887.95 9898.58 9908.25 9909.21 9919.84 9928.06 9930.45
 9933.03 9933.03 9938.76 9939.1010054.9310056.5210064.9210064.9210067.0310069.16
10072.2010077.5810088.1610098.7510099.8610109.3310119.9210130.3710130.5010137.06
  154.02  150.49  149.36  142.22  134.78  127.17  126.31  109.83  108.74  108.43
  107.31  107.31  104.83  104.67  103.81  105.88  107.93  107.93  108.45  108.53
  108.61  108.81  110.23  121.37  122.64  133.98  140.57  142.71  142.73  143.48
 -845.98 -849.51 -850.64 -857.78 -865.22 -872.83 -873.69 -890.17 -891.26 -891.57
 -892.69   99.31   96.83   96.67   95.81   97.88   99.93 -892.07 -891.55 -891.47
 -891.39 -891.19 -889.77 -878.63 -877.36 -866.02 -859.43 -857.29 -857.27 -856.52
BR Coef=-1 , 0 , 0 ,, 0 ,,,0.8,0,1,0,
WSPro=,,,, 1 ,,,, 0 ,,,, 0 ,,,,-1 ,-1 ,-1 , 0 , 0 , 0 , 0 , 0
BC Design=,, 0 ,, 0 ,,,,,,

Type RM Length L Ch R = 1 ,45110.04,103.259200,103.259200,103.259200
XS GIS Cut Line= 2
669232.319808871853348.273991257669487.443247288853262.473549187
#Sta/Elev= 30
9871.335153.72969874.163151.76329884.713 144.1359895.264136.63539905.814128.9177
9912.977120.91649916.364116.86779926.915111.58369937.465109.62589948.01598.30798
9958.56690.488619969.11685.721499979.66783.750329990.21781.2931410007.0981.03565
10011.32 81.128410032.4283.6542810042.9790.2914910053.52101.106910064.07108.2756
10069.83109.495910074.62110.213610085.17113.805510095.72121.1528 10101.2125.7142
10106.27130.186610116.82139.103810127.37145.590510132.57146.1516 10140.5146.5569
#Mann= 3 , 0 , 0
9871.335    0.12       09871.335    0.12       0 10140.5    0.12       0
#XS Ineff= 2 , 0
       0                               0
Bank Sta=9871.335,10140.5
Exp/Cntr=0.3,0.1

Type RM Length L Ch R = 1 ,45006.78,246.789400,246.789400,246.789400
XS GIS Cut Line= 6
668893.027547733853540.172851748669095.793174192853489.994649017
669363.120299628853412.033540219669497.467196744853369.502766694
669874.124381392853224.567900445670043.620589671853165.252352349
#Sta/Elev= 30
9499.872269.16459666.577229.18919718.388221.77029760.055207.15719770.471199.7281
9822.554183.30089869.511154.3085 9895.47129.91469916.303123.70979968.38686.42285
9978.803 81.42629989.22981.2733110031.1884.5793210062.65 96.282810073.14100.5935
10104.61125.5173 10136.2140.303710178.79 150.53510264.29184.089410283.43188.3584
10307.24202.3123 10448.2 259.75510489.77279.738610500.51290.630210511.24294.5566
10532.71297.811410553.98 294.89110596.51284.420310649.61261.803510711.37250.0365
#Mann= 3 , 0 , 0
9499.872    0.12       09499.872    0.12       010711.37    0.12       0
#XS Ineff= 2 , 0
       0                               0
Bank Sta=9499.872,10711.37
Exp/Cntr=0.3,0.1

Type RM Length L Ch R = 1 ,44759.99,246.789500,246.789500,246.789500
XS GIS Cut Line= 6
668497.788662192853939.229750582668907.870666785 853887.63432462
669176.167103241 853809.74722223 669362.75776708853716.234251904
669822.325822767 853408.32611357670437.393387701 853178.33035357
#Sta/Elev= 30
 8942.88456.14829030.388430.14489110.765423.19089130.885393.62759231.761349.7456
9313.383343.92499404.714367.03779446.001 355.0559477.048338.66989497.746321.9538
9518.476314.41129678.388291.52319722.362274.29859766.286247.6909 9847.84187.3942
9872.014181.96679945.049116.38649957.71191.591819970.37279.1525710046.7382.92081
10097.13102.866810229.98175.088710407.07216.026810502.02225.7677 10632.9215.4241
10707.98222.085810856.39276.890910981.82353.418611033.84372.482911057.14375.1079
#Mann= 3 , 0 , 0
 8942.88    0.12       0 8942.88    0.12       011057.14    0.12       0
#XS Ineff= 2 , 0
       0                               0
Bank Sta=8942.88,11057.14
Exp/Cntr=0.3,0.1

Type RM Length L Ch R = 1 , 44513.2,246.789400,246.789400,246.789400
XS GIS Cut Line= 6
 668652.43283689854103.363386407669010.492448049854071.004181276
669299.883128482854001.668779164669492.983844107853912.483409206
670063.160397298853565.155506867670604.593309431853368.891960299
#Sta/Elev= 30
8942.209428.39598974.845422.30918994.887379.19859075.055329.97779105.132301.2252
9185.501253.50229215.721250.75099266.087265.37899306.405285.79679387.671345.0654
9428.545348.0202 9469.43326.97219594.752240.61729680.987190.49769724.883176.0441
9815.167132.72759922.868104.85419981.117 76.866410017.5475.0235610029.6978.75926
10090.41123.638310162.02159.902510302.23205.992210427.18262.675810592.86258.8487
 10721.9283.287510849.12273.724110922.84259.385611006.23267.503511057.82264.2803
#Mann= 3 , 0 , 0
8942.209    0.12       08942.209    0.12       011057.82    0.12       0
#XS Ineff= 2 , 0
       0                               0
Bank Sta=8942.209,11057.82
Exp/Cntr=0.3,0.1

Type RM Length L Ch R = 1 ,44266.41,246.789400,246.789400,246.789400
XS GIS Cut Line= 6
668722.759067192854207.656724247669195.075530856854189.734652221
 669446.07091294854150.032823801669637.549016014854084.059390721
670273.982842682853805.547860185670743.768023104853662.679915217
#Sta/Elev= 30
8942.015 310.0278974.266283.60769074.299 245.0399134.318212.50439154.325209.0697
9194.338211.99089344.536270.45179464.061296.0678 9525.42291.51719627.024240.0338
9688.796199.25229719.976184.2741 9740.96180.17979772.567164.42749836.901148.8874
9977.58676.228789997.98374.0846510010.1774.2214810075.88105.725710153.32 149.605
10186.51161.881910263.89169.635710406.17166.068610471.26177.448110492.74175.0853
10610.25207.180610757.97  260.4710862.58314.208911028.27388.328411058.01407.4308
#Mann= 3 , 0 , 0
8942.015  0.0682       08942.015  0.0682       011058.01  0.0682       0
#XS Ineff= 2 , 0
       0                               0
Bank Sta=8942.015,11058.01
Exp/Cntr=0.3,0.1

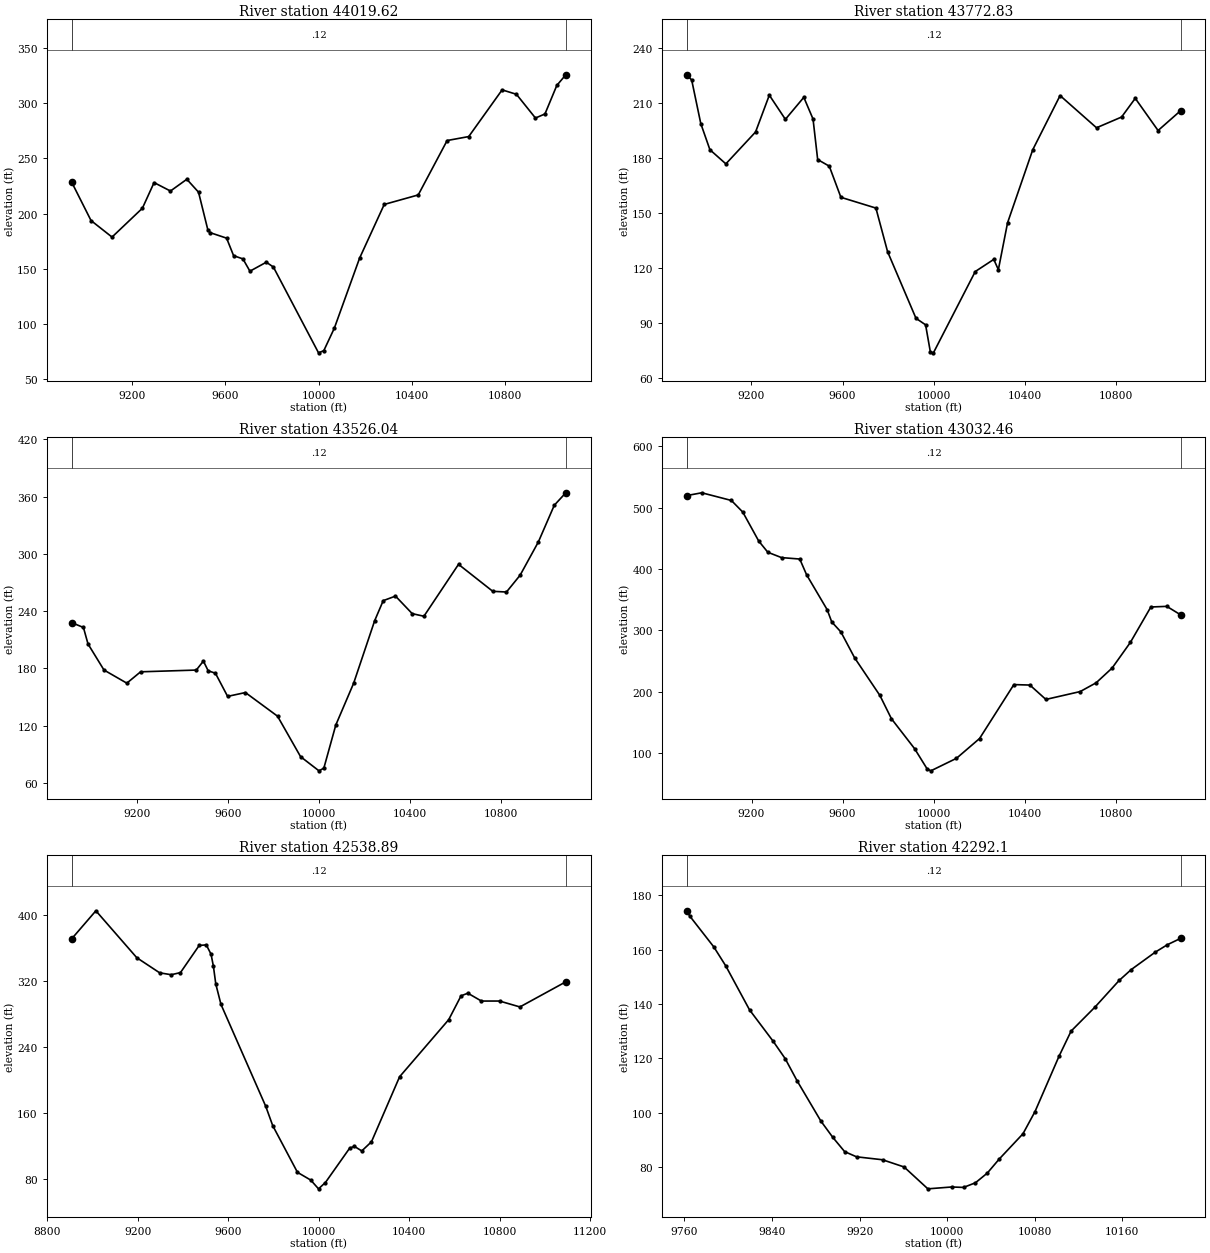
Type RM Length L Ch R = 1 ,44019.62,246.789500,246.789500,246.789500
XS GIS Cut Line= 6
668832.099656759854285.643217411669526.314846763854327.795165183
669683.951212918854320.349629692 669789.26245859854291.997758818
670198.253749627854122.793014733670892.864491054853966.246147612
#Sta/Elev= 30
8940.614228.44759023.554193.72319113.624178.76339243.819204.87849293.931228.0764
9364.141220.43979434.379231.0849 9484.55219.39379524.687185.12619534.721182.7492
9604.875177.7965 9634.92161.92969674.922159.02239704.923 147.897 9775.18 156.024
9805.513151.66559999.08774.0170710021.68  75.98910066.7896.2922810175.19159.7117
10280.87208.311210426.66216.902810550.58266.137210643.11269.712210786.36311.9779
 10847.7307.980810929.29286.489110970.01290.172611020.91316.005511059.46325.6295
#Mann= 3 , 0 , 0
8940.614    0.12       08940.614    0.12       011059.46    0.12       0
#XS Ineff= 2 , 0
       0                               0
Bank Sta=8940.614,11059.46
Exp/Cntr=0.3,0.1

Type RM Length L Ch R = 1 ,43772.83,246.789400,246.789400,246.789400
XS GIS Cut Line= 6
668832.686929545 854305.35553896669389.881593803854358.812134676
670032.597618327854523.686555049670233.362131289854557.209291751
670553.456480811854571.530055554670974.235007811854553.371010515
#Sta/Elev= 30
 8915.08 225.446 8937.42 222.6258977.468198.78559017.516 184.523  9087.6176.8009
9218.006194.20879278.386214.31999348.939201.11719429.889213.12539470.364201.2794
 9490.72179.15569541.707  175.549592.693158.53929746.401152.65899797.736128.8432
9922.45192.463779964.62588.903289985.71273.97916 9999.0173.6069210182.71118.0035
10264.01124.6355 10284.2119.015210324.57144.618210435.09184.480810555.21214.0906
10715.23196.507410825.27202.377710885.33212.5816 10985.5  195.0111084.91205.8887
#Mann= 3 , 0 , 0
 8915.08    0.12       0 8915.08    0.12       011084.91    0.12       0
#XS Ineff= 2 , 0
       0                10099.81       0
Bank Sta=8915.08,11084.91
Exp/Cntr=0.3,0.1

Type RM Length L Ch R = 1 ,43526.04,493.578900,493.578900,493.578900
XS GIS Cut Line= 6
668783.427787719854335.626051411669192.802732063854375.631709881
669455.140960007 854450.26766849669882.539574299854794.839338656
670065.722298404854887.828250392670785.596384097854954.971727552
#Sta/Elev= 30
8914.985228.03468966.628222.93038986.656205.66449056.827178.36999157.181164.5991
9217.644176.4969 9462.21178.32669493.402187.74099514.331177.59019546.287174.9875
 9599.72150.74259677.944154.76269818.938130.01659920.14587.59584   1000172.73632
10022.4375.6028810074.87120.736410153.19164.496110245.64230.104510283.13251.0557
10337.03255.826610410.38237.447810461.81 234.71810613.81289.104710764.28260.8331
10824.37260.102310884.39277.748510964.39312.559311034.39351.025811084.99 364.083
#Mann= 3 , 0 , 0
8914.985    0.12       08914.985    0.12       011084.99    0.12       0
#XS Ineff= 2 , 0
       0                               0
Bank Sta=8914.985,11084.99
Exp/Cntr=0.3,0.1

Type RM Length L Ch R = 1 ,43032.46,493.578900,493.578900,493.578900
XS GIS Cut Line= 6
668308.387889211854888.030716986668948.975356249854922.848664307
669201.237663519854955.114519439669589.090427603855029.808559717
670101.472578217855076.311711565670466.096480311855090.637012903
#Sta/Elev= 30
8914.733519.43668981.402524.05129111.511511.52779161.554492.62129231.613445.4489
9271.646427.15229331.744418.47959411.898 416.1229441.999390.42519532.302333.6375
9552.369313.68559592.609297.38949652.987 255.1419763.977193.90159814.537156.0464
9916.223107.32479970.95774.567049987.64571.1678810100.2491.5533210201.68 123.799
 10352.4211.638510422.73210.884110493.05187.466210643.61200.270110713.83214.5659
10783.93238.583310864.04 280.26510954.12338.026911024.14339.049911085.26325.1681
#Mann= 3 , 0 , 0
8914.733    0.12       08914.733    0.12       011085.26    0.12       0
#XS Ineff= 2 , 0
       0                               0
Bank Sta=8914.733,11085.26
Exp/Cntr=0.3,0.1

Type RM Length L Ch R = 1 ,42538.89,246.789400,246.789400,246.789400
XS GIS Cut Line= 6
668638.185012645855681.074558391668961.076173415855654.874447497
669258.464363243855585.233657754669790.002517392855303.143381368
669968.965809256855240.650018398670727.872375909855199.099977089
#Sta/Elev= 30
8908.067371.31089014.995405.27859195.852348.41139296.915 330.117 9347.97327.8206
9388.815330.38059471.569363.28499502.984363.96359523.928352.7241  9534.4338.1441
9544.985 316.5759567.878 291.8669765.664168.4703 9796.54145.03839905.96888.42949
 9964.6779.04197    9999 68.442610029.3976.0648410136.82117.780210157.35119.8962
10190.19114.359210233.03125.430510357.35204.2124 10574.4273.387910628.97302.2485
10658.99305.425710719.03295.925910799.05295.942610889.06 288.79411091.97319.2124
#Mann= 3 , 0 , 0
8908.067    0.12       08908.067    0.12       011091.97    0.12       0
#XS Ineff= 2 , 0
       0                               0
Bank Sta=8908.067,11091.97
Exp/Cntr=0.3,0.1

Type RM Length L Ch R = 1 , 42292.1,245.599700,245.599700,245.599700
XS GIS Cut Line= 3
669552.057237983855684.864910215669834.609321356855565.073243558
669966.119738013 855505.17741023
#Sta/Elev= 30
9761.921 174.2919765.117172.1913 9786.84160.95759797.702153.99919819.425137.8123
9841.148126.1677 9852.01119.84269862.872111.68469884.59596.864539895.45690.88022
9906.31885.60363 9917.1883.694899940.90982.610739960.62679.951899982.349 71.9013
10004.0772.5835110014.9372.42687 10025.874.1276810036.6677.7068510047.5282.86507
10069.2592.1917910080.24100.361210102.21120.7635 10113.2129.986810135.18138.8977
10157.15148.654810168.14152.639310190.12159.062710201.11161.783510213.33164.1485
#Mann= 3 , 0 , 0
9761.921    0.12       09761.921    0.12       010213.33    0.12       0
#XS Ineff= 2 , 0
       0                               0
Bank Sta=9761.921,10213.33
Exp/Cntr=0.3,0.1

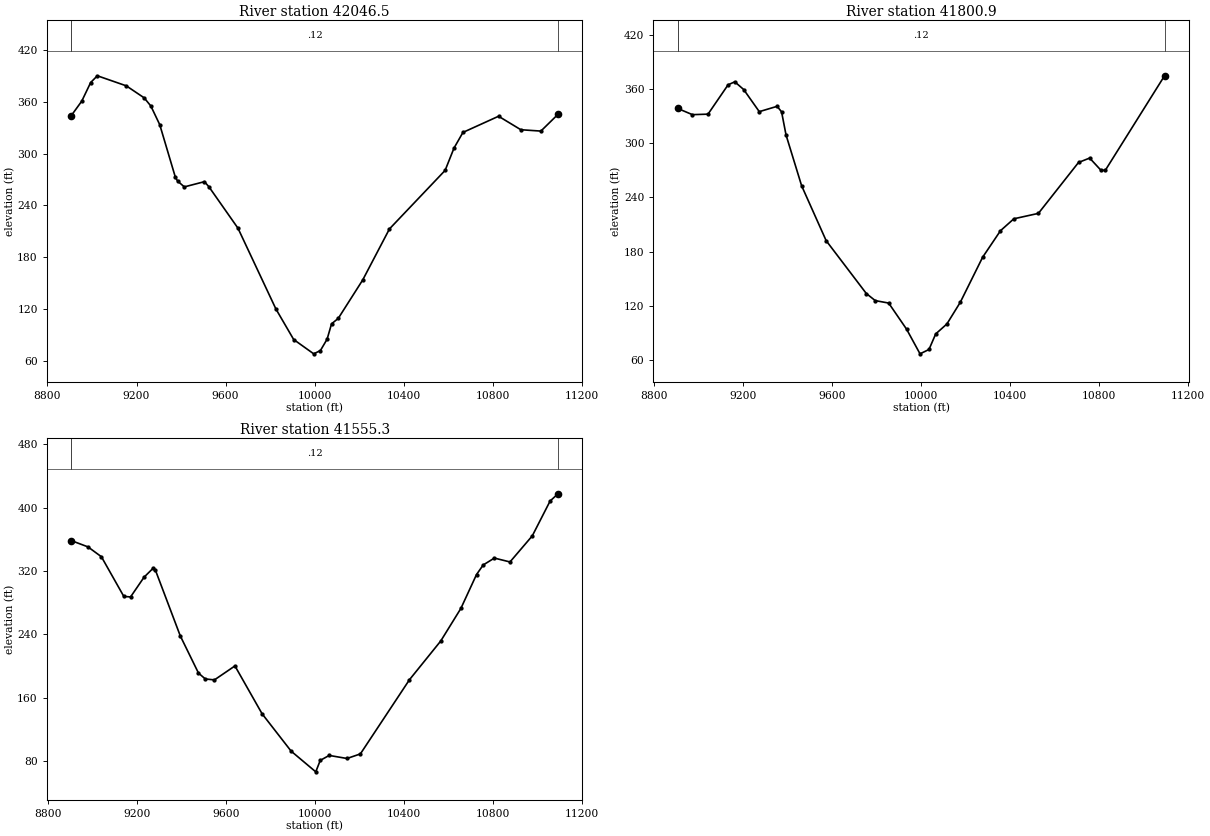
Type RM Length L Ch R = 1 , 42046.5,245.599700,245.599700,245.599700
XS GIS Cut Line= 6
668738.044903625 855873.09824911669096.857144475855864.753803502
669498.809872639855831.927929322669623.413119659855825.614096683
670024.112417969855831.403891195670921.991902424855821.385768658
#Sta/Elev= 30
8907.145343.95218954.101360.66758994.101382.23299024.102390.02249154.163378.3646
9234.217364.48259264.238355.03959304.326 333.3619374.486 272.4949384.516268.0689
 9414.63261.34159504.971267.38289525.047261.4807 9655.54213.51429825.753120.0459
 9905.7784.576869995.80168.00324 10025.871.8274610055.8184.9502910075.81102.7422
10105.81109.028310215.82153.573310335.84212.661910585.87280.457910625.88306.3583
10665.88324.431910825.88343.150610925.89327.540311015.89325.968311092.88345.4109
#Mann= 3 , 0 , 0
8907.145    0.12       08907.145    0.12       011092.88    0.12       0
#XS Ineff= 2 , 0
       0                               0
Bank Sta=8907.145,11092.88
Exp/Cntr=0.3,0.1

Type RM Length L Ch R = 1 , 41800.9,245.599700,245.599700,245.599700
XS GIS Cut Line= 6
668669.599525677855989.050030423669487.966086177856035.173590665
669909.668537376856079.294639195670105.981636272856094.415520816
670492.190862857856114.483247446670851.188056984 856128.60237107
#Sta/Elev= 30
8906.691338.56158972.186331.72639042.287332.28529132.417364.7871 9162.46368.1478
9202.517359.58949272.618335.05939352.734340.97029372.762334.88259392.791309.2429
9462.892252.86659573.085192.03859753.504 133.464 9793.66125.59339853.894122.8858
9934.37693.921829994.77466.5934210035.0271.4218210065.2188.6681110115.5299.72082
 10175.8123.7946 10276.1173.705710356.32203.0926 10416.4216.302510526.55 222.293
 10706.8278.725910756.85283.611510806.89270.2778 10826.9269.9211 11093.3 374.825
#Mann= 3 , 0 , 0
8906.691    0.12       08906.691    0.12       0 11093.3    0.12       0
#XS Ineff= 2 , 0
       0                               0
Bank Sta=8906.691,11093.3
Exp/Cntr=0.3,0.1

Type RM Length L Ch R = 1 , 41555.3,245.599700,245.599700,245.599700
XS GIS Cut Line= 6
668700.786169131856132.100002988669047.287688187856179.655194273
669575.318138482856285.969432182669829.703165218856312.553205407
670092.039043057856329.063090458670870.430748139856398.432645706
#Sta/Elev= 30
8905.616358.3147  8980.4350.42129040.862337.97969141.721287.88089172.096287.2349
9232.846312.18979273.458323.42629283.646321.18059395.716238.02329477.521191.1018
9508.259183.70539549.242182.51729641.455200.14319763.534139.75439894.24892.56813
10004.9666.4652810025.1280.9180910065.3487.1785610145.4783.3213710205.5789.09022
10426.39182.763510567.06231.636210657.49 272.70310727.83315.453310757.97327.5871
10808.16336.279410878.41331.378710978.71364.3358 11058.9408.323111094.42417.4342
#Mann= 3 , 0 , 0
8905.616    0.12       08905.616    0.12       011094.42    0.12       0
#XS Ineff= 2 , 0
       0                               0
Bank Sta=8905.616,11094.42
Exp/Cntr=0.3,0.1