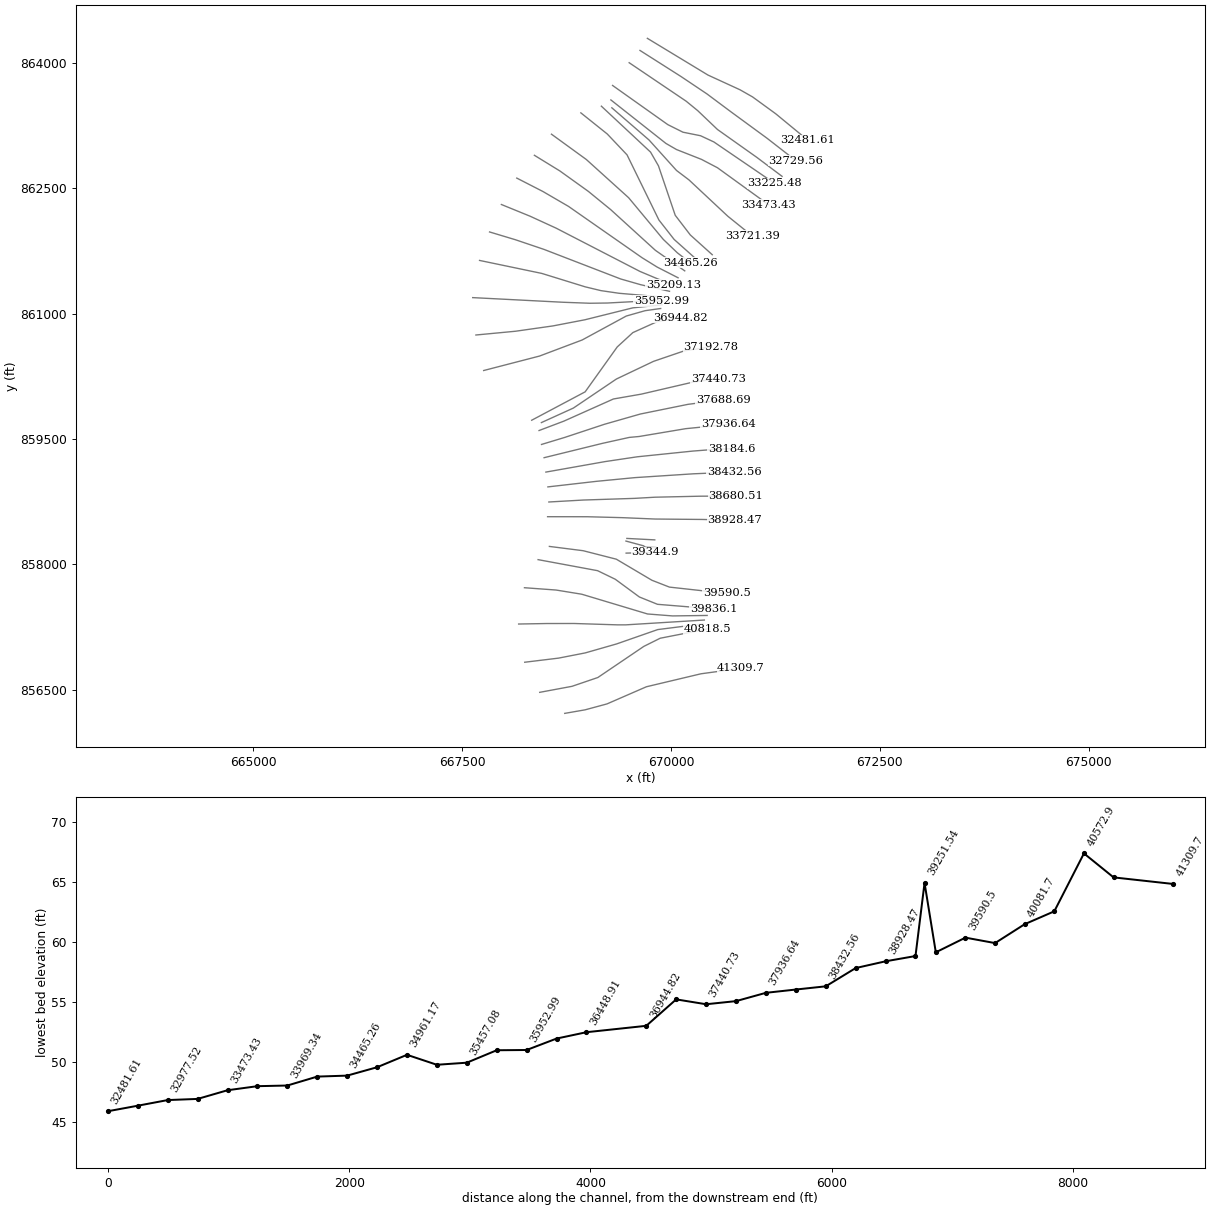
HEC-RAS study 13716_ras.prj: 13716

--- 13716_ras.g01 (geometry) --- (continued)

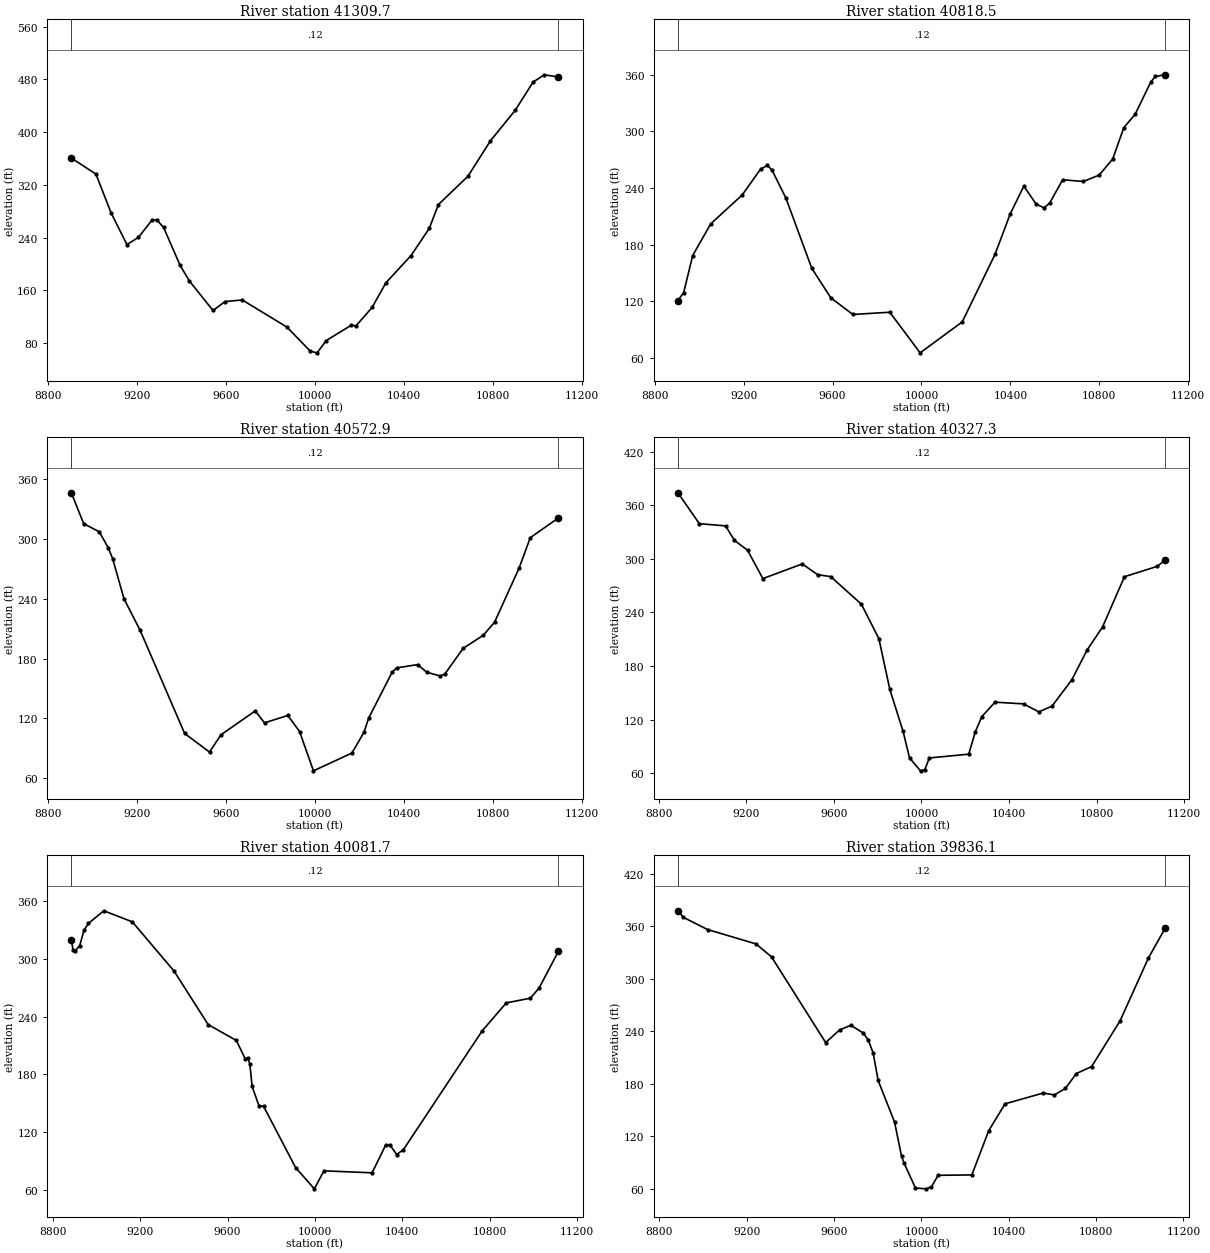
Type RM Length L Ch R = 1 , 41309.7,491.199400,491.199400,491.199400
XS GIS Cut Line= 6
668728.931039194856217.171595843  668973.2700198856259.730187956
669235.065364151856330.507916229669706.520831232856535.582865866
670360.056127207856690.800680257670838.648057826856756.072026098
#Sta/Elev= 30
8905.333360.66589015.976336.27319083.893277.52299155.165229.25679206.543240.1155
9268.196 266.4979288.886266.9989 9319.99255.20059393.225198.42319435.274174.2373
9542.111129.14199596.393142.72919673.512145.12319874.598103.8611 9979.1367.36904
10009.8864.8130410050.8583.4333310163.85106.826610184.52105.663410256.89133.7219
10318.92171.149910432.32212.660410514.31254.076710555.21290.118610687.61332.9279
10788.95386.8967 10899.9433.095410980.52475.985411030.77487.161711094.72483.7557
#Mann= 3 , 0 , 0
8905.333    0.12       08905.333    0.12       011094.72    0.12       0
#XS Ineff= 2 , 0
       0                               0
Bank Sta=8905.333,11094.72
Exp/Cntr=0.3,0.1

Type RM Length L Ch R = 1 , 40818.5,245.599800,245.599800,245.599800
XS GIS Cut Line= 6
668429.223560378856468.852451485668815.757856105856540.805744332
669125.214172513856646.258983861669675.927916582857018.788282701
669871.557822914857116.155883187670438.728845026857227.197090227
#Sta/Elev= 30
8904.519120.69018930.604129.24348971.083168.49339052.042201.99879194.579232.8564
9276.593260.14629307.438264.01859328.137258.85419390.594229.1811 9506.45155.0584
9592.403123.57689691.399106.03089857.616108.3765    999465.3569310183.2998.11677
10330.58169.575610399.44212.737810460.36 242.01810515.93222.888110551.14219.0646
10576.19223.884210635.03248.7656 10727.5246.919410799.02253.676210859.75270.5874
10910.35304.099310960.81318.037211031.27352.2953 11051.4358.201611095.41359.9869
#Mann= 3 , 0 , 0
8904.519    0.12       08904.519    0.12       011095.41    0.12       0
#XS Ineff= 2 , 0
       0                               0
Bank Sta=8904.519,11095.41
Exp/Cntr=0.3,0.1

Type RM Length L Ch R = 1 , 40572.9,245.599700,245.599700,245.599700
XS GIS Cut Line= 6
668249.845611755856828.989014716668654.930655475856878.229438913
668973.997950553856940.497211512669349.533273427857047.934811194
 669842.33046916857219.733768206670381.302861379857287.909050825
#Sta/Elev= 30
8904.342346.41658959.802315.42159030.191307.23519070.412291.12739090.523280.0648
9140.971 240.176 9213.87208.30869414.032104.85659526.07386.185999577.237103.5065
9731.605127.50349773.232115.49179878.235122.95229930.964106.79479993.41867.35055
10166.5585.2379210220.48  105.9410241.92 120.36510348.04166.6633 10368.9170.7501
10462.15173.949410503.29166.271810564.87162.473310585.22164.784910666.54190.2024
10757.51203.443710807.92216.448610918.63270.909310968.82301.3793 11095.6321.2281
#Mann= 3 , 0 , 0
8904.342    0.12       08904.342    0.12       0 11095.6    0.12       0
#XS Ineff= 2 , 0
       09818.839                       0
Bank Sta=8904.342,11095.6
Exp/Cntr=0.3,0.1

Type RM Length L Ch R = 1 , 40327.3,245.599700,245.599700,245.599700
XS GIS Cut Line= 6
668176.905435199857286.220691193668515.960270218857292.168923759
668842.037573866 857292.54365279669362.020658535857276.181960587
669459.503886158857276.208162031670400.096129388857333.864153584
#Sta/Elev= 30
8887.329374.10618985.439339.47479105.457337.00839145.463320.81099205.472309.7687
9275.476277.94349455.476294.38779525.476282.33299585.482280.17049725.508249.2797
9805.522210.61439855.565153.73769915.625107.10349945.65576.901569995.70562.53695
10015.72 63.960710035.7476.9630710215.8381.2034910245.86106.2082 10275.9123.3342
10335.97139.476610466.24137.5688 10536.4128.577210596.54135.113410686.75164.5081
10756.91 198.04210827.07223.619610927.24  280.0411077.51291.713511112.66298.7287
#Mann= 3 , 0 , 0
8887.329    0.12       08887.329    0.12       011112.66    0.12       0
#XS Ineff= 2 , 0
       0                               0
Bank Sta=8887.329,11112.66
Exp/Cntr=0.3,0.1

Type RM Length L Ch R = 1 , 40081.7,245.599700,245.599700,245.599700
XS GIS Cut Line= 6
668246.608450165857720.442139386668625.656603374857692.814071072
 668932.45788123857642.769065376669720.236164058857406.428329756
670018.817263095857383.160253546670433.925802184857388.664908918
#Sta/Elev= 30
8884.992318.90118893.394308.57568903.406308.1822 8923.43313.51438943.454329.5926
8963.478 336.4799033.564349.55119163.998338.11189355.253287.0715  9511.4231.6221
9640.461215.18039681.627195.89029693.597197.1551 9702.21  190.529712.606 167.517
9743.895147.50479764.754147.08369911.74983.427929997.60561.4643110041.2180.11749
10261.7378.0664110323.48106.596310343.85106.839910374.4197.0230910404.92 102.006
10766.01225.236110876.01254.127910986.04258.965911026.05269.4262   11115307.6814
#Mann= 3 , 0 , 0
8884.992    0.12       08884.992    0.12       0   11115    0.12       0
#XS Ineff= 2 , 0
       0                               0
Bank Sta=8884.992,11115
Exp/Cntr=0.3,0.1

Type RM Length L Ch R = 1 , 39836.1,245.599700,245.599700,245.599700
XS GIS Cut Line= 6
668409.864690055858056.427955088669122.141198358857924.405049136
669333.963663541857821.740684127669622.773417463857609.486934304
669839.450270311857522.026722299670510.932454354857467.358067356
#Sta/Elev= 30
8884.352377.54478909.586370.02099020.013356.13659242.051339.70659313.169324.9074
9561.241226.99519624.829241.37439676.758246.75879733.592237.81229756.156230.0088
 9778.72215.16859801.488183.70049876.902136.11119908.69897.212419921.13888.88441
9972.59960.8210510022.1859.8931610045.5862.2799510076.4675.3582110230.7875.79153
10308.27  126.4410383.04157.059310558.25 169.35610608.79167.145110659.12174.5499
10709.43191.569110779.59199.647810909.69251.7693 11039.7323.694711115.63357.3485
#Mann= 3 , 0 , 0
8884.352    0.12       08884.352    0.12       011115.63    0.12       0
#XS Ineff= 2 , 0
       0                               0
Bank Sta=8884.352,11115.63
Exp/Cntr=0.3,0.1

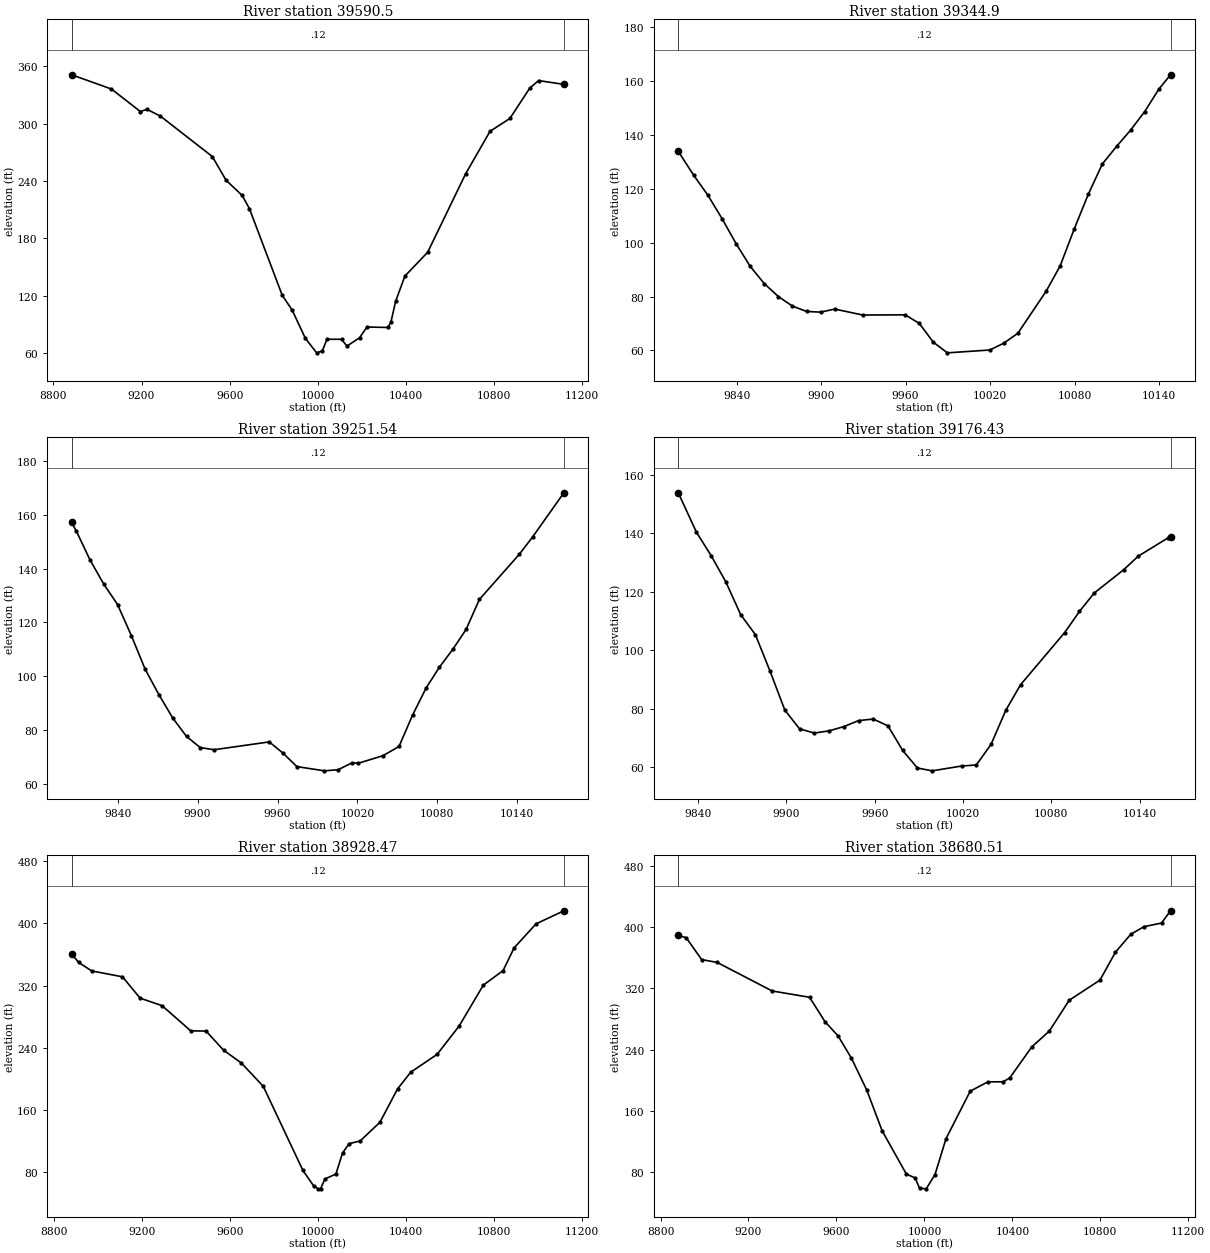
Type RM Length L Ch R = 1 , 39590.5,245.599700,245.599700,245.599700
XS GIS Cut Line= 6
668544.964817585  858214.6238262668949.089454432858163.327788214
669346.478606553858061.791749527669772.227478523857809.837332307
669981.879457565857727.998594646670669.840165804857651.826113778
#Sta/Elev= 30
8882.284351.13039063.194336.22969194.468312.69719224.873314.95979285.685 307.874
9521.413265.60889583.623 240.887 9656.79 224.953 9689.74211.16169838.789120.5272
9883.876105.05249943.86375.511549995.04760.3462410020.9662.4168710041.8574.59472
10108.37 74.506310132.36 67.356410190.08 76.142110223.66  87.36310318.67 86.8536
10332.4592.5783410353.61114.149610395.79140.633410499.15165.505810671.75247.6314
10782.35292.014310872.65305.466310962.76337.143311002.79345.078411117.71341.0955
#Mann= 3 , 0 , 0
8882.284    0.12       08882.284    0.12       011117.71    0.12       0
#XS Ineff= 2 , 0
       0                               0
Bank Sta=8882.284,11117.71
Exp/Cntr=0.3,0.1

Type RM Length L Ch R = 1 , 39344.9,93.361600,93.361600,93.361600
XS GIS Cut Line= 2
669463.949599087858134.517688006669813.341960192858143.198243544
#Sta/Elev= 30
9798.597133.86929809.651124.91729819.654117.56619829.657108.9192 9839.6699.63301
9849.66391.204959859.66684.80319 9869.67 80.00639879.67376.460729889.67674.47957
9899.679 74.22369909.68275.355519929.68873.143349959.69773.21536  9969.770.06113
9979.70363.055669989.707  59.12610019.7260.1731310029.7262.7028510039.7266.39668
10059.7381.9328710069.7391.3569910079.73105.081310089.74117.992210099.74129.2133
10109.74135.661310119.75141.732810129.75148.601310139.75156.8923 10148.1162.2519
#Mann= 3 , 0 , 0
9798.597    0.12       09798.597    0.12       0 10148.1    0.12       0
#XS Ineff= 2 , 0
       0                               0
Bank Sta=9798.597,10148.1
Exp/Cntr=0.3,0.1

Type RM Length L Ch R = 1 ,39251.54,75.111700,75.111700,75.111700
XS GIS Cut Line= 4
669461.687268406858278.631763011669669.686693579858222.717939034
669696.525329113 858204.82551536669818.417465419858201.470685929
#Sta/Elev= 30
9805.396157.12179808.826154.03029819.181143.25379829.536134.21359839.891126.6467
9850.246115.11869860.601102.62879870.95693.168489881.31184.520969891.66677.66341
9902.02173.527569912.37672.734349953.79775.636389964.15271.442719974.50766.48048
9995.21764.8989110005.5765.3268910015.9367.8703810020.7867.7299410039.1870.52506
 10051.273.9472810061.5185.7309410071.5295.6276510081.52103.379410091.52109.9601
10101.53117.366810111.53128.523610141.54145.298710151.55151.763410174.97168.1198
#Mann= 3 , 0 , 0
9805.396    0.12       09805.396    0.12       010174.97    0.12       0
#XS Ineff= 2 , 0
       0                               0
Bank Sta=9805.396,10174.97
Exp/Cntr=0.3,0.1

Type RM Length L Ch R = 1 ,39176.43,247.956300,247.956300,247.956300
XS GIS Cut Line= 2
669472.630154669858310.298938006669806.831543535858292.937826887
#Sta/Elev= 30
 9826.42153.82459838.806140.3381 9848.82132.30749858.833123.31229868.847112.1892
 9878.86105.34369888.87492.801159898.887 79.55489908.90173.163159918.91471.72596
9928.928  72.4819938.94173.921659948.95575.975189958.96876.514969968.98274.18359
9978.99565.770959989.00959.778459999.02258.8166610019.0560.4601510029.0660.82535
10039.0867.8883810049.0979.51062 10059.188.2237310089.14106.079610099.16113.2924
10109.17119.5584 10129.2127.528210139.21132.193210159.24138.369310161.07138.6712
#Mann= 3 , 0 , 0
 9826.42    0.12       0 9826.42    0.12       010161.07    0.12       0
#XS Ineff= 2 , 0
       0                               0
Bank Sta=9826.42,10161.07
Exp/Cntr=0.3,0.1

Type RM Length L Ch R = 1 ,38928.47,247.956200,247.956200,247.956200
XS GIS Cut Line= 6
668523.551811709858570.172670925668998.875816479858569.735195952
  669416.2652129858558.786924753669811.713011796 858542.23635464
670371.357481454858537.262014408670761.330744158858528.850557318
#Sta/Elev= 30
8880.796360.83218912.245349.89968972.248338.84629112.253331.28729192.258303.8051
9292.266294.13919422.294261.75979492.318261.42919572.346 236.6949652.373220.4232
9752.408 190.2869932.57282.084499982.62161.7265910002.6458.3788410012.6558.43116
10032.66 71.0437 10082.777.4645910112.72104.389510142.74 116.56510192.76119.9811
10282.77144.010910362.77186.952710422.77208.462210542.78 231.47410642.78267.8395
10752.79320.525910842.81339.290810892.82368.500610992.85399.475611119.21416.2624
#Mann= 3 , 0 , 0
8880.796    0.12       08880.796    0.12       011119.21    0.12       0
#XS Ineff= 2 , 0
       0                               0
Bank Sta=8880.796,11119.21
Exp/Cntr=0.3,0.1

Type RM Length L Ch R = 1 ,38680.51,247.956300,247.956300,247.956300
XS GIS Cut Line= 6
 668538.71364458858746.146197101668951.846113189858769.573952985
 669560.50656756858789.342895919669810.812022398858803.475868288
670350.409754358858815.509398834670775.844099064858817.397560799
#Sta/Elev= 30
8880.655389.18558917.013386.2027 8987.15357.56679057.288353.97819307.622316.5844
9477.753308.32739547.807276.52459607.834 257.7089667.856228.84939737.882186.9969
9807.908133.67179917.97177.136819958.04672.012529978.08458.5449710008.1557.81653
10048.2576.4882810098.31123.446410208.37185.549510288.39197.694410358.41197.8285
10388.42202.956710488.44243.441610568.46264.236610658.49304.4633 10798.5330.7775
 10868.5367.167610938.51390.713110998.51400.644611078.51405.409911119.35421.4481
#Mann= 3 , 0 , 0
8880.655    0.12       08880.655    0.12       011119.35    0.12       0
#XS Ineff= 2 , 0
       0                               0
Bank Sta=8880.655,11119.35
Exp/Cntr=0.3,0.1

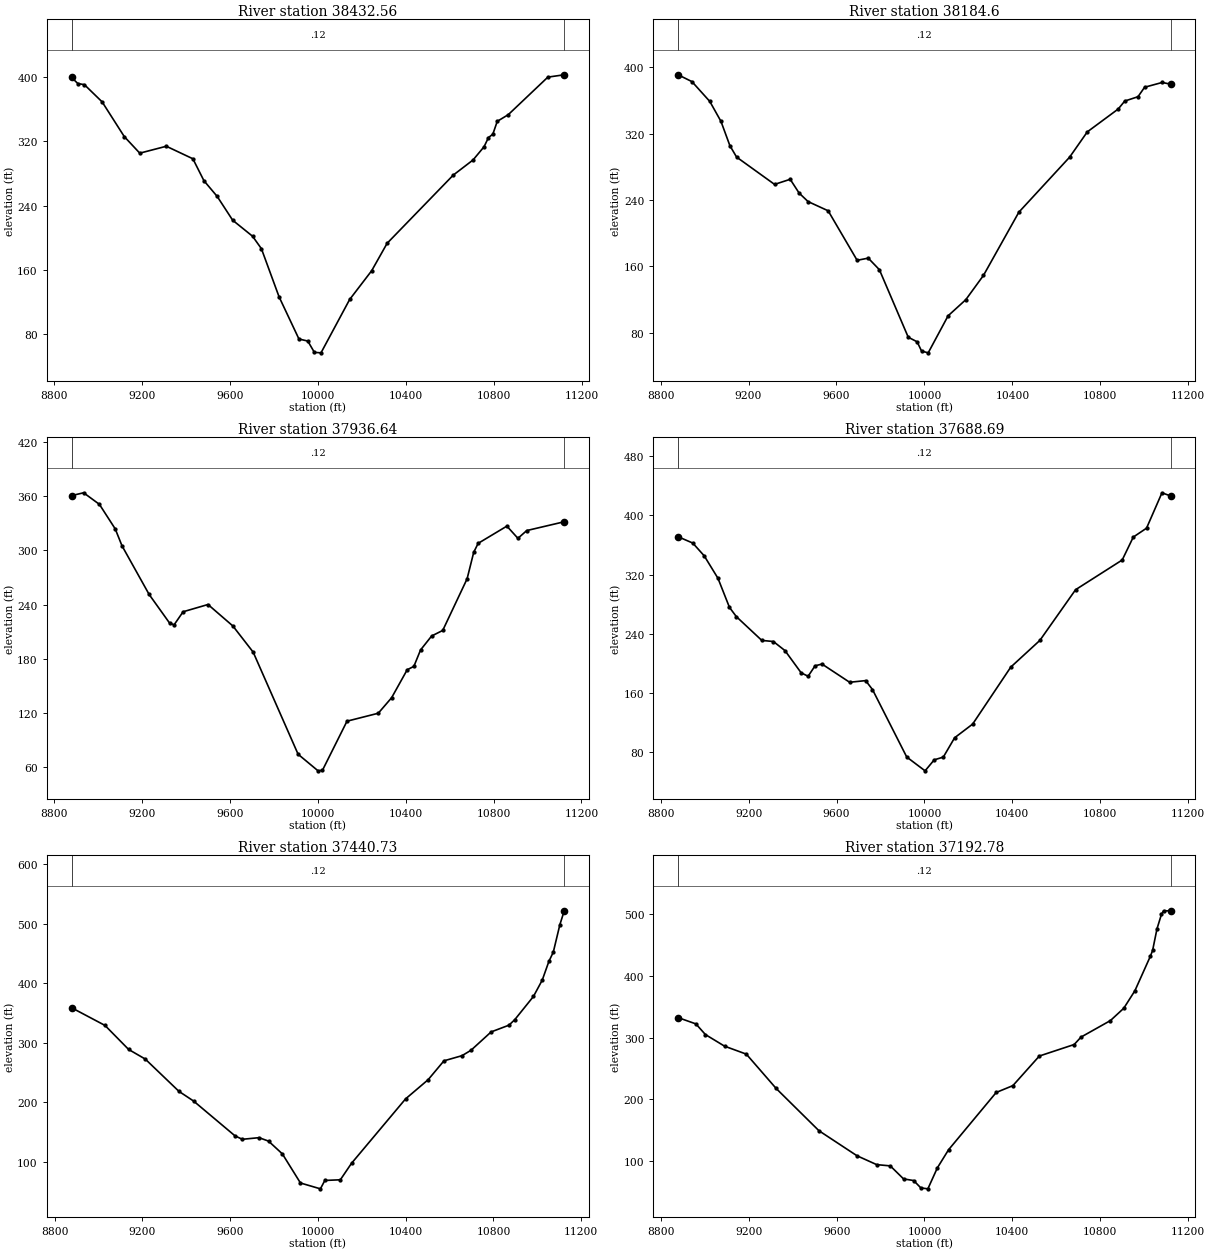
Type RM Length L Ch R = 1 ,38432.56,247.956200,247.956200,247.956200
XS GIS Cut Line= 6
 668527.16912328858926.816903265669111.091986769858993.555782068
669568.467305616859037.662516903 670269.70146473859083.410792153
  670560.3250775859095.570419735670759.477939228859100.054600923
#Sta/Elev= 30
8879.973399.79188907.996392.24468938.202390.77579018.752369.32189119.439326.0485
 9189.92305.35479310.672313.98839431.393 298.359 9481.68270.98459541.984251.3702
9612.338221.72079702.794201.72629742.996186.20559823.325126.13989913.68573.54615
9953.80371.013539983.87656.8798810013.95 56.298110144.26122.8468 10244.5158.7611
10314.67  192.9510615.21277.9532 10705.3296.864510755.35313.333410775.37324.7739
10795.38329.0469 10815.4345.059510865.44353.359311045.52400.209211120.02403.1329
#Mann= 3 , 0 , 0
8879.973    0.12       08879.973    0.12       011120.02    0.12       0
#XS Ineff= 2 , 0
       0                               0
Bank Sta=8879.973,11120.02
Exp/Cntr=0.3,0.1

Type RM Length L Ch R = 1 , 38184.6,247.956300,247.956300,247.956300
XS GIS Cut Line= 6
668503.033831243 859103.89947917669212.101378879859229.518001907
669597.290895094859286.888074674670263.697836002859355.516069053
670479.527139188859372.168570625670723.757832507859384.795068426
#Sta/Elev= 30
8879.723390.77248942.654382.5424  9023.9358.67749074.679334.67999115.301305.3854
9145.769291.68449318.416258.81359389.506 264.9499430.129248.36089470.752238.1355
9562.153227.02779693.913167.4426 9744.55170.03819795.187156.11339926.43874.82273
9966.80469.318049986.98658.1646510017.1956.0309110107.69100.611110188.14120.0079
10268.59149.273410429.48  225.3410660.55291.660910740.78322.036710881.19349.5251
10911.23359.169110971.31364.350111001.35375.757811081.46 381.53511120.27379.4083
#Mann= 3 , 0 , 0
8879.723    0.12       08879.723    0.12       011120.27    0.12       0
#XS Ineff= 2 , 0
       0                               0
Bank Sta=8879.723,11120.27
Exp/Cntr=0.3,0.1

Type RM Length L Ch R = 1 ,37936.64,247.956200,247.956200,247.956200
XS GIS Cut Line= 6
668481.782458153859276.147401284669182.432448929859448.243030236
669502.074312252859518.909134077669619.759679513859529.801752522
670178.362736333859623.546620119670685.299661435859673.920862691
#Sta/Elev= 30
8878.373360.85298933.061363.98129004.995 351.1429076.928 323.9769107.839305.1954
9231.506251.22949324.255219.63859344.866217.55269386.089232.09199499.449 240.134
9612.753216.31979705.093187.35449909.77974.1223610000.6455.7582310020.6656.38507
 10132.4 110.80710274.79119.603510335.67136.844210406.54167.817510436.92171.5579
10467.28189.733410517.78205.230510568.29211.389810679.26268.6175 10709.5298.1129
10729.66307.935310860.43327.0202 10910.7313.475210950.86322.100411121.63331.8606
#Mann= 3 , 0 , 0
8878.373    0.12       08878.373    0.12       011121.63    0.12       0
#XS Ineff= 2 , 0
       0                               0
Bank Sta=8878.373,11121.63
Exp/Cntr=0.3,0.1

Type RM Length L Ch R = 1 ,37688.69,247.956300,247.956300,247.956300
XS GIS Cut Line= 6
668450.877843269859434.623718365668726.589667773859517.983697633
669204.297387702859675.909124971669634.582176084859798.763783083
670204.858121803859914.550638368670624.750725324859968.586342037
#Sta/Elev= 30
8877.911371.2125 8944.66362.66218996.708345.46559059.498315.09819111.899275.7825
 9143.34263.29149259.217231.17889311.955229.72139364.692217.46359438.525 187.418
9470.167 182.776 9501.81196.89359533.371199.27399659.352174.66479732.244176.9218
9763.445164.81419919.44773.7204810002.9355.0671510044.6769.9151810086.0373.62677
10137.5899.7189510219.69118.209110393.47195.183910525.94231.229110688.61299.6741
10901.02339.792810951.43370.725111011.83382.764211082.17430.561211122.09426.1915
#Mann= 3 , 0 , 0
8877.911    0.12       08877.911    0.12       011122.09    0.12       0
#XS Ineff= 2 , 0
       0                               0
Bank Sta=8877.911,11122.09
Exp/Cntr=0.3,0.1

Type RM Length L Ch R = 1 ,37440.73,247.956200,247.956200,247.956200
XS GIS Cut Line= 6
668421.491257002 859601.24191371668718.984298445859713.721688837
669311.778343864859978.581717206669645.247858153860036.617881778
670260.897674947 860179.62510244670564.615263789860222.726321229
#Sta/Elev= 30
 8877.17358.69469029.434329.02319137.053288.73959212.879272.59449366.543218.3819
9433.119202.17269622.013143.73699655.347137.93799731.525140.67999774.825134.9072
9837.988113.43739920.37264.6215210011.3354.80771 10031.568.8865210102.2770.01522
10153.1397.6591610399.46205.726610502.46237.965610574.55269.6516 10656.7278.2646
10697.67287.310310789.62318.151110870.95329.471510897.52338.797410982.32377.5917
11022.61405.0876 11052.8436.452411072.93452.017111103.13498.364911122.88521.4459
#Mann= 3 , 0 , 0
 8877.17    0.12       0 8877.17    0.12       011122.88    0.12       0
#XS Ineff= 2 , 0
       0                               0
Bank Sta=8877.17,11122.88
Exp/Cntr=0.3,0.1

Type RM Length L Ch R = 1 ,37192.78,247.956300,247.956300,247.956300
XS GIS Cut Line= 6
668449.340811284859696.139112161668832.232479188 859869.84871482
 669347.64278371860217.587226736669792.152217619860428.927783389
  670161.1599678 860554.83107092670477.389696329860601.367239572
#Sta/Elev= 30
8877.005332.42118958.157322.22929001.369305.01949088.709286.1887 9188.09273.2835
9324.118 217.6869519.146149.28499692.549108.77269782.26594.408149844.41192.37563
9904.90371.281139950.84768.656979983.70656.7259410015.7555.2124710059.1989.29628
10110.11118.484310327.28211.221810403.39222.320810523.97270.2143 10682.8288.8569
10714.06300.891310847.88327.569410908.99347.583710959.68375.916611030.26431.8568
11040.33441.104611060.47476.300111080.56499.423711090.59505.364511123.06505.2283
#Mann= 3 , 0 , 0
8877.005    0.12       08877.005    0.12       011123.06    0.12       0
#XS Ineff= 2 , 0
       0                               0
Bank Sta=8877.005,11123.06
Exp/Cntr=0.3,0.1

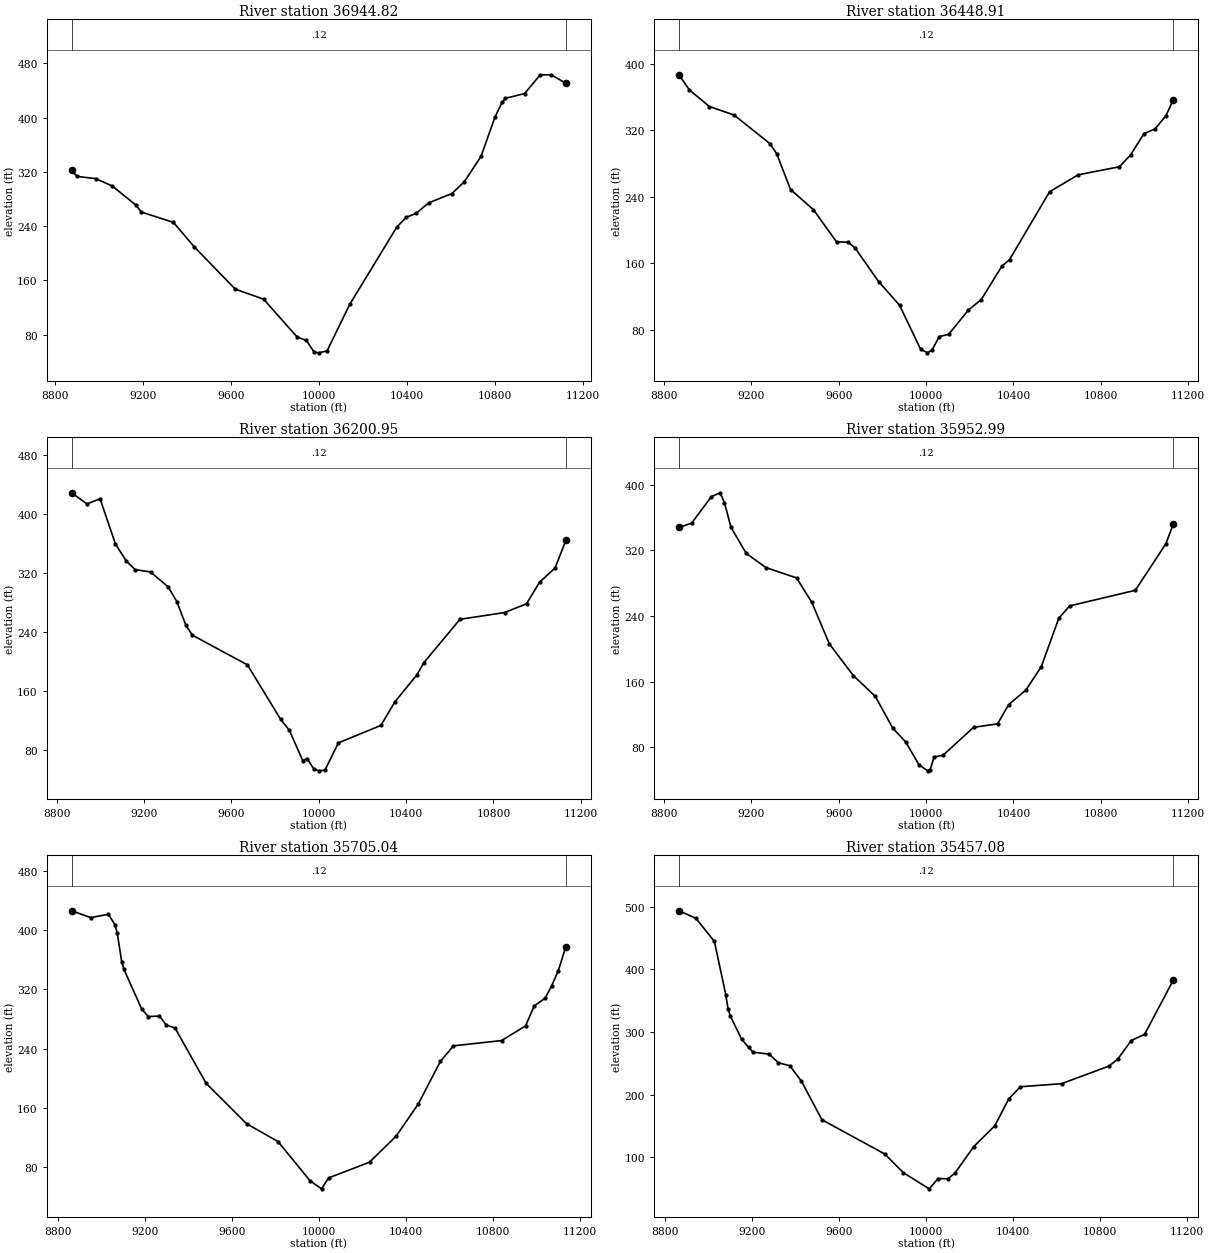
Type RM Length L Ch R = 1 ,36944.82,495.912500,495.912500,495.912500
XS GIS Cut Line= 6
668333.109724353859724.302288627668973.351191701860064.055321928
669357.554091371860601.442773475669544.300787275860772.653659139
669833.882619451860903.443397941670110.735796078860951.290562217
#Sta/Elev= 30
8876.233322.41678899.613313.20358985.054309.89499060.448299.09339169.688270.4913
9192.379260.73159339.145245.31659433.037209.47739620.273146.95919749.284 132.083
9902.33876.059419943.63471.424459978.66254.128039999.18453.0140610037.57  55.836
10140.88124.477210355.09238.548910397.23252.704310443.38258.798310499.81274.1343
10605.81287.899310661.87305.243610738.02342.674310801.64 400.85710833.12422.2207
10848.93428.316110936.17435.277311007.27462.994711057.68462.822311123.82450.5138
#Mann= 3 , 0 , 0
8876.233    0.12       08876.233    0.12       011123.82    0.12       0
#XS Ineff= 2 , 0
       0                               0
Bank Sta=8876.233,11123.82
Exp/Cntr=0.3,0.1

Type RM Length L Ch R = 1 ,36448.91,247.956200,247.956200,247.956200
XS GIS Cut Line= 6
667758.489451695860319.056039319 668427.23512523860492.183344742
668937.579796488 860684.50683592669465.797893539860970.992850367
669690.760607658861034.861478194669877.498570205861061.180444574
#Sta/Elev= 30
 8869.14386.52098916.518368.46569008.198 348.3969120.897338.22199286.086303.6445
9317.311291.16439379.761 248.6499484.548224.45849590.206185.81939643.436185.4258
9675.375178.43079782.401138.17799878.814109.60489974.70356.9489110006.5352.48258
10027.7455.9324710060.01 71.993810103.3174.6959310193.59103.850810252.29 116.386
10346.75156.426310382.17164.516510565.39246.038210696.49266.364510884.96276.0458
10936.27290.321110997.21315.852211047.84 321.40511098.15337.445911130.85 356.286
#Mann= 3 , 0 , 0
 8869.14    0.12       0 8869.14    0.12       011130.85    0.12       0
#XS Ineff= 2 , 0
       0                               0
Bank Sta=8869.14,11130.85
Exp/Cntr=0.3,0.1

Type RM Length L Ch R = 1 ,36200.95,247.956300,247.956300,247.956300
XS GIS Cut Line= 6
667665.484772225860744.018675034668138.220482564860788.860584903
668587.621288572860852.713570839668970.385817793860926.222188151
669544.391140763861069.003535663 669894.76577474861104.921900233
#Sta/Elev= 30
8868.574428.84288938.313413.72498998.507420.64559068.733359.58989118.999336.1877
9159.223324.70019229.615321.53659310.063301.36819350.307281.33919390.654249.7656
9420.914235.90639673.374195.55239825.195121.79569865.794106.72619926.69365.59942
9946.99368.501019977.47854.28968   1000151.9530110028.4953.0332410089.7889.84854
10284.64113.557710348.21145.259810450.12182.360810481.21 198.57510646.47257.3507
10850.44266.476410951.26278.415811011.49307.807211081.62326.706411131.43364.2689
#Mann= 3 , 0 , 0
8868.574    0.12       08868.574    0.12       011131.43    0.12       0
#XS Ineff= 2 , 0
       0                               0
Bank Sta=8868.574,11131.43
Exp/Cntr=0.3,0.1

Type RM Length L Ch R = 1 ,35952.99,247.956200,247.956200,247.956200
XS GIS Cut Line= 6
 667627.03275362861191.284759038668712.464308966861135.590667402
669030.937244989861123.876423093669241.247702158861126.708996215
669698.796891913861151.200096462 669888.45788827861150.214084582
#Sta/Elev= 30
8868.083348.13178926.126353.39019016.245385.58049056.297 390.4449076.324378.5557
9106.363348.25699176.455316.39989266.574299.16239406.758286.5063 9476.85256.5567
9556.955 206.007  9667.1167.22559767.232142.01239847.337103.22029907.41685.95775
9967.491 58.439710007.5351.0027810017.5451.8231210037.5668.0951210077.5969.97175
10217.68104.1348 10327.7108.330910377.71131.664710457.74149.805510527.82178.1316
10607.97237.205610658.06 252.37710958.42271.378911098.43328.1225 11131.9351.7284
#Mann= 3 , 0 , 0
8868.083    0.12       08868.083    0.12       0 11131.9    0.12       0
#XS Ineff= 2 , 0
       0                               0
Bank Sta=8868.083,11131.9
Exp/Cntr=0.3,0.1

Type RM Length L Ch R = 1 ,35705.04,247.956300,247.956300,247.956300
XS GIS Cut Line= 6
667709.033848761861636.265997204668453.542782968861480.989355261
668974.210035561 861320.20892758 669162.35699366861274.893476593
  669381.5225138861242.946984659669929.649137518861196.195461305
#Sta/Elev= 30
8864.443 425.9098951.917416.70969033.321421.19289063.877406.91259074.074 395.351
9094.468356.85049104.665346.8405 9186.24293.43939216.831 283.278 9267.83283.9356
9298.522272.00549339.444 267.7769482.708193.12229667.916138.8769 9813.05114.6727
9959.90261.8225110013.0150.9824810044.8365.6749710233.1686.8979410356.34122.3402
10457.77165.617410558.67222.759510619.01243.825410839.76250.877810950.08270.6579
10990.25297.698511040.47308.0613 11070.6325.039411100.73344.970211135.53377.6773
#Mann= 3 , 0 , 0
8864.443    0.12       08864.443    0.12       011135.53    0.12       0
#XS Ineff= 2 , 0
       0                               0
Bank Sta=8864.443,11135.53
Exp/Cntr=0.3,0.1

Type RM Length L Ch R = 1 ,35457.08,247.956200,247.956200,247.956200
XS GIS Cut Line= 6
667828.767844063 861976.89205402668137.097326497861884.234277177
668478.931289234861768.835665047669398.311025282861414.486123558
669635.301466155 861346.55395694669983.313793844 861266.80056075
#Sta/Elev= 30
8864.088493.52488941.847481.56389026.906444.67099079.192359.74129089.658337.2248
9100.124325.61379152.454288.52279183.852275.77839204.881267.9604 9278.52264.8347
  9320.6 251.1639373.242246.28919426.194222.18629521.508160.05529809.914105.5843
9895.99675.6442410014.3849.94769 10055.366.4025410100.6265.9537910132.9675.11999
 10219.2117.320810316.22150.675510380.36193.558810433.68212.803510622.97217.7095
10840.23245.668310881.36256.817410943.04286.510911004.49296.353411135.91382.4484
#Mann= 3 , 0 , 0
8864.088    0.12       08864.088    0.12       011135.91    0.12       0
#XS Ineff= 2 , 0
       0                               0
Bank Sta=8864.088,11135.91
Exp/Cntr=0.3,0.1

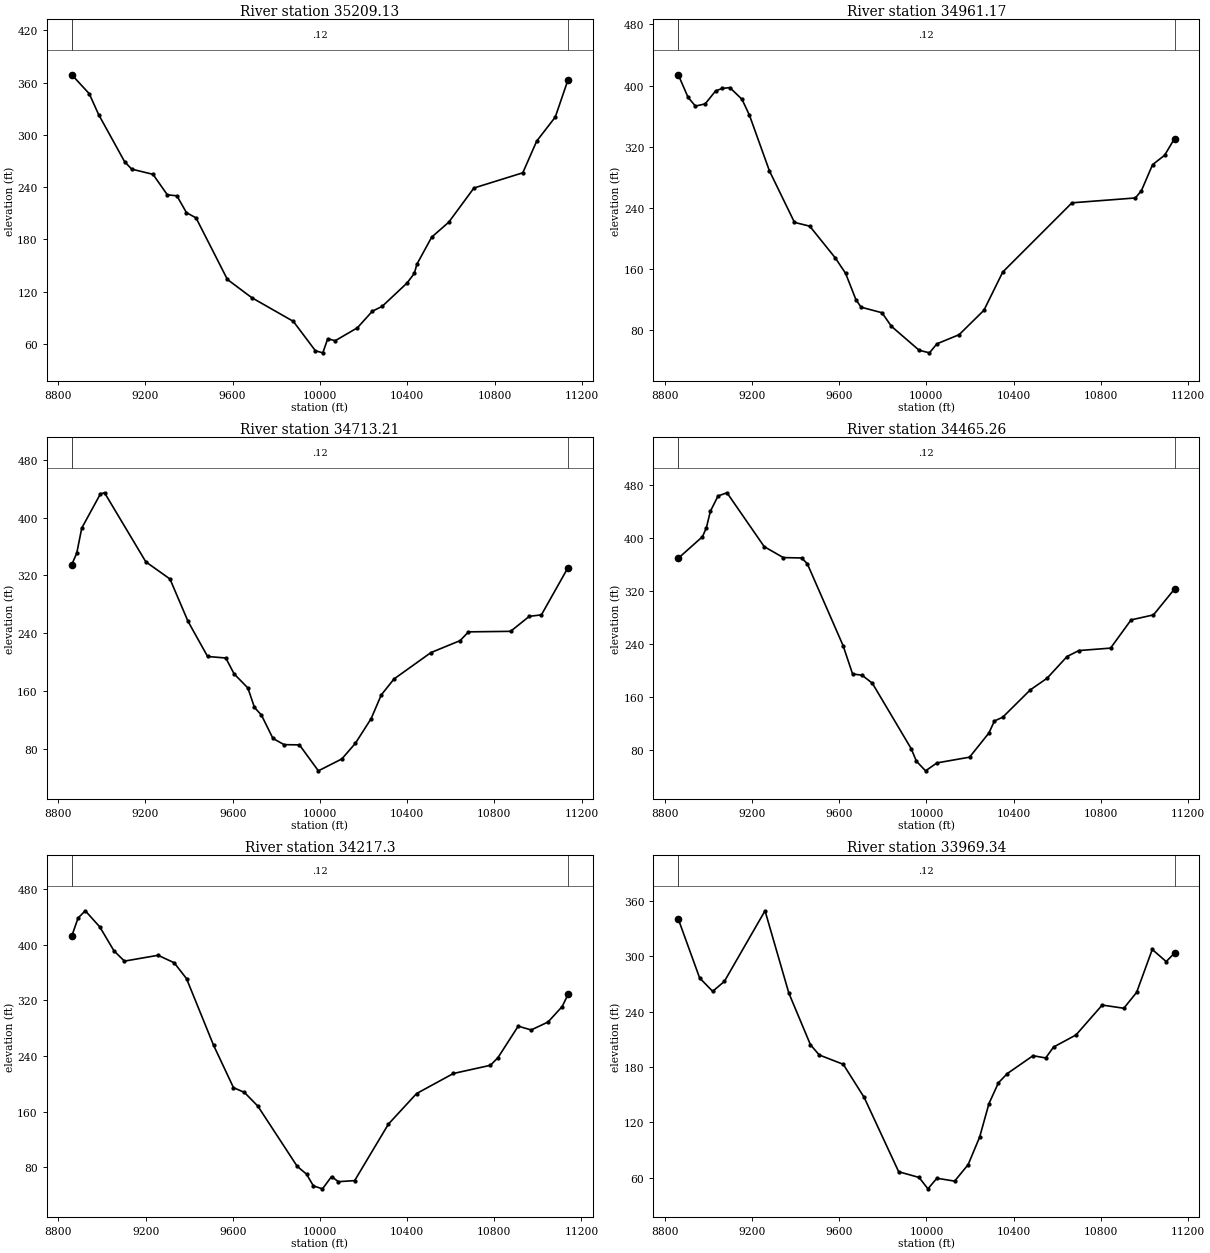
Type RM Length L Ch R = 1 ,35209.13,247.956300,247.956300,247.956300
XS GIS Cut Line= 6
667970.489161694862305.300027525668314.435446028862165.062098388
668626.219511595862022.117002403669630.898932696861503.947533141
669846.721954985861413.432906225670029.979450245861347.758202447
#Sta/Elev= 30
8863.101368.90158943.147347.14158986.119323.22019105.106269.16269137.623260.6138
9235.178254.64879300.877231.14229344.676230.00469388.475210.69539432.521204.6179
9576.221133.96519687.745 113.0839878.284 85.88269979.38852.1546210013.28 49.7749
10035.9666.0022910069.9863.6641710172.0378.5589210240.0697.5012110285.41103.1411
 10398.8129.785810432.82141.023310444.16151.361310512.19182.5755 10590.4199.7049
10705.73238.946710929.59256.408810993.49292.845811078.47320.358111136.87363.1861
#Mann= 3 , 0 , 0
8863.101    0.12       08863.101    0.12       011136.87    0.12       0
#XS Ineff= 2 , 0
       0                               0
Bank Sta=8863.101,11136.87
Exp/Cntr=0.3,0.1

Type RM Length L Ch R = 1 ,34961.17,247.956200,247.956200,247.956200
XS GIS Cut Line= 6
668154.612380953862621.355729291668467.208237907862461.103069247
668774.014096845862282.683751478669655.320774791861668.200581555
669836.213217831861556.200196827670085.827228656861428.673537888
#Sta/Elev= 30
8862.967414.21068908.105384.54448941.633373.28658986.337376.14379033.966393.1082
 9064.57396.38869099.523397.40869155.139382.0873 9189.12 361.3089280.615288.6173
9395.455221.17439465.421216.24639582.251174.82589629.693154.58969677.135120.1044
9700.856110.3007 9796.69103.0249 9839.74 85.27949966.76653.9705810014.1150.60261
10048.0862.3751410149.9874.3387110263.45106.184910350.05156.309310667.19 246.779
10957.87253.141710985.48262.696111036.56296.685711091.88309.031811137.05330.7446
#Mann= 3 , 0 , 0
8862.967    0.12       08862.967    0.12       011137.05    0.12       0
#XS Ineff= 2 , 0
       0                               0
Bank Sta=8862.967,11137.05
Exp/Cntr=0.3,0.1

Type RM Length L Ch R = 1 ,34713.21,247.956300,247.956300,247.956300
XS GIS Cut Line= 6
668365.511518251862894.061409546668671.259247801862706.286723749
669011.474709386862462.390065264669278.868121854862244.151705105
669813.822554207861757.353349828670165.690086906861511.482704203
#Sta/Elev= 30
8862.053335.16598884.635350.75348907.811385.65618993.579433.03329012.324434.4633
9201.597338.87789312.363315.10859395.277256.38529484.923  207.859568.436 205.763
9606.553183.78539669.644164.25479699.739137.45059731.904126.6766 9784.5694.48537
9835.85385.79288 9906.0885.518819992.96849.5691810100.5366.0313910163.0887.82532
10235.23121.982710281.48154.686310340.02176.764410509.15213.228710643.07 229.817
10681.45241.947610874.67242.669810960.25263.410611015.92265.493611137.96330.8892
#Mann= 3 , 0 , 0
8862.053    0.12       08862.053    0.12       011137.96    0.12       0
#XS Ineff= 2 , 0
       0                               0
Bank Sta=8862.053,11137.96
Exp/Cntr=0.3,0.1

Type RM Length L Ch R = 1 ,34465.26,247.956200,247.956200,247.956200
XS GIS Cut Line= 6
668569.847414042863146.649060231668987.173702052862843.768751475
669493.959660014862386.240721594669907.974942348861888.726908062
670077.183031703861727.157605414670232.887861095861607.526132205
#Sta/Elev= 30
8861.402  369.018972.543401.48478990.571415.19269008.599439.69259044.075462.8616
9084.955467.59649255.767386.48439343.356370.01529426.955369.42279453.186361.0102
9617.678237.47859661.248194.77269704.818192.86799752.049180.78099930.48282.09454
9954.08663.426689996.11148.8727410048.5560.8161510198.1269.4635210286.85105.8307
 10312.2123.956410350.23129.615610476.99170.836910553.75188.285110645.54221.0217
10699.62230.000210845.25233.679810939.25276.162311042.06283.728311138.58 322.635
#Mann= 3 , 0 , 0
8861.402    0.12       08861.402    0.12       011138.58    0.12       0
#XS Ineff= 2 , 0
       0                               0
Bank Sta=8861.402,11138.58
Exp/Cntr=0.3,0.1

Type RM Length L Ch R = 1 , 34217.3,247.956300,247.956300,247.956300
XS GIS Cut Line= 6
668921.792530118863401.727777673 669238.05782257863148.863552326
669474.834844654862899.094250119669856.466365682862119.652931346
 670038.17164621861887.799120498670306.298957406861648.606626601
#Sta/Elev= 30
8861.368 412.504 8890.19438.36648923.301448.77528989.996425.51249055.194391.0462
9102.976376.37219257.079 384.7479331.028374.06399387.821 351.2369511.986255.3432
9603.414194.35039653.404187.5337 9715.06167.84039895.76181.175389938.54269.97358
9970.13753.02009 10011.848.7919610053.4866.4319610084.7459.0862410159.4460.63213
10314.69142.0255 10443.7185.862610612.68214.728610782.72226.516210817.49237.6721
10910.05282.826510969.57277.327111046.77288.735711111.67310.952511138.65 328.351
#Mann= 3 , 0 , 0
8861.368    0.12       08861.368    0.12       011138.65    0.12       0
#XS Ineff= 2 , 0
       0                               0
Bank Sta=8861.368,11138.65
Exp/Cntr=0.3,0.1

Type RM Length L Ch R = 1 ,33969.34,247.956200,247.956200,247.956200
XS GIS Cut Line= 6
669167.374850609863481.721797384669756.375570524862932.056493652
 669850.85309722862767.860800484 670051.60867088862176.377098348
670232.243333824 861940.88617193670494.970409893861704.483653394
#Sta/Elev= 30
8861.149340.44828959.113276.60149019.017262.05719072.698272.82849259.308349.3637
9368.731260.09919467.842204.17599508.418193.08619618.416183.00089714.358 147.116
9872.76566.582039966.29160.3968610007.2348.0493810048.0159.5462910129.6356.41367
10191.7474.3294810244.34104.083710287.16 140.41610330.64162.949410371.36172.9475
10489.44192.309810547.68189.874610583.56201.652910686.93214.858810807.05247.2128
10906.11243.736210964.93260.925411036.76307.454311100.71294.312511138.86303.4924
#Mann= 3 , 0 , 0
8861.149    0.12       08861.149    0.12       011138.86    0.12       0
#XS Ineff= 2 , 0
       0                               0
Bank Sta=8861.149,11138.86
Exp/Cntr=0.3,0.1

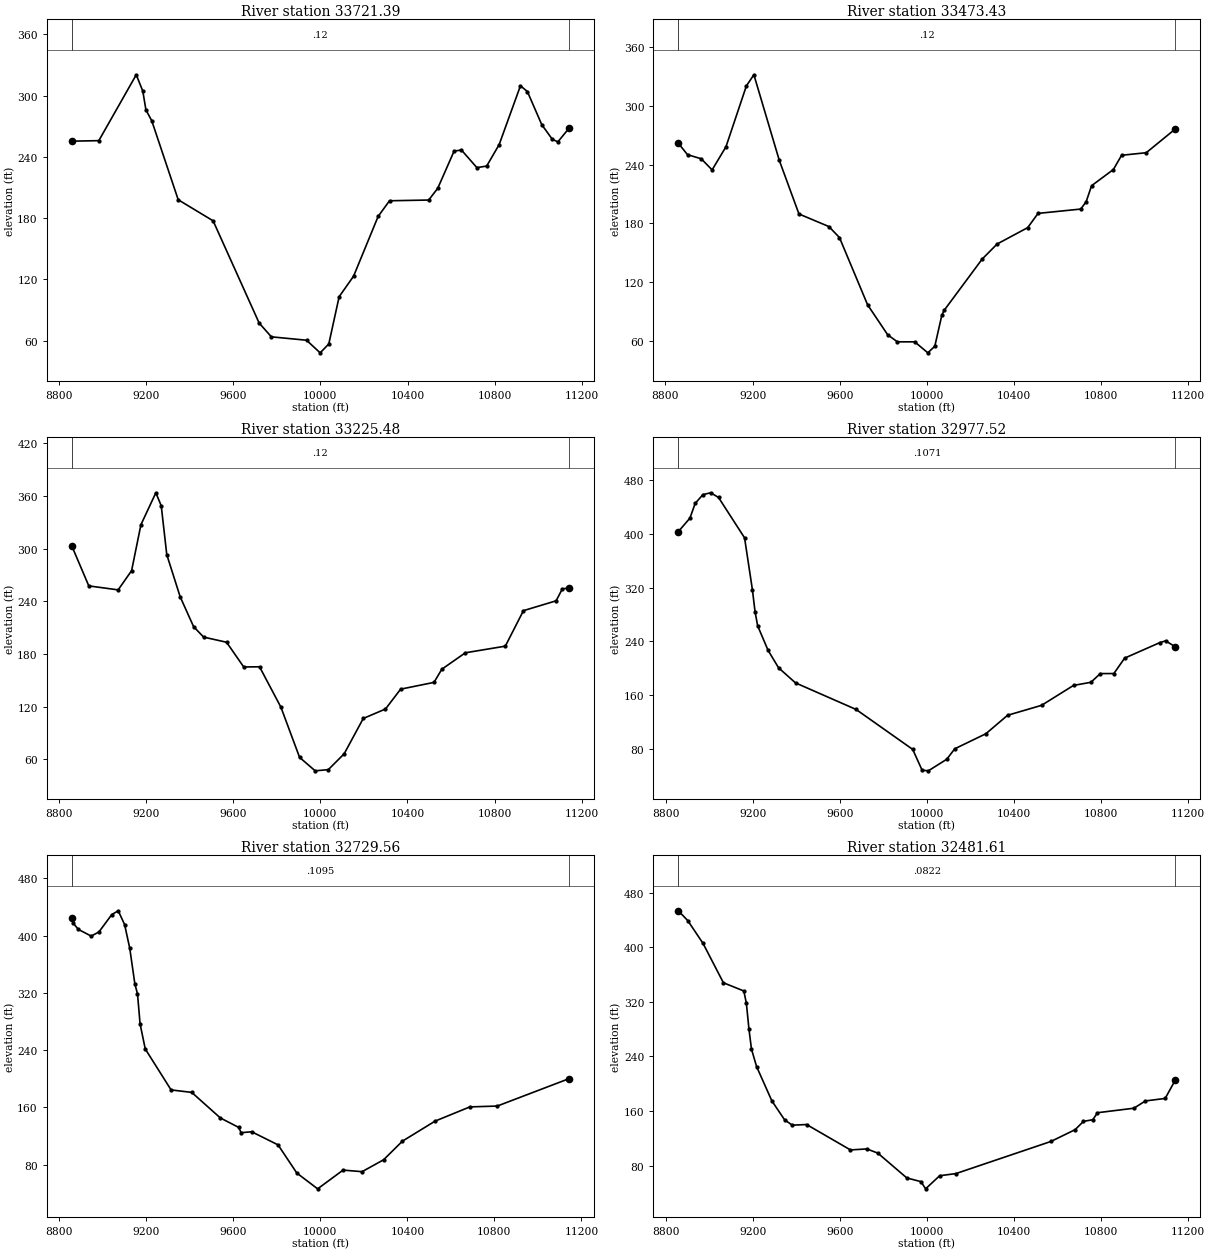
Type RM Length L Ch R = 1 ,33721.39,247.956300,247.956300,247.956300
XS GIS Cut Line= 6
669292.851955665863462.046440074669739.053448388863076.196335433
670067.193098544862712.437891196 670215.88877392862599.932211833
670681.501600762862164.711266788670975.020405959861928.185025652
#Sta/Elev= 30
  8859.2255.33368983.086255.84289154.873320.3632 9184.96304.37329199.318285.9613
9226.089275.29299347.506197.94539507.727177.29319718.96977.200029775.13363.67089
9936.47460.349129999.07447.99431 10038.756.6837710086.22102.997810152.43123.0701
10265.35181.694210317.42196.948810497.31197.667510538.82209.186510613.86245.6082
10647.42246.668510718.51229.414910763.36230.932810820.69251.967410918.46309.5974
10950.28303.928611016.28271.494211065.33256.973411090.49254.736411140.83267.8375
#Mann= 3 , 0 , 0
  8859.2    0.12       0  8859.2    0.12       011140.83    0.12       0
#XS Ineff= 2 , 0
       0                               0
Bank Sta=8859.2,11140.83
Exp/Cntr=0.3,0.1

Type RM Length L Ch R = 1 ,33473.43,247.956200,247.956200,247.956200
XS GIS Cut Line= 6
669281.305372446863556.391396157669940.550275184863035.846316862
670066.877993134862962.923663189670365.781840261862845.207625746
670557.126522977862745.188063286 671171.48128061862300.815561665
#Sta/Elev= 30
8858.971 261.7858901.225250.03938963.926245.91689014.087234.50859077.774258.1776
9171.575320.39549205.913331.6711 9322.28244.42349412.788  189.499550.182176.6603
9598.863165.37589728.029  96.6739820.40466.028399864.83858.905239944.18858.89378
10004.5647.6563210036.5354.40803 10068.5 85.861410079.1590.9897310254.25143.5146
10322.71 158.82310462.97175.549810510.52190.089610706.55194.506910731.45 202.058
10756.35218.399410856.34234.879810894.05249.455311007.18252.055711141.03276.3942
#Mann= 3 , 0 , 0
8858.971    0.12       08858.971    0.12       011141.03    0.12       0
#XS Ineff= 2 , 0
       0                               0
Bank Sta=8858.971,11141.03
Exp/Cntr=0.3,0.1

Type RM Length L Ch R = 1 ,33225.48,247.956300,247.956300,247.956300
XS GIS Cut Line= 6
 669301.43829129863729.683639996669963.101822421863260.707663297
670144.111513742863170.395555225670354.963218889863128.039119266
670514.667310505863053.433121772 671239.19010539862559.753307783
#Sta/Elev= 30
8858.182303.00018936.115 257.6049070.986253.06929132.726274.95339175.655327.3325
9244.206 363.673 9268.98348.81869294.275293.27999355.687245.3171 9417.62211.1796
9463.733199.27239569.052193.41639647.815165.26539720.535165.44939818.728119.4369
9904.44262.295349976.19246.93491 10036.448.2821310109.2366.3092610197.14106.6044
10299.21 117.37110368.62139.964710522.11147.704410557.89 162.66210665.98181.3933
10849.75 188.97210932.91229.389311083.02240.610611111.58254.1863 11141.8255.2467
#Mann= 3 , 0 , 0
8858.182    0.12       08858.182    0.12       0 11141.8    0.12       0
#XS Ineff= 2 , 0
       0                               0
Bank Sta=8858.182,11141.8
Exp/Cntr=0.3,0.1

Type RM Length L Ch R = 1 ,32977.52,247.956200,247.956200,247.956200
XS GIS Cut Line= 6
669500.224810868864001.704417986670182.355625426863541.395434092
670321.163609692863427.942620492670557.683502739863202.557577688
671028.446711009862869.123798819671330.780304111862642.302222588
#Sta/Elev= 30
8857.901403.70428911.375423.9055 8935.26445.78038971.088458.96659006.916461.6651
9042.745454.62829162.324394.41489198.411316.8964 9210.44 284.3079222.468263.2137
9270.584226.4292  9318.7200.51799396.381178.06039674.752138.42279934.99478.81352
 9978.0747.8466710006.7246.8396810091.3364.0957310128.1879.72682   10271102.1431
10370.86129.717610527.16144.577210673.98174.2789   10754178.956410797.12191.9242
10859.24 191.97310908.93215.0022 11071.5238.252411097.17240.7279 11142.1231.8375
#Mann= 3 , 0 , 0
8857.901  0.1071       08857.901  0.1071       0 11142.1  0.1071       0
#XS Ineff= 2 , 0
       0                               0
Bank Sta=8857.901,11142.1
Exp/Cntr=0.3,0.1

Type RM Length L Ch R = 1 ,32729.56,247.956300,247.956300,247.956300
XS GIS Cut Line= 6
669629.579635416 864148.62090667670120.969562246863836.366552715
670431.058840111863628.688285695670717.632306862863414.977165592
671151.706010834863097.363375666671494.716124848862830.664988494
#Sta/Elev= 30
8857.344424.89728863.748417.37128887.379408.75988946.457399.40918981.903405.1934
 9040.98429.44929070.665434.77059100.057415.43749123.688382.30949147.375332.0747
9159.254 318.7999171.133276.7059 9194.89241.78119313.679184.54679408.709181.0724
9540.086145.39059623.828132.30499635.792124.80119684.213 126.1019805.441107.7845
9891.81368.412029987.51246.3703110104.3972.5519110191.75 70.341210290.63 86.9354
10377.14112.936410527.59140.995610687.35160.833610813.18161.998611142.66200.1999
#Mann= 3 , 0 , 0
8857.344  0.1095       08857.344  0.1095       011142.66  0.1095       0
#XS Ineff= 2 , 0
       0                               0
Bank Sta=8857.344,11142.66
Exp/Cntr=0.3,0.1

Type RM Length L Ch R = 1 ,32481.61,247.956200,247.956200,247.956200
XS GIS Cut Line= 6
669717.987108473864293.336764727670443.806941632863853.868412959
670828.032731279863677.499756752670978.053052137863592.092004723
671255.292667927 863390.41955937671641.081873774863072.936484402
#Sta/Elev= 30
8856.508453.40028899.915439.02618970.279 405.5619063.893347.93399157.918335.8479
9169.645317.85259181.372 280.284  9193.1 250.6979216.555225.11719286.919174.7901
9345.556146.99869380.738139.21569446.745140.14659648.522102.93059723.821 104.417
 9774.4698.242519907.78761.87137 9972.7556.458919994.23545.9109610058.8765.11621
10133.5268.2495110571.06115.374710682.04132.614310720.63144.773110763.73147.2485
10784.94157.450910952.79164.074811005.38174.7096 11096.5 178.40111143.46205.5321
#Mann= 3 , 0 , 0
8856.508  0.0822       08856.508  0.0822       011143.46  0.0822       0
#XS Ineff= 2 , 0
       0                               0
Bank Sta=8856.508,11143.46
Exp/Cntr=0.3,0.1