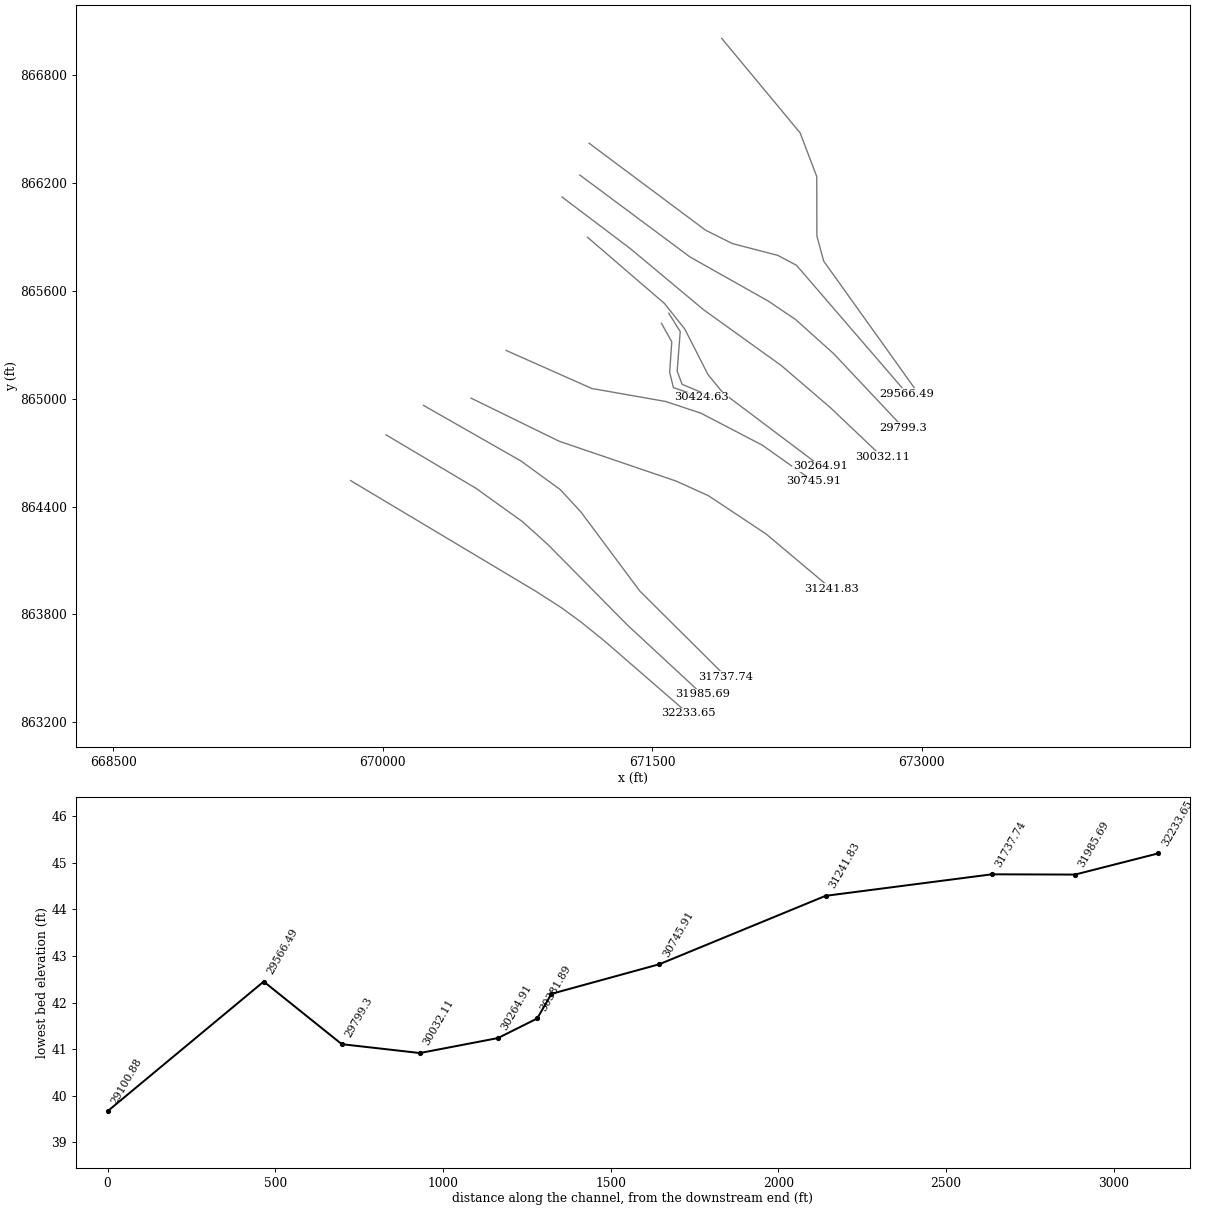
HEC-RAS study 13716_ras.prj: 13716

--- 13716_ras.g01 (geometry) --- (continued)

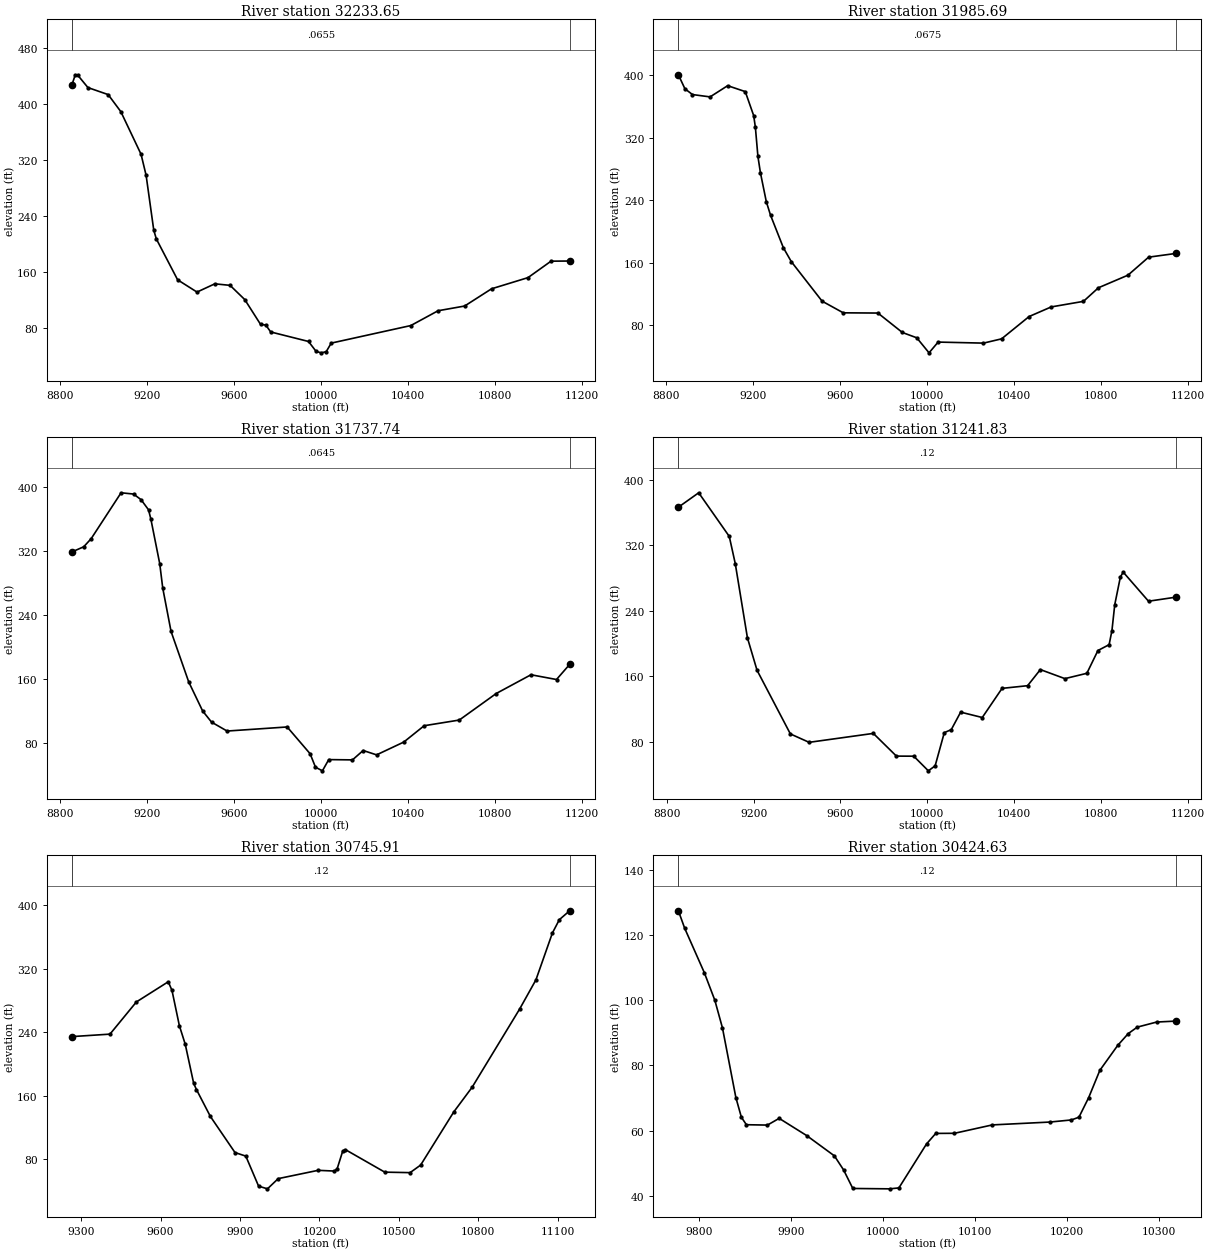
Type RM Length L Ch R = 1 ,32233.65,247.956300,247.956300,247.956300
XS GIS Cut Line= 6
669821.524978429864544.333160423670850.780441901863929.287062156
670995.038857766863836.812730585 671105.66387226863755.706740211
671231.831584661863653.975357027671699.102107589863248.753895462
#Sta/Elev= 30
8855.897  426.798871.567441.46048883.196440.8027 8929.71423.22839022.739413.2274
9080.882388.97869173.911328.21119197.218298.1734  9232.3 220.1279243.993207.6598
9342.013149.26279431.093131.7952 9512.95143.54199583.112141.37659650.674121.1103
9723.43785.669719747.46184.800229769.89874.967139943.79161.398939978.569 47.2727
10001.7445.2039610024.98 46.814110048.2259.0689310414.0284.0844610539.37105.1962
10661.34111.894710785.07136.454910952.69152.3883 11058.6 175.84611144.07176.0573
#Mann= 3 , 0 , 0
8855.897  0.0655       08855.897  0.0655       011144.07  0.0655       0
#XS Ineff= 2 , 0
       0                               0
Bank Sta=8855.897,11144.07
Exp/Cntr=0.3,0.1

Type RM Length L Ch R = 1 ,31985.69,247.956200,247.956200,247.956200
XS GIS Cut Line= 6
670018.923482632864798.894411071670519.761342703864501.180938647
670778.417194857864315.626481712670921.794213609864186.265001211
671358.567537383863743.901516581671778.434567029863354.437913663
#Sta/Elev= 30
8855.626400.85218885.775382.89698920.461375.53289001.393372.52519082.326386.8859
9163.258379.29679201.904348.56819209.647333.82519221.325296.45349233.004275.2407
9259.983238.33539279.342221.07379338.237179.45719374.726161.61199516.502110.9269
9613.84295.995659773.13495.702469885.67670.799389951.77264.0205810008.2244.74909
10049.9558.5279510258.5857.19747 10341.9 62.679110468.3391.2478510570.11103.5567
10718.27110.677710787.14128.0988   10923144.225711017.82 167.26711144.39172.0929
#Mann= 3 , 0 , 0
8855.626  0.0675       08855.626  0.0675       011144.39  0.0675       0
#XS Ineff= 2 , 0
       09734.315                       0
Bank Sta=8855.626,11144.39
Exp/Cntr=0.3,0.1

Type RM Length L Ch R = 1 ,31737.74,495.912500,495.912500,495.912500
XS GIS Cut Line= 6
670227.618344881864962.671977807670770.665688297864652.893783175
670988.832981578864493.677936035671103.371246555864369.847271237
671431.297914385863929.598255006671909.974609969863453.852673538
#Sta/Elev= 30
 8855.53318.69698909.858325.13358944.256335.30149081.848392.74859139.178391.1532
9173.576384.16669207.974371.50459218.679360.00059259.558304.06679273.477273.3973
9311.641 219.2089392.908156.01739456.922  119.679497.802105.72959569.28694.55603
9845.53999.664229950.96866.200159975.86949.3128910007.6544.7547610036.8358.82079
10145.96 58.464510195.0470.2049810256.7864.74355 10381.880.7600110475.56101.2117
 10637.1108.3189 10806.9141.527910966.79165.005611084.15159.050211144.52177.9075
#Mann= 3 , 0 , 0
 8855.53  0.0645       0 8855.53  0.0645       011144.52  0.0645       0
#XS Ineff= 2 , 0
       09808.907                       0
Bank Sta=8855.53,11144.52
Exp/Cntr=0.3,0.1

Type RM Length L Ch R = 1 ,31241.83,495.912500,495.912500,495.912500
XS GIS Cut Line= 6
670492.179166997865003.059198155670982.968001254864762.983862454
671632.467905551864541.811634118671812.965438037864460.111281057
672133.718552928864247.429564708672498.566218741  863940.7762377
#Sta/Elev= 30
8853.394366.44698947.037384.08839087.883330.78119115.553297.48299171.508206.8527
9215.848167.16159369.43589.40114 9455.6979.127779751.57190.041219857.90762.29712
9937.78462.1908810005.1244.2922210036.3750.4420210078.52 90.962110110.7194.67635
10153.87116.025410253.46109.470610344.67145.083210462.31148.344310521.11168.0308
10634.16156.9746 10735.3163.485210786.32191.319810837.84198.454910850.82215.6138
10863.81247.337110889.79281.240410902.91287.083511019.35 251.577 11146.6 256.575
#Mann= 3 , 0 , 0
8853.394    0.12       08853.394    0.12       0 11146.6    0.12       0
#XS Ineff= 2 , 0
       09738.867                       0
Bank Sta=8853.394,11146.6
Exp/Cntr=0.3,0.1

Type RM Length L Ch R = 1 ,30745.91,321.284000,321.284000,321.284000
XS GIS Cut Line= 6
670687.314878019865268.557516331671164.198473422865056.770666183
671575.297032069864984.488071732671771.710174031 864919.24927834
672112.590180323864741.564749519672396.622579591864540.941382117
#Sta/Elev= 30
9264.865 234.6029408.831237.71039508.613278.25739629.045303.66869643.092292.9258
9671.125248.3288 9693.27224.98489725.258175.60879735.774167.78599788.338133.9763
9881.24488.555349922.14584.043359970.45646.2149310003.9842.8217610044.5455.67684
10195.3966.1331710256.9365.2229910267.3868.1609210288.27 90.277110298.7192.18098
10447.2463.8510410542.9563.2266910582.7972.7679310708.05139.747710777.51 170.893
10956.61  269.17 11018.5306.133211080.71365.148911106.85381.869511145.79393.1124
#Mann= 3 , 0 , 0
9264.865    0.12       09264.865    0.12       011145.79    0.12       0
#XS Ineff= 2 , 0
       0                10302.23       0
Bank Sta=9264.865,11145.79
Exp/Cntr=0.3,0.1

Type RM Length L Ch R = 1 ,30424.63,42.737300,42.737300,42.737300
XS GIS Cut Line= 5
671551.651702553 865419.64024967671609.125936955865316.447874278
671597.369843572865146.637636274671618.269565135865061.732517287
671775.017477185865008.176980659
#Sta/Elev= 30
9777.306127.39359784.187122.02799805.511108.44629816.95799.987619825.29191.46171
 9839.85  70.1569845.84264.129439851.29661.834929874.18961.723299886.94563.78399
9916.92458.499249946.99652.29742 9957.0247.983999967.04442.2977710007.1442.18669
10017.1642.4691510047.23 55.945210057.2659.1714310077.6359.2061310118.8261.77828
10181.3362.6510510204.8363.2991410213.0364.14284 10223.670.1413310235.7678.50375
 10255.3 86.184510266.6989.7692710276.4491.7397310297.5793.2982410318.7393.59567
#Mann= 3 , 0 , 0
9777.306    0.12       09777.306    0.12       010318.73    0.12       0
#XS Ineff= 2 , 0
       0                 10299.3       0
Bank Sta=9777.306,10318.73
Exp/Cntr=0.3,0.1

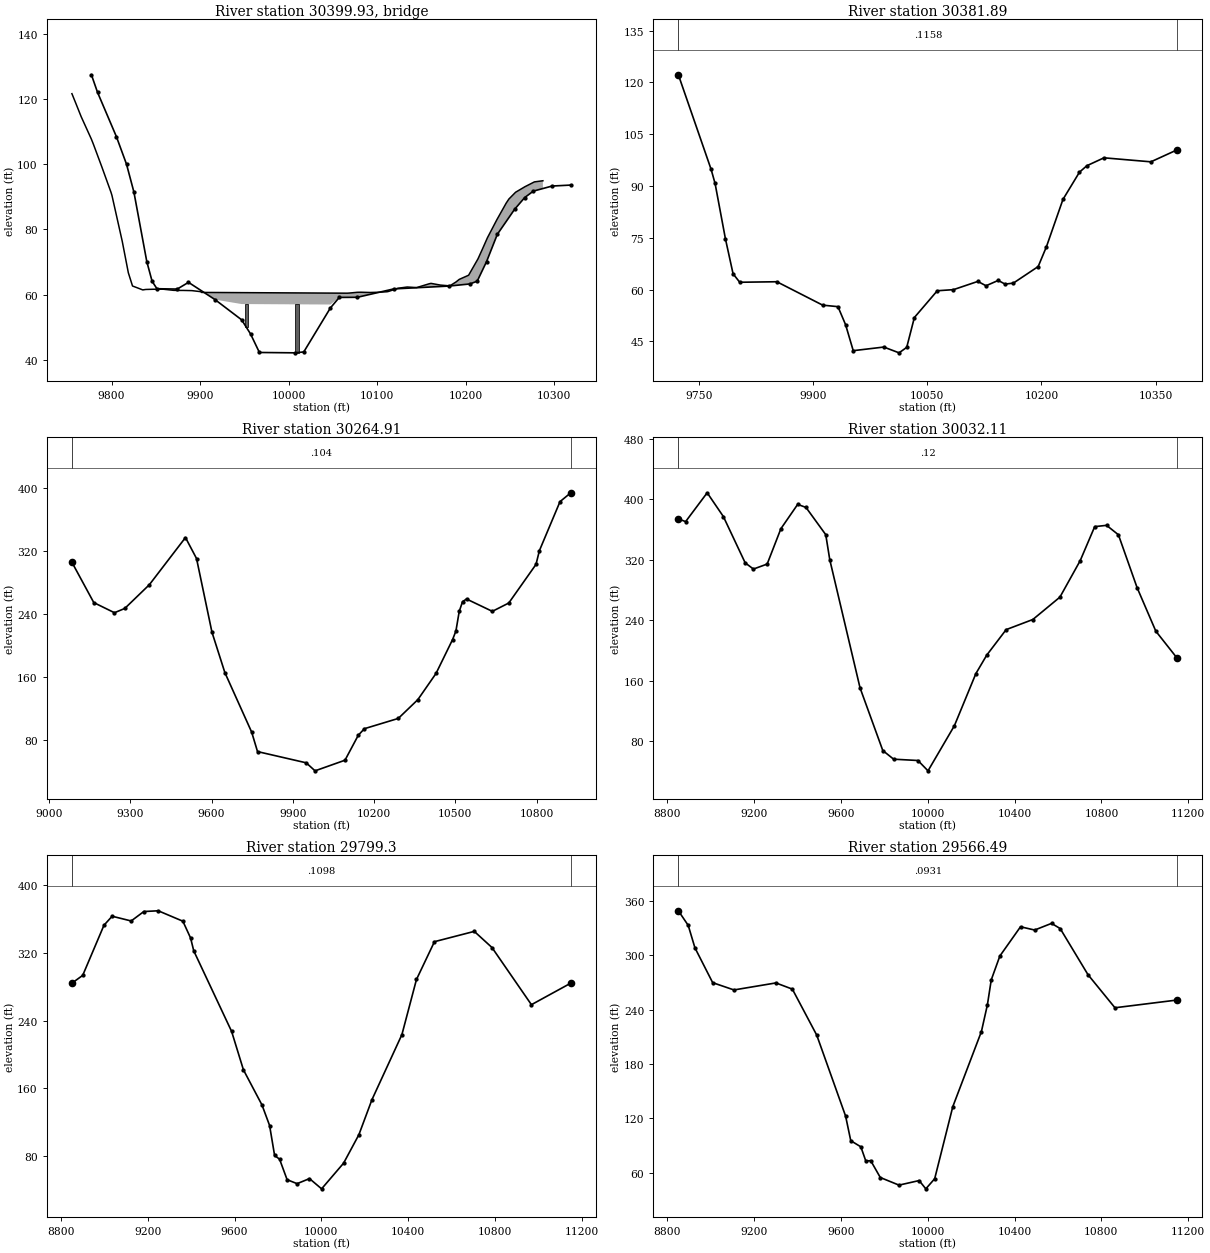
Type RM Length L Ch R = 3 ,30399.93,,,
BEGIN DESCRIPTION:
END DESCRIPTION:
Bridge Culvert--1,0,-1,-1, 0
Deck Dist Width WeirC Skew NumUp NumDn MinLoCord MaxHiCord MaxSubmerge Is_Ogee
8.737450,25.262400,2.6,0, 58, 58, , , 0.95, 0, 0,0,,
 9755.29 9759.93 9765.68 9777.28 9779.62 9788.89 9799.31 9800.50 9812.11 9819.00
 9823.72 9835.32 9838.70 9846.93 9858.39 9858.54 9870.15 9874.70 9880.79 9890.81
 9897.37 9897.37 9900.82 9901.6110064.3610064.3610066.6610069.0210071.1810077.65
10081.6510092.1310102.6010111.3210113.0710123.5410134.0210144.4910144.9810152.69
10159.1710160.8710171.4910182.1010189.0510192.7110203.3210213.9310218.9310224.55
10235.1610245.7710248.8110256.3810266.9910277.6110278.6910287.23
  121.60  118.49  114.59  107.66  106.06   99.30   91.47   90.43   76.38   66.73
   62.67   61.47   61.61   61.67   61.68   61.68   61.34   61.31   61.31   61.25
   61.04   61.04   60.93   60.70   60.47   60.47   60.47   60.52   60.57   60.74
   60.76   60.68   60.76   60.91   61.02   61.98   62.36   62.18   62.21   62.85
   63.38   63.47   62.95   62.71   63.90   64.69   65.97   71.00   73.99   77.44
   82.95   88.07   89.32   91.40   93.10   94.57   94.61   94.92
 -878.40 -881.51 -885.41 -892.34 -893.94 -900.70 -908.53 -909.57 -923.62 -933.27
 -937.33 -938.53 -938.39 -938.33 -938.32 -938.32 -938.66 -938.69 -938.69 -938.75
 -938.96   57.54   57.43   57.20   56.97 -939.53 -939.53 -939.48 -939.43 -939.26
 -939.24 -939.32 -939.24 -939.09 -938.98 -938.02 -937.64 -937.82 -937.79 -937.15
 -936.62 -936.53 -937.05 -937.29 -936.10 -935.31 -934.03 -929.00 -926.01 -922.56
 -917.05 -911.93 -910.68 -908.60 -906.90 -905.43 -905.39 -905.08
 9755.29 9759.93 9765.68 9777.28 9779.62 9788.89 9799.31 9800.50 9812.11 9819.00
 9823.72 9835.32 9838.70 9846.93 9858.39 9858.54 9870.15 9874.70 9880.79 9890.81
 9900.82 9901.61 9902.46 9902.4610066.6610069.0210069.4510069.4510071.1810077.65
10081.6510092.1310102.6010111.3210113.0710123.5410134.0210144.4910144.9810152.69
10159.1710160.8710171.4910182.1010189.0510192.7110203.3210213.9310218.9310224.55
10235.1610245.7710248.8110256.3810266.9910277.6110278.6910287.23
  121.60  118.49  114.59  107.66  106.06   99.30   91.47   90.43   76.38   66.73
   62.67   61.47   61.61   61.67   61.68   61.68   61.34   61.31   61.31   61.25
   60.93   60.70   60.70   60.70   60.47   60.52   60.53   60.53   60.57   60.74
   60.76   60.68   60.76   60.91   61.02   61.98   62.36   62.18   62.21   62.85
   63.38   63.47   62.95   62.71   63.90   64.69   65.97   71.00   73.99   77.44
   82.95   88.07   89.32   91.40   93.10   94.57   94.61   94.92
 -878.40 -881.51 -885.41 -892.34 -893.94 -900.70 -908.53 -909.57 -923.62 -933.27
 -937.33 -938.53 -938.39 -938.33 -938.32 -938.32 -938.66 -938.69 -938.69 -938.75
 -939.07 -939.30 -939.30   57.20   56.97   57.02   57.03 -939.47 -939.43 -939.26
 -939.24 -939.32 -939.24 -939.09 -938.98 -938.02 -937.64 -937.82 -937.79 -937.15
 -936.62 -936.53 -937.05 -937.29 -936.10 -935.31 -934.03 -929.00 -926.01 -922.56
 -917.05 -911.93 -910.68 -908.60 -906.90 -905.43 -905.39 -905.08
Pier Skew, UpSta & Num, DnSta & Num=  ,9952.37, 2 ,9957.46, 2 , 0 , 0 , 0 ,,
    4.00    4.00
 -939.37   60.63
    4.00    4.00
 -939.38   60.62
Pier Skew, UpSta & Num, DnSta & Num=  ,10009.37, 2 ,10014.45, 2 , 0 , 0 , 0 ,,
    4.00    4.00
 -939.45   60.55
    4.00    4.00
 -939.46   60.54
BR Coef=-1 , 0 , 0 ,, 0 ,,,0.8,0,1,0,
WSPro=,,,, 1 ,,,, 0 ,,,, 0 ,,,,-1 ,-1 ,-1 , 0 , 0 , 0 , 0 , 0
BC Design=,, 0 ,, 0 ,,,,,,

Type RM Length L Ch R = 1 ,30381.89,116.978700,116.978700,116.978700
XS GIS Cut Line= 6
671592.144913137865475.808251485671656.150310546865373.922108695
671639.169286758865153.168799266671666.600171357865080.019773677
671788.079803169865029.076702267671888.659713387865005.564515471
#Sta/Elev= 30
9723.366122.22669766.331 94.83659771.55890.739669785.12974.719199795.17764.56517
9803.92862.107569852.63662.257059912.80855.473919932.86655.037599942.89649.80846
9952.92642.282899993.04643.3323910013.1141.6563910023.1443.2482910033.1751.88813
10063.2659.64578 10084.559.9667310116.5462.3566910127.2261.0926610143.2262.63541
10152.3361.5648310163.1761.86906 10195.7 66.659110206.54  72.39910228.2386.11113
10249.9294.0104410259.6395.8752710282.05 98.165210343.6797.0049610378.24100.4929
#Mann= 3 , 0 , 0
9723.366  0.1158       09723.366  0.1158       010378.24  0.1158       0
#XS Ineff= 2 , 0
       0                10284.64       0
Bank Sta=9723.366,10378.24
Exp/Cntr=0.3,0.1

Type RM Length L Ch R = 1 ,30264.91,232.806200,232.806200,232.806200
XS GIS Cut Line= 6
671140.587985453865898.103498878671568.158733193865530.437596038
671681.887875841865387.063532822671810.299293899865134.792221542
671893.405562513865033.270977282672435.671889898864625.047588932
#Sta/Elev= 30
9084.568306.09029165.315254.88949241.612242.01869279.761247.46319370.544277.6153
9503.882337.49089544.691310.85819601.596217.37749649.249166.05249748.24390.41227
9769.86565.686379949.71151.416919982.29741.2356310092.8854.7265910142.0686.48838
10164.63 94.761210289.62107.787310361.84131.643510428.97164.902710490.21207.9841
10502.44218.809410514.66243.692310526.89256.0496 10541.6259.442910636.93243.7697
 10697.6 254.34210798.19303.410210810.67320.827710886.83383.107210926.61394.3412
#Mann= 3 , 0 , 0
9084.568   0.104       09084.568   0.104       010926.61   0.104       0
#XS Ineff= 2 , 0
       0                10223.24       0
Bank Sta=9084.568,10926.61
Exp/Cntr=0.3,0.1

Type RM Length L Ch R = 1 ,30032.11,232.806100,232.806100,232.806100
XS GIS Cut Line= 6
670998.090005674866122.745022029671380.148903481865833.953031143
671786.638706398865494.662831411672217.965986551865185.009854643
 672492.65281366864949.538826452672780.631121026864676.078429227
#Sta/Elev= 30
8850.616374.08088884.046370.37438983.429408.50389057.967377.09319158.573315.8578
9196.532307.67959259.797314.26089323.062360.98949400.356 393.1569438.678389.1539
9529.802353.12719548.297320.01149687.794150.60699792.68367.733159842.66656.30958
9954.63154.57813   1000140.9141310122.57100.565810221.64169.512310271.69193.9078
10361.07227.583510484.05 240.97810608.84270.561110702.08318.6598 10769.1363.7423
10823.74365.461810878.38352.985410964.39283.115211050.76 225.54911149.39189.6903
#Mann= 3 , 0 , 0
8850.616    0.12       08850.616    0.12       011149.39    0.12       0
#XS Ineff= 2 , 0
       0                               0
Bank Sta=8850.616,11149.39
Exp/Cntr=0.3,0.1

Type RM Length L Ch R = 1 , 29799.3,232.806200,232.806200,232.806200
XS GIS Cut Line= 6
671097.193011929866245.012454386671709.836423101865789.282651004
672146.879302813865542.865125803672298.817912258865440.208048176
672509.562923108865251.143161769672898.021280968864838.486917654
#Sta/Elev= 30
8850.336284.41818900.081293.64398998.056352.94029035.674 363.6069123.448357.9972
9181.855369.16969248.154 370.0539361.694357.71519397.328337.8107 9411.85322.6457
9586.292227.36919640.826181.88469726.384140.30039761.407116.02069784.46480.64684
9807.52176.133859842.10651.92072 9888.2247.230879945.32153.2136410001.0841.10438
10102.5171.5007810172.95105.148310233.21146.602610371.22223.537910438.36288.7678
10521.27333.493810704.81345.682410786.33326.583810968.16258.951511149.63284.4458
#Mann= 3 , 0 , 0
8850.336  0.1098       08850.336  0.1098       011149.63  0.1098       0
#XS Ineff= 2 , 0
       0                               0
Bank Sta=8850.336,11149.63
Exp/Cntr=0.3,0.1

Type RM Length L Ch R = 1 ,29566.49,465.612300,465.612300,465.612300
XS GIS Cut Line= 6
671149.019086443866421.674368085671797.757807083865937.448729734
 671947.04343155865863.153317254672199.274694229865797.546966849
672303.037871702 865742.58728261672918.682798812865028.270450212
#Sta/Elev= 30
8850.132 348.7498895.588332.66448926.511307.94149008.332269.55619106.516261.5464
9299.854269.27129375.653 262.444    9488211.77719621.126122.5666 9644.8795.48292
9691.371 88.74469714.344 73.04549736.82773.499719781.06554.92368 9867.2246.54232
9960.13351.565969990.83242.4495410031.7553.5777210115.32133.005610247.21215.7493
10274.78245.199810292.55272.653810332.23298.933610427.42331.123410492.67327.5394
10570.48334.867810610.34329.161110738.56278.333210862.75241.916711149.87250.4552
#Mann= 3 , 0 , 0
8850.132  0.0931       08850.132  0.0931       011149.87  0.0931       0
#XS Ineff= 2 , 0
       0                               0
Bank Sta=8850.132,11149.87
Exp/Cntr=0.3,0.1

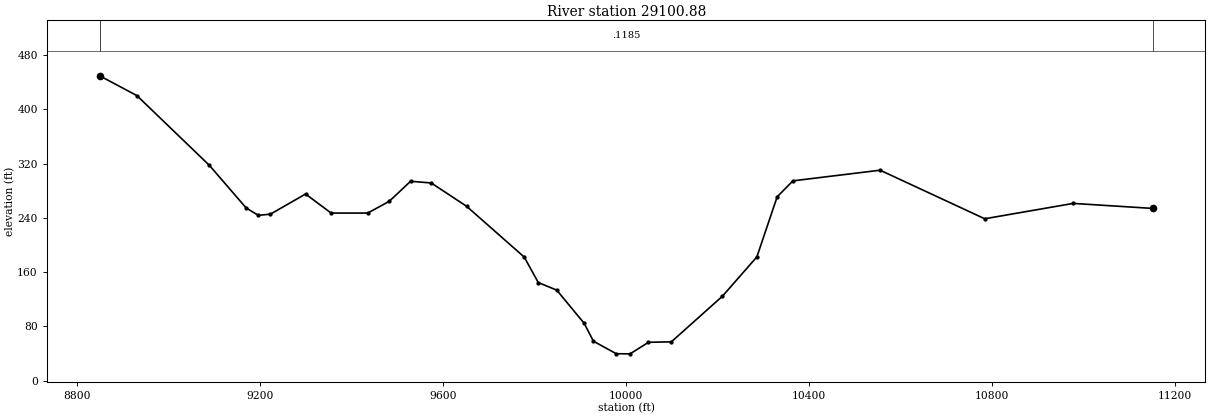
Type RM Length L Ch R = 1 ,29100.88,232.806200,232.806200,232.806200
XS GIS Cut Line= 6
671886.810818555867005.561391494672323.340015856866479.529768978
672415.924315279866236.469645765672416.739331061865905.646615017
672454.409186914865765.816402363 672963.68190112865053.665635911
#Sta/Elev= 30
8849.075449.34468930.485420.15089089.175317.24139169.227254.68679195.911243.6992
9222.463245.47029299.204275.15359355.071247.0728 9434.94247.04679481.996264.3071
9528.714293.90839573.875 291.4069651.084 257.1079777.182182.22159807.842144.6834
9848.252133.53599908.34284.481739928.35158.281929978.45939.7805110008.5839.66343
10048.7156.6550410098.7757.3648410210.51124.6558 10285.6182.451410330.02271.0318
10364.47294.545610555.08310.217510783.71238.658310977.08261.307211150.98253.9052
#Mann= 3 , 0 , 0
8849.075  0.1185       08849.075  0.1185       011150.98  0.1185       0
#XS Ineff= 2 , 0
       0                               0
Bank Sta=8849.075,11150.98
Exp/Cntr=0.3,0.1