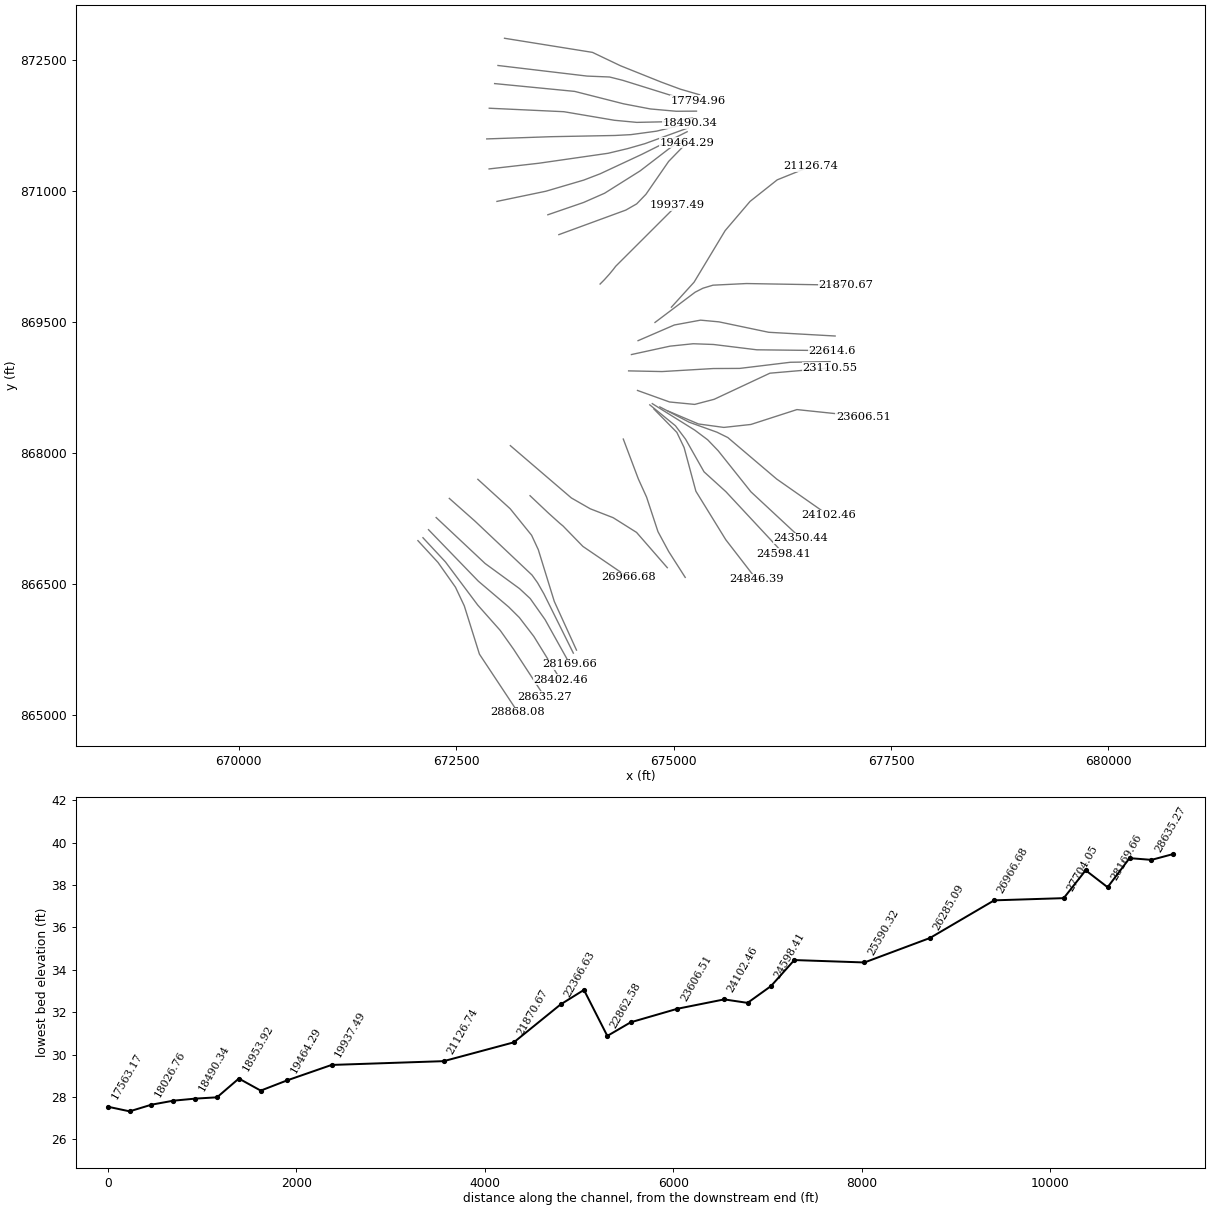
HEC-RAS study 13716_ras.prj: 13716

--- 13716_ras.g01 (geometry) --- (continued)

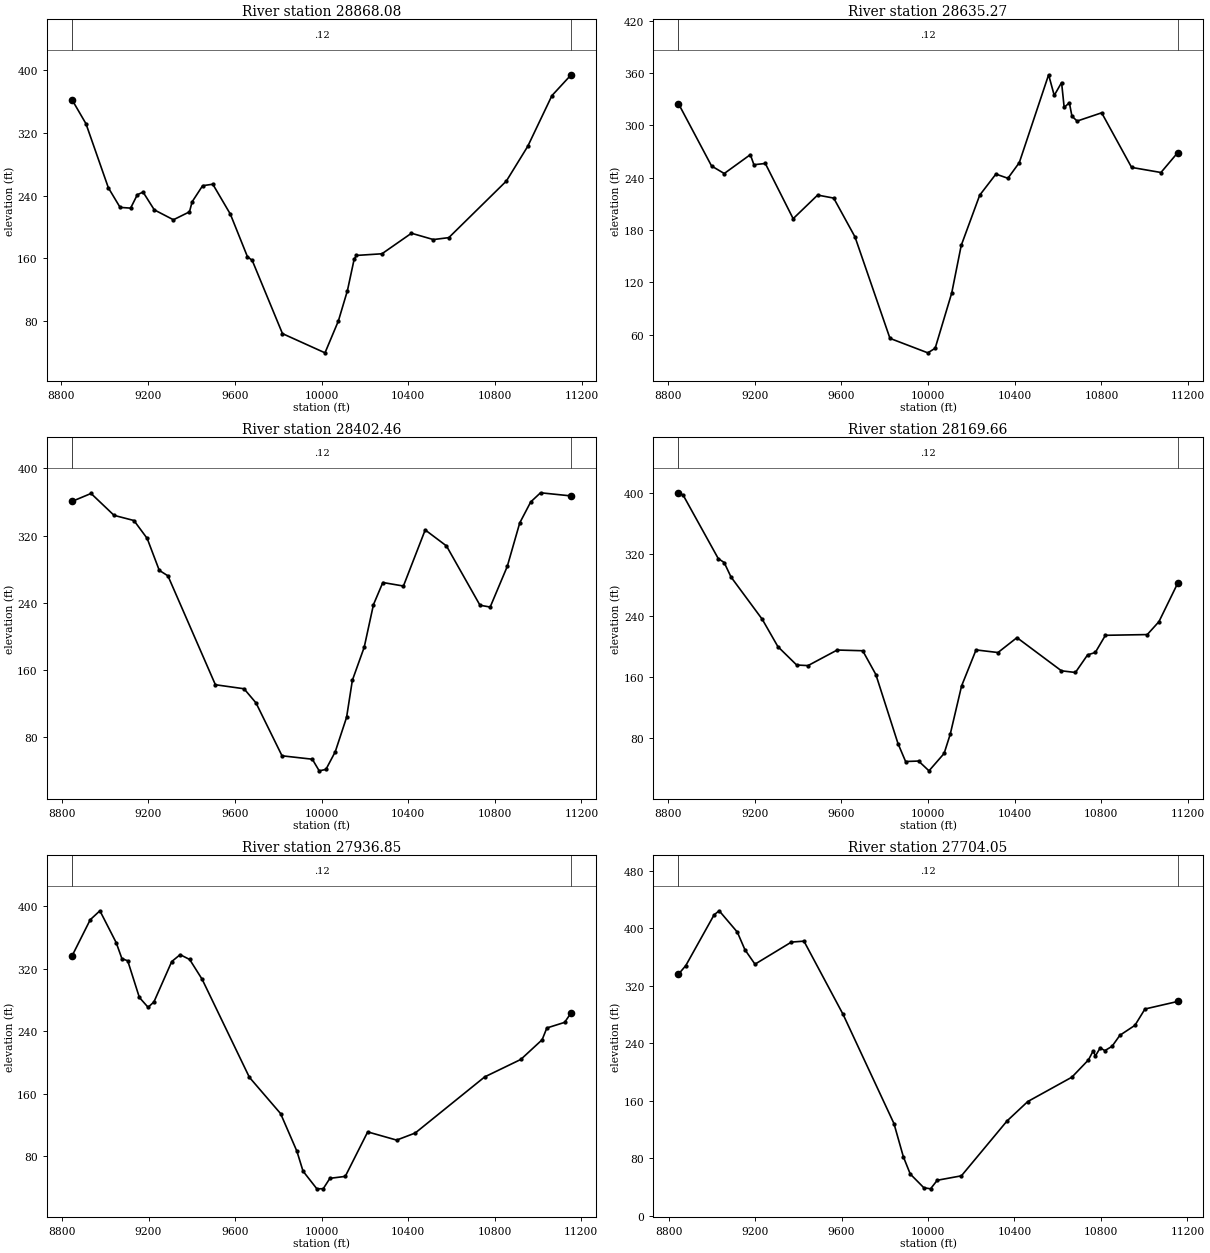
Type RM Length L Ch R = 1 ,28868.08,232.806200,232.806200,232.806200
XS GIS Cut Line= 6
672059.572205278866995.309993294672290.730057212866745.646868892
672491.506171534866462.347822468672592.935483942866248.629127702
672766.822887885865696.555403772673207.899966583865033.551188372
#Sta/Elev= 30
8848.861362.44618913.474331.73349016.874249.95349070.944224.96359119.466224.0398
9150.382241.11129176.861244.50659228.661221.82749316.886209.1875 9390.93219.2957
 9403.04 232.0659451.478252.61999498.504254.51769579.471216.33829658.165162.0986
9680.273157.35279819.749 63.991510015.91 39.468610077.7180.2082910119.25118.7306
 10150.4158.929310161.01163.695210278.53165.808710414.64192.005510515.66183.9422
10586.87186.394210852.48258.625410950.83302.804211062.49367.538511151.13394.1042
#Mann= 3 , 0 , 0
8848.861    0.12       08848.861    0.12       011151.13    0.12       0
#XS Ineff= 2 , 0
       0                               0
Bank Sta=8848.861,11151.13
Exp/Cntr=0.3,0.1

Type RM Length L Ch R = 1 ,28635.27,232.806100,232.806100,232.806100
XS GIS Cut Line= 6
672117.513647313867028.690352908672376.497141605866751.395164482
672747.029199276866258.583113351673006.400547178865967.473933274
673158.643890529865753.995470906 673517.20627607 865207.48189275
#Sta/Elev= 30
8848.803324.96789001.696253.37219060.177244.74159180.537 266.3719197.012254.8075
9249.566256.27429377.998192.97659490.913220.03889565.022216.56599663.232172.0556
9824.50355.78637    9999 39.191110032.9344.4488710109.33107.781410153.07162.2782
10238.43219.932110313.13244.103510368.42239.288510421.04257.235110556.18357.9261
10582.09334.279910615.98349.016410627.94320.506510651.86325.852810663.82310.4346
10687.74304.869710800.84314.335410938.91251.752511074.28245.907111151.22268.5394
#Mann= 3 , 0 , 0
8848.803    0.12       08848.803    0.12       011151.22    0.12       0
#XS Ineff= 2 , 0
       0                               0
Bank Sta=8848.803,11151.22
Exp/Cntr=0.3,0.1

Type RM Length L Ch R = 1 ,28402.46,232.806200,232.806200,232.806200
XS GIS Cut Line= 6
672181.338215714867120.811320149672754.266373762866531.467028162
673104.532605857866235.329508972673226.330376417866114.924486239
673392.546095879865899.243163986673698.536439962865405.563318214
#Sta/Elev= 30
8847.211360.65168935.443 370.1699041.691344.0679 9133.53337.89029194.663316.5475
 9250.55278.43869290.549271.89719509.718141.98249641.956137.18949697.247120.3336
9817.43557.209499957.40853.141449989.14639.2724510020.2140.9778810063.2261.97305
10115.61103.085110142.38147.357410196.97186.677410239.79  237.5910283.08 263.948
10378.12 259.73610478.71326.658110576.97307.5726 10731.7236.840110778.76234.6623
 10857.6 283.05510915.28335.0121 10966.1360.1011 11011.4370.986911152.78 367.224
#Mann= 3 , 0 , 0
8847.211    0.12       08847.211    0.12       011152.78    0.12       0
#XS Ineff= 2 , 0
       0                               0
Bank Sta=8847.211,11152.78
Exp/Cntr=0.3,0.1

Type RM Length L Ch R = 1 ,28169.66,232.806100,232.806100,232.806100
XS GIS Cut Line= 6
672269.265426176867259.646263149672832.596082905866733.522392635
 673227.81101457866446.425602711673350.667781849866332.888794512
673521.851018473866091.424952294673806.885030119865582.260411434
#Sta/Elev= 30
8846.415399.73718867.773396.9317 9030.66314.06489057.808309.00259089.508290.1358
9233.999235.04399306.244199.49679392.939175.60969445.408174.84979580.154195.1138
 9698.19 194.177 9758.85163.25439861.15273.455999896.34350.033659956.391 50.6447
10004.4537.9003310074.3360.5334710102.6485.5446410155.03148.338310221.91195.2598
 10323.3191.854710411.01211.235510616.55168.072610681.19 165.89710737.31188.7552
10773.07191.942610819.78214.2729 11013.2215.2179 11067.2232.016111153.56281.8489
#Mann= 3 , 0 , 0
8846.415    0.12       08846.415    0.12       011153.56    0.12       0
#XS Ineff= 2 , 0
       0                               0
Bank Sta=8846.415,11153.56
Exp/Cntr=0.3,0.1

Type RM Length L Ch R = 1 ,27936.85,232.806200,232.806200,232.806200
XS GIS Cut Line= 6
672420.626347659867478.784791651672715.414857119867218.885388567
673371.980674432866601.446286183673435.010479609866513.881392489
673507.749926929866387.480358929 673846.70160655865708.190655325
#Sta/Elev= 30
8846.072335.85638930.623382.36838975.305393.81629050.728353.07829077.007 332.742
9103.931 329.9519157.778283.14339198.164270.53159225.088 277.4199307.537329.0106
9346.321337.78339390.339331.59719447.895306.36169666.345181.15889810.663134.7921
9885.96886.784839914.45261.270899978.41238.6982810007.7238.8430510038.5452.10367
10109.6554.5953810213.33111.425510347.11100.945410432.88109.970310754.18181.6623
   10921203.931911019.71229.082811041.46244.1392 11123.7251.298211153.89263.5765
#Mann= 3 , 0 , 0
8846.072    0.12       08846.072    0.12       011153.89    0.12       0
#XS Ineff= 2 , 0
       0                               0
Bank Sta=8846.072,11153.89
Exp/Cntr=0.3,0.1

Type RM Length L Ch R = 1 ,27704.05,737.368000,737.368000,737.368000
XS GIS Cut Line= 6
672748.853226712867696.983310542673120.924744066867360.095508371
673366.950567802 867056.78600357673443.929701038866891.726346462
673627.620529696866300.261179515673883.067754589865742.565263753
#Sta/Elev= 30
8845.297335.7967 8879.52347.93799010.374418.4828 9033.87424.10559117.896394.4159
 9152.83370.02899199.523349.82969367.922380.55289426.099381.87099607.039280.0184
 9842.39128.22489885.75582.128819917.78757.998779980.50638.9684610011.7137.38483
10042.6649.3146910154.4655.4885110365.77131.867910461.39158.775510665.44192.6677
10742.26 216.72310763.63228.978510774.56222.296110796.41233.378210818.26 229.643
10851.24235.575310887.66250.949510957.28264.805611003.69287.503211154.76297.9728
#Mann= 3 , 0 , 0
8845.297    0.12       08845.297    0.12       011154.76    0.12       0
#XS Ineff= 2 , 0
       0                               0
Bank Sta=8845.297,11154.76
Exp/Cntr=0.3,0.1

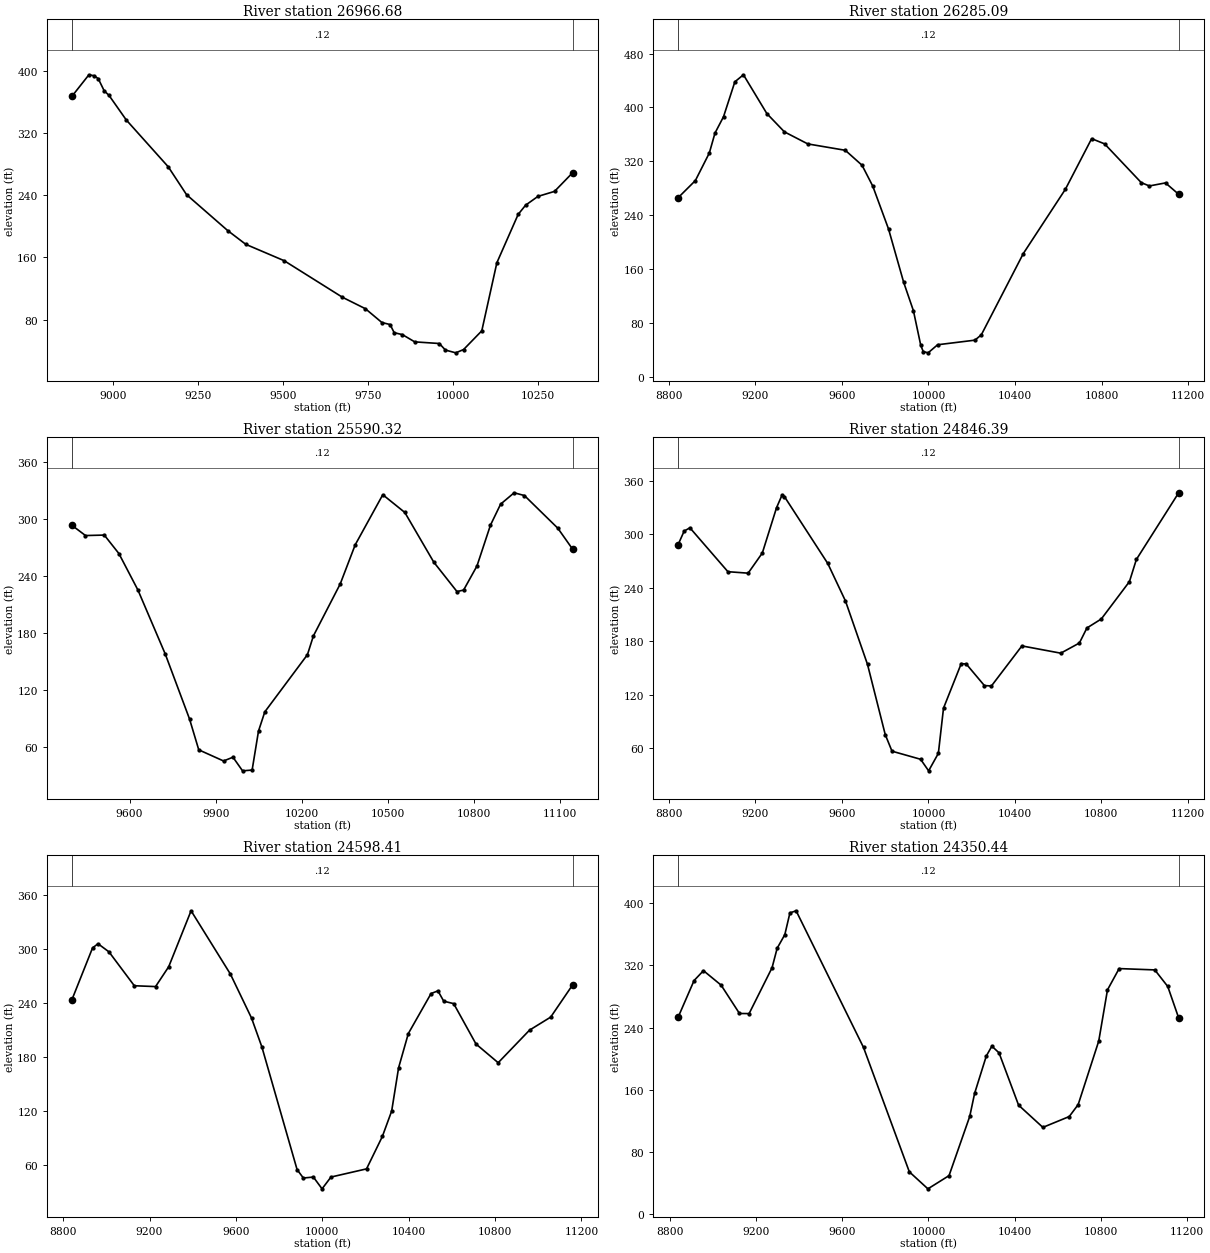
Type RM Length L Ch R = 1 ,26966.68,681.588000,681.588000,681.588000
XS GIS Cut Line= 6
673348.763510972867509.680357531673561.292682111867309.894855618
673690.994811177867193.788660511673728.101526231867163.226735204
673956.835395098866929.254686117674479.296332598866575.250779867
#Sta/Elev= 30
8880.493367.06718930.226394.60398945.727393.34198957.676389.60638974.927374.1842
8989.527367.99639040.024336.57429163.546276.34799217.422240.50619338.215 194.471
9391.544176.72229504.336155.71359675.996108.65249743.478 93.95649791.79676.26081
9815.95473.642149828.03363.165139852.19260.70238 9888.4351.380859960.87849.26843
9978.70540.8475210009.2237.2815110032.1941.5493410085.6765.5605810130.02153.0634
10192.63215.170110214.57227.053110250.81238.3128 10299.6244.756210352.63268.6323
#Mann= 3 , 0 , 0
8880.493    0.12       08880.493    0.12       010352.63    0.12       0
#XS Ineff= 2 , 0
       0                               0
Bank Sta=8880.493,10352.63
Exp/Cntr=0.3,0.1

Type RM Length L Ch R = 1 ,26285.09,694.768800,694.768800,694.768800
XS GIS Cut Line= 6
 673122.46393044868082.562036408 673824.10110639867483.890434527
674040.946759501867360.036156283674304.888354398867257.947756179
 674573.98916308867089.384699564674927.114075007866686.031855301
#Sta/Elev= 30
8843.837265.8907  8923.4291.32228987.885332.28319014.111361.9388 9053.45386.1407
9105.903438.0469  9145.5448.46459253.628  390.879334.723363.7007 9442.85345.7805
9616.036336.31459693.387314.09039742.994 283.0499815.719219.45319885.555 140.385
9930.787 97.95939964.71146.504879976.01937.411549998.63635.50478 10042.547.50634
10214.7954.3372710244.3762.2481710438.38182.981610632.63278.398810754.03353.6057
10813.93345.840810983.31288.264211020.61283.352311095.21287.876211156.09270.9529
#Mann= 3 , 0 , 0
8843.837    0.12       08843.837    0.12       011156.09    0.12       0
#XS Ineff= 2 , 0
       0                               0
Bank Sta=8843.837,11156.09
Exp/Cntr=0.3,0.1

Type RM Length L Ch R = 1 ,25590.32,743.929800,743.929800,743.929800
XS GIS Cut Line= 6
  674421.3289436868157.806704032674594.360721988867701.178544017
674689.177368583867493.223172665 674819.75036098867098.848512142
674942.964007824866871.077098391675133.276321873866574.904973738
#Sta/Elev= 30
9399.393293.11569446.411282.41199511.894282.89969562.747263.4507 9629.16224.9348
9724.337157.50449808.95288.984149841.07556.502839927.46744.752369960.306 48.7231
9993.68734.3502410027.0535.1760910049.2876.3096810071.2596.5253110219.82156.8279
10240.57176.5964   10334231.361510386.28272.651510482.37325.452410559.21306.7269
10660.11254.328410740.88223.359710763.96224.924410810.51250.287110857.62293.4037
10892.96315.511610940.08327.495210975.91324.583111092.23290.160411143.65268.1293
#Mann= 3 , 0 , 0
9399.393    0.12       09399.393    0.12       011143.65    0.12       0
#XS Ineff= 2 , 0
       0                               0
Bank Sta=9399.393,11143.65
Exp/Cntr=0.3,0.1

Type RM Length L Ch R = 1 ,24846.39,247.976500,247.976500,247.976500
XS GIS Cut Line= 6
674772.496074519868502.489011189675037.080570524868234.255687827
675120.712664344868060.275464664 675255.99481115867560.726206907
675600.028958746867005.427695683675949.849011107866555.094720904
#Sta/Elev= 30
8842.489288.65948870.428303.86258896.991307.48659072.669258.18829166.201 256.536
9231.896279.19729297.734330.15049322.908344.1872 9333.95342.5973 9534.54267.4456
9616.423225.28419718.383154.02339800.35975.187549831.63956.539129963.85547.45869
   1000134.4639810046.0754.1246410069.89104.906710151.75 154.88610175.03154.5008
10258.92130.269210291.45 129.79110432.46174.805210612.23166.649510698.31178.0568
 10733.1194.939810799.64205.065210929.86247.068310961.82271.894111157.59 346.846
#Mann= 3 , 0 , 0
8842.489    0.12       08842.489    0.12       011157.59    0.12       0
#XS Ineff= 2 , 0
       0                               0
Bank Sta=8842.489,11157.59
Exp/Cntr=0.3,0.1

Type RM Length L Ch R = 1 ,24598.41,247.976600,247.976600,247.976600
XS GIS Cut Line= 6
674725.984146804868549.252552168675020.624448701868310.170065219
675137.389693164868156.336795997675349.523699551867782.989760113
675600.940115211867555.720217485676266.841636784866844.338264288
#Sta/Elev= 30
8840.942243.47498936.134300.78288961.444305.38379012.096296.38329129.493258.7582
9227.865257.82249288.797279.8756  9392.4342.00089574.423271.74649672.598222.7516
9720.286190.7923 9883.3354.61032 9912.2945.248619958.803 46.3104    999933.23492
 10040.246.3170910205.03 55.407310278.2791.4077710321.37119.612210353.44167.6673
10398.54205.679710503.78250.078910535.65253.095810562.44241.618910608.57238.8921
10712.05194.018310814.68173.267310959.79209.444411057.86223.935511159.12259.5923
#Mann= 3 , 0 , 0
8840.942    0.12       08840.942    0.12       011159.12    0.12       0
#XS Ineff= 2 , 0
       0                               0
Bank Sta=8840.942,11159.12
Exp/Cntr=0.3,0.1

Type RM Length L Ch R = 1 ,24350.44,247.976600,247.976600,247.976600
XS GIS Cut Line= 6
674754.530759026868563.186028093675242.879943874868260.123996077
675391.399841599868149.619000308675511.924299502868024.595270863
675888.791946672867554.129412265676463.311411896867022.436665405
#Sta/Elev= 30
8839.853253.26638913.664300.43788957.255313.17489039.052294.56179124.234258.0652
9168.872257.93829275.267316.96379298.911342.05189334.376359.5024 9358.02387.4969
 9386.73390.22499699.114 214.4049911.52554.34156 9997.68 32.443510095.6449.44233
10191.63125.667410214.08155.187710268.39203.346410294.13216.031810327.29207.4613
10418.04140.1074 10530.6111.5193 10652.8125.449910694.24140.829210789.54222.5574
10830.06288.4242 10884.1315.848511049.38314.141911109.47292.834911160.17252.2803
#Mann= 3 , 0 , 0
8839.853    0.12       08839.853    0.12       011160.17    0.12       0
#XS Ineff= 2 , 0
       0                               0
Bank Sta=8839.853,11160.17
Exp/Cntr=0.3,0.1

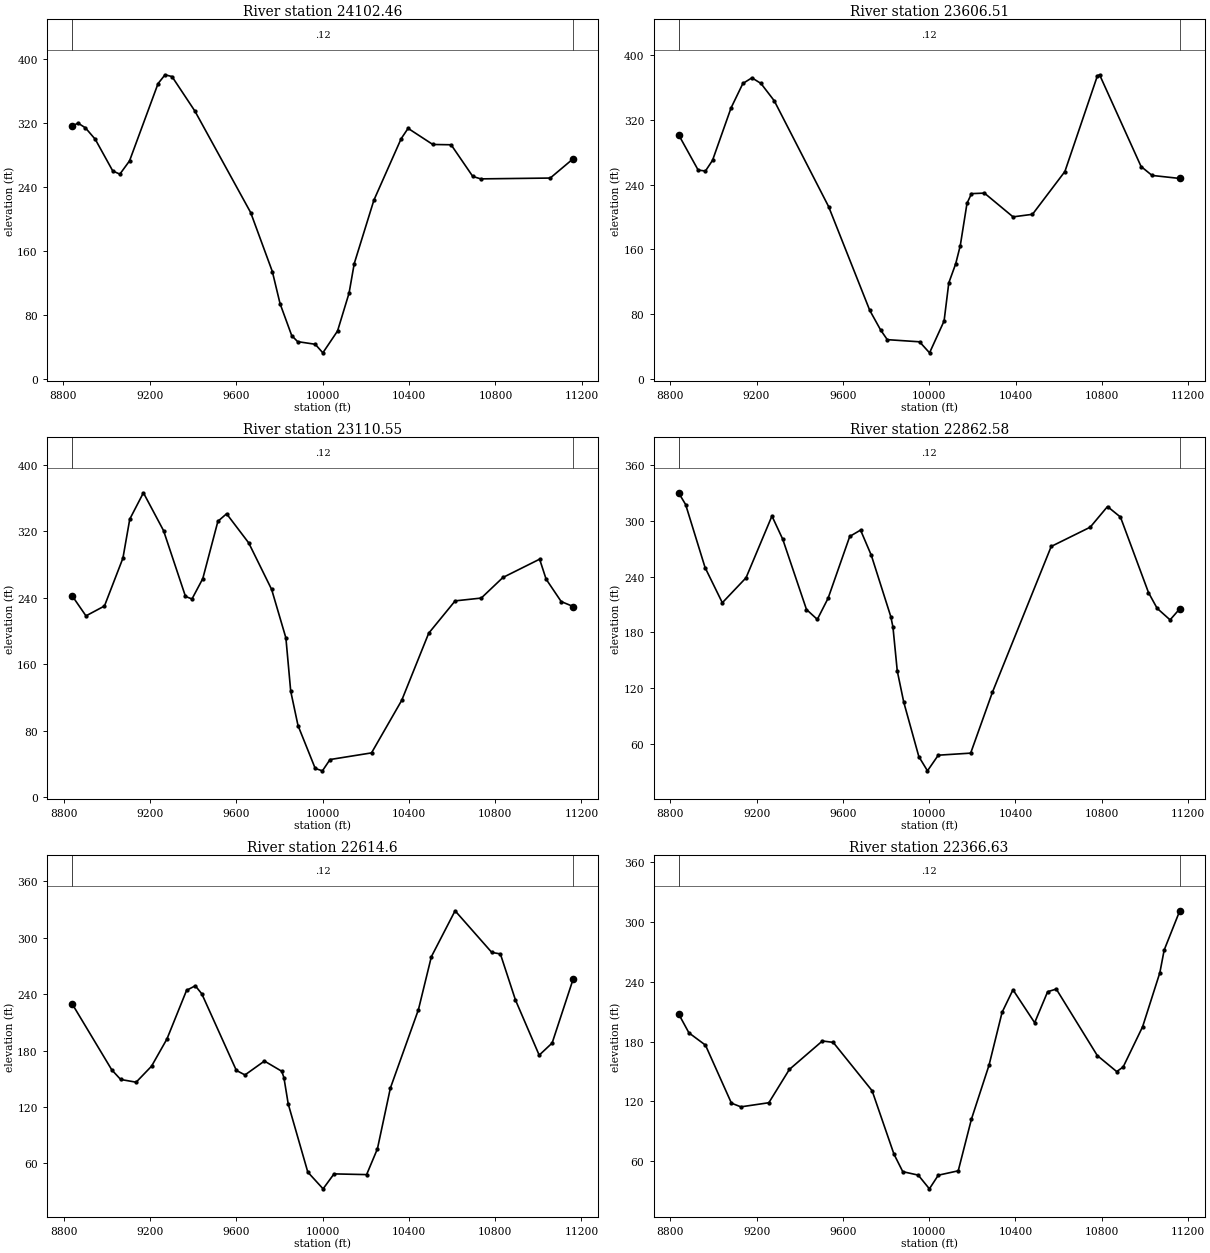
Type RM Length L Ch R = 1 ,24102.46,495.953200,495.953200,495.953200
XS GIS Cut Line= 6
674840.967536971868526.025234751675179.458178226868350.284390251
675498.415089568868236.385290446675623.134286467 868175.15899349
676184.909261255 867700.34588314676779.917579756867285.917221776
#Sta/Elev= 30
8839.637315.78788867.074 319.8398901.324313.94088946.991 299.649  9028.3259.9378
9061.091255.99369105.831272.57319237.984369.24459270.353 380.2139302.575377.9618
9408.584334.80759666.791207.97799767.059134.28169802.86894.081419856.95454.09602
9884.35946.61663 9965.7743.31512   1000132.6076810069.0259.9133810122.45107.3702
10146.36144.204410237.47 223.55610363.59300.307610395.66313.242910510.09293.0836
10594.91292.723410695.33253.120310732.09250.075411053.85251.107811160.44 275.322
#Mann= 3 , 0 , 0
8839.637    0.12       08839.637    0.12       011160.44    0.12       0
#XS Ineff= 2 , 0
       0                               0
Bank Sta=8839.637,11160.44
Exp/Cntr=0.3,0.1

Type RM Length L Ch R = 1 ,23606.51,495.953200,495.953200,495.953200
XS GIS Cut Line= 6
674934.399559322868479.280137624675285.699198456868330.626799866
675577.167251123868291.141014645    675888.44267868324.918498384
676418.124186778868495.143078349677181.007615885868415.548199983
#Sta/Elev= 30
8838.873301.9269 8929.52258.20188963.259256.98128996.174270.20799081.853334.9395
9136.715365.24429178.669372.23989220.472365.30359282.116343.86969533.919213.0642
9724.691 84.6767 9775.3560.267749805.88848.478259955.41945.8118510001.6932.16641
10069.0271.5466610090.88118.691210122.83142.260910144.04164.743110175.23217.0603
10196.03229.026310255.94229.685810388.52200.311810478.61203.466410628.71256.3564
10779.42374.724710789.49376.008310981.76262.577511032.55251.549811161.11  247.81
#Mann= 3 , 0 , 0
8838.873    0.12       08838.873    0.12       011161.11    0.12       0
#XS Ineff= 2 , 0
       0                               0
Bank Sta=8838.873,11161.11
Exp/Cntr=0.3,0.1

Type RM Length L Ch R = 1 ,23110.55,247.976600,247.976600,247.976600
XS GIS Cut Line= 6
674584.728001657868714.049539739674953.262731342868582.225956635
675241.989887842868554.491234022675466.191003795868612.889949129
676107.297904786868911.626704263  676800.8453952868971.288220418
#Sta/Elev= 30
8838.255242.37838902.818218.03928988.513229.91349074.136287.52019105.872334.4844
9169.107366.20449262.419320.67799364.157241.45849394.259238.3745 9444.35262.8822
9514.434331.89199554.725340.93669657.269305.86649763.571249.85189829.613 191.527
9851.994127.36889885.80186.065119965.63934.38574    999931.5274510034.2245.12521
10226.62 53.135910366.65116.431110491.66197.173910614.26236.095710735.34239.4842
10835.72264.251811005.86286.280111035.86262.290411105.88235.274411161.74229.2783
#Mann= 3 , 0 , 0
8838.255    0.12       08838.255    0.12       011161.74    0.12       0
#XS Ineff= 2 , 0
       0                               0
Bank Sta=8838.255,11161.74
Exp/Cntr=0.3,0.1

Type RM Length L Ch R = 1 ,22862.58,247.976500,247.976500,247.976500
XS GIS Cut Line= 6
674482.367506924  868938.1080832674867.214992625 868930.29148084
675456.253184504868964.925332059675759.523237557868966.364986334
676342.097039489869036.604530162676800.011751211869044.297132343
#Sta/Elev= 30
8838.158330.18198870.829317.52778960.936249.71339040.966211.81219150.973238.7157
9271.022305.17569321.072280.17139431.204204.50099481.327193.88939531.449216.7133
9631.694283.20369681.816290.01819731.908262.75259822.032196.90969832.035185.6459
9852.041138.3465 9882.05104.84969952.06446.178519992.06830.8839510042.0847.72093
10192.3349.9514110293.19 115.49310565.81272.432610746.59293.149410826.73 315.356
10886.76304.063711016.78222.761111056.79205.822611116.81193.375411161.84205.3259
#Mann= 3 , 0 , 0
8838.158    0.12       08838.158    0.12       011161.84    0.12       0
#XS Ineff= 2 , 0
       0                               0
Bank Sta=8838.158,11161.84
Exp/Cntr=0.3,0.1

Type RM Length L Ch R = 1 , 22614.6,247.976600,247.976600,247.976600
XS GIS Cut Line= 6
674514.970096591869125.003444358674958.607114759869221.124810389
675225.026103116  869248.6238359675458.991629218 869240.18814813
675956.867523127869179.327477966676822.798065541869169.583915982
#Sta/Elev= 30
8837.944229.81259022.283159.4638 9063.33149.28549135.162146.36849206.618163.3967
9278.025192.30319369.087244.0041  9409.5248.84599439.667 240.2849599.928158.8876
9639.928154.09429730.052168.84879810.291158.01659820.358151.35589840.493123.1643
9931.20950.8359210002.0933.0545410052.7648.9461110203.9148.1743310254.0375.55995
10314.14140.129710444.19223.4776 10504.2279.7602 10614.2328.5457 10784.2284.3228
 10824.2282.6857 10894.2233.716411004.21175.096711064.25188.009311162.11256.2658
#Mann= 3 , 0 , 0
8837.944    0.12       08837.944    0.12       011162.11    0.12       0
#XS Ineff= 2 , 0
       0                               0
Bank Sta=8837.944,11162.11
Exp/Cntr=0.3,0.1

Type RM Length L Ch R = 1 ,22366.63,495.953200,495.953200,495.953200
XS GIS Cut Line= 6
674591.129033278869283.805936624675008.421830939869463.384644773
675309.986880448869518.713852254675521.720149226869499.045235271
676093.719607972869379.771098347676857.372486028869337.123587532
#Sta/Elev= 30
8837.488207.92998885.527188.84168962.178176.5444 9082.63118.3396 9126.43114.6168
9256.197118.75739351.271152.11839504.631180.71389554.795179.30629735.214130.8016
9836.58467.194549877.45649.606659949.33646.1269410000.9332.3685310042.2346.04601
10134.7950.4543910196.21102.425710277.59156.400410338.24 209.49910388.74232.0687
10489.28199.030410549.47 230.10110589.56232.815310779.81166.104110869.89150.0022
10899.92154.638410990.01194.969711070.08249.2176 11090.1271.921411162.54311.3271
#Mann= 3 , 0 , 0
8837.488    0.12       08837.488    0.12       011162.54    0.12       0
#XS Ineff= 2 , 0
       0                               0
Bank Sta=8837.488,11162.54
Exp/Cntr=0.3,0.1

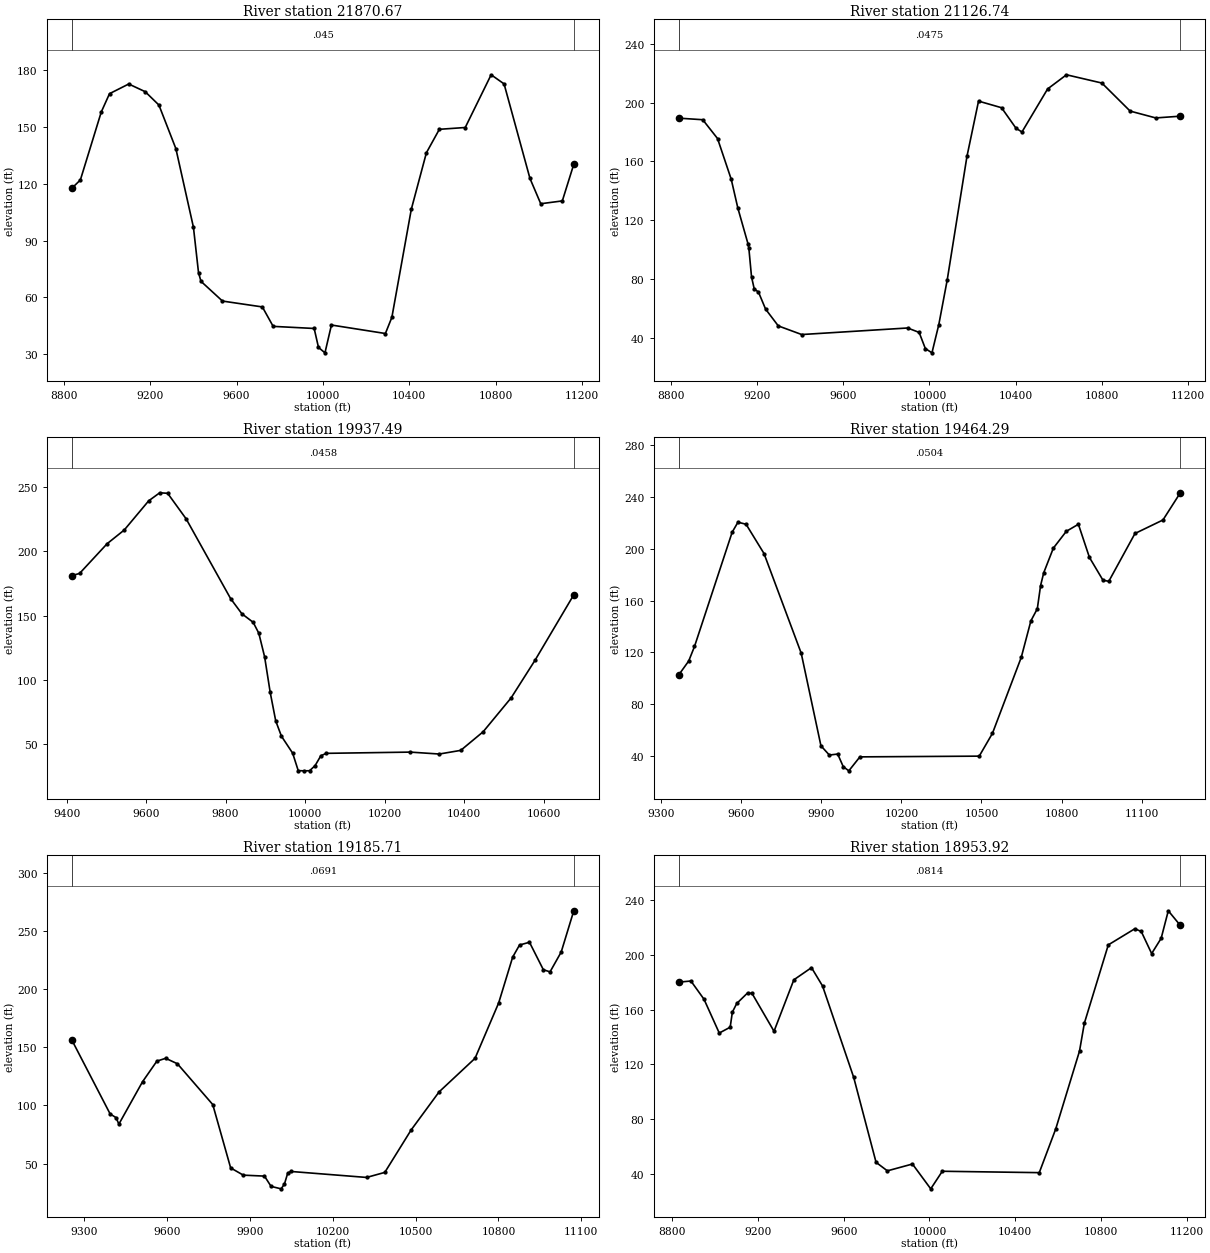
Type RM Length L Ch R = 1 ,21870.67,743.929800,743.929800,743.929800
XS GIS Cut Line= 6
674785.683348092869492.325794426675247.377490302869838.588537988
675337.752826179869884.481224284675452.653806866869918.875288983
675837.343713853869937.530030647676978.091596918  869918.3555642
#Sta/Elev= 30
8837.221117.77048875.707122.03568972.701158.03179010.853167.68819099.873 172.799
9176.177168.74029239.763161.67469318.415  138.619399.88396.984059423.30773.08175
9434.73668.417019534.41857.97202 9719.2654.868569769.40544.58456 9959.4543.47205
9979.45133.4415810009.4530.5814910039.4645.29382 10289.640.8080910319.6349.36633
10409.67106.5137 10479.7136.4315 10539.7148.835410659.71149.788510779.71 177.683
10839.71 172.85910959.71122.847611009.71109.458411109.72 110.95611162.81130.3472
#Mann= 3 , 0 , 0
8837.221   0.045       08837.221   0.045       011162.81   0.045       0
#XS Ineff= 2 , 0
       0                10152.66       0
Bank Sta=8837.221,11162.81
Exp/Cntr=0.3,0.1

Type RM Length L Ch R = 1 ,21126.74,1189.254700,1189.254700,1189.254700
XS GIS Cut Line= 6
674974.493397857869667.166136861675235.102552824869953.067469067
675592.562289134870543.385212973   675879.077447 870877.72583279
676191.403590085871124.358290743676574.698763463871278.150515236
#Sta/Elev= 30
 8833.81189.49168945.962188.41979014.708175.62429078.414147.85929109.317128.1736
9156.259103.98089160.069101.33979172.78481.399169185.49973.129739204.83171.12928
 9238.2459.434829297.24248.029939406.01442.153539898.28246.614299951.91843.60935
9980.714 32.628110011.5229.6935810043.3748.9035810082.6179.4160410174.17163.3822
10228.09201.092410335.08196.5918 10402.3182.617110429.95180.073910549.31209.3929
10636.93219.023210801.49213.395410932.88194.296711051.96 189.63911166.21190.8367
#Mann= 3 , 0 , 0
 8833.81  0.0475       0 8833.81  0.0475       011166.21  0.0475       0
#XS Ineff= 2 , 0
       0                               0
Bank Sta=8833.81,11166.21
Exp/Cntr=0.3,0.1

Type RM Length L Ch R = 1 ,19937.49,473.201600,473.201600,473.201600
XS GIS Cut Line= 6
674154.445409834869931.915116623674201.686665028869979.158693507
674261.046120435870044.708935171674306.794677258870099.888621211
674333.063376665870134.317895696675036.750759691870833.551561102
#Sta/Elev= 30
9413.809 181.2889432.698182.93039501.998206.02529545.154216.7004 9606.59239.3639
9634.387245.61429654.265245.21419700.871225.31329812.697163.37939841.071151.5753
9869.446144.95299883.633136.46439898.236118.12889912.33390.435449926.19568.32378
9940.52856.453949968.75643.27062 9982.82 29.67319997.13129.5150610011.3229.59771
10025.11  33.50210039.6941.2306810053.3143.1131910264.7744.0724610337.6242.58023
10391.6545.4182510448.0459.8758710518.5286.2488410578.81115.570610676.06166.3298
#Mann= 3 , 0 , 0
9413.809  0.0458       09413.809  0.0458       010676.06  0.0458       0
#XS Ineff= 2 , 0
       0                               0
Bank Sta=9413.809,10676.06
Exp/Cntr=0.3,0.1

Type RM Length L Ch R = 1 ,19464.29,278.573400,278.573400,278.573400
XS GIS Cut Line= 6
 673680.16975432870497.247246666674450.820913158870778.360669449
674575.242984597870849.281375184674681.615968174870958.881520743
674942.719522114871335.257448114675153.755752943871551.184938403
#Sta/Elev= 30
9365.902 102.5639403.677113.38819425.367124.58129566.358212.59359588.048220.3266
9618.447218.76429685.657196.1915 9824.95119.42439898.88348.067189930.28540.95033
9961.554 41.7205  9982.431.9947110003.2428.7839810044.7639.5446210491.5740.10706
10541.0657.6579410649.04 116.23910685.09144.3602 10709.1153.643810721.36171.5545
 10733.1181.374910769.11200.353310817.69213.310610862.92218.743710904.27 193.204
 10954.9175.655510976.77174.7966 11074.8211.633211179.61222.044711244.64243.0032
#Mann= 3 , 0 , 0
9365.902  0.0504       09365.902  0.0504       011244.64  0.0504       0
#XS Ineff= 2 , 0
       0                               0
Bank Sta=9365.902,11244.64
Exp/Cntr=0.3,0.1

Type RM Length L Ch R = 1 ,19185.71,231.791300,231.791300,231.791300
XS GIS Cut Line= 6
673553.828020791870724.662367017 673964.02715962870865.147735502
 674206.65185094870971.349544946674614.944983775871226.838556977
674943.069136326871477.493784855675127.039495592871604.617453106
#Sta/Elev= 30
9255.623155.81249393.51992.672079414.64789.538839425.21183.937159510.809 120.314
9562.776138.02529594.654140.48719637.157135.79979765.274100.71539830.053 46.2974
9875.90840.062629952.56439.24962 9976.5330.40725 10012.828.3035710024.8632.39005
10036.9241.9182410048.9743.2262710322.37 38.099310388.3842.4289110483.9978.96053
10585.09111.6195 10715.3140.4708 10800.9188.072610851.62 227.45310876.46237.8274
10912.46240.209810962.71216.603610986.96214.757511027.36 231.79311072.94267.2534
#Mann= 3 , 0 , 0
9255.623  0.0691       09255.623  0.0691       011072.94  0.0691       0
#XS Ineff= 2 , 0
       0                               0
Bank Sta=9255.623,11072.94
Exp/Cntr=0.3,0.1

Type RM Length L Ch R = 1 ,18953.92,231.791400,231.791400,231.791400
XS GIS Cut Line= 6
672968.429405972870877.537168836673531.035960105870993.982698459
 673966.71362287871121.498536161674155.416589394 871193.69264618
674631.609375457871414.842710711675155.675168967871674.983538734
#Sta/Elev= 30
8829.447180.09048886.877180.91418947.788167.61759019.102142.85579070.052147.1133
9080.242158.15099100.622164.46569151.741172.2584  9172.2171.79639274.638144.1481
9367.091181.79219449.489190.7021  9501.1177.28419646.279110.46639750.80348.25196
9803.57242.037169920.49847.0332610005.9128.8731810059.8841.7355810512.3240.71738
10589.1872.7269910700.07 129.63910722.63150.016510834.42207.343910958.05219.1293
10988.17217.170311036.71200.994711081.07212.138611114.34232.299111170.53 221.586
#Mann= 3 , 0 , 0
8829.447  0.0814       08829.447  0.0814       011170.53  0.0814       0
#XS Ineff= 2 , 0
       09884.028                       0
Bank Sta=8829.447,11170.53
Exp/Cntr=0.3,0.1

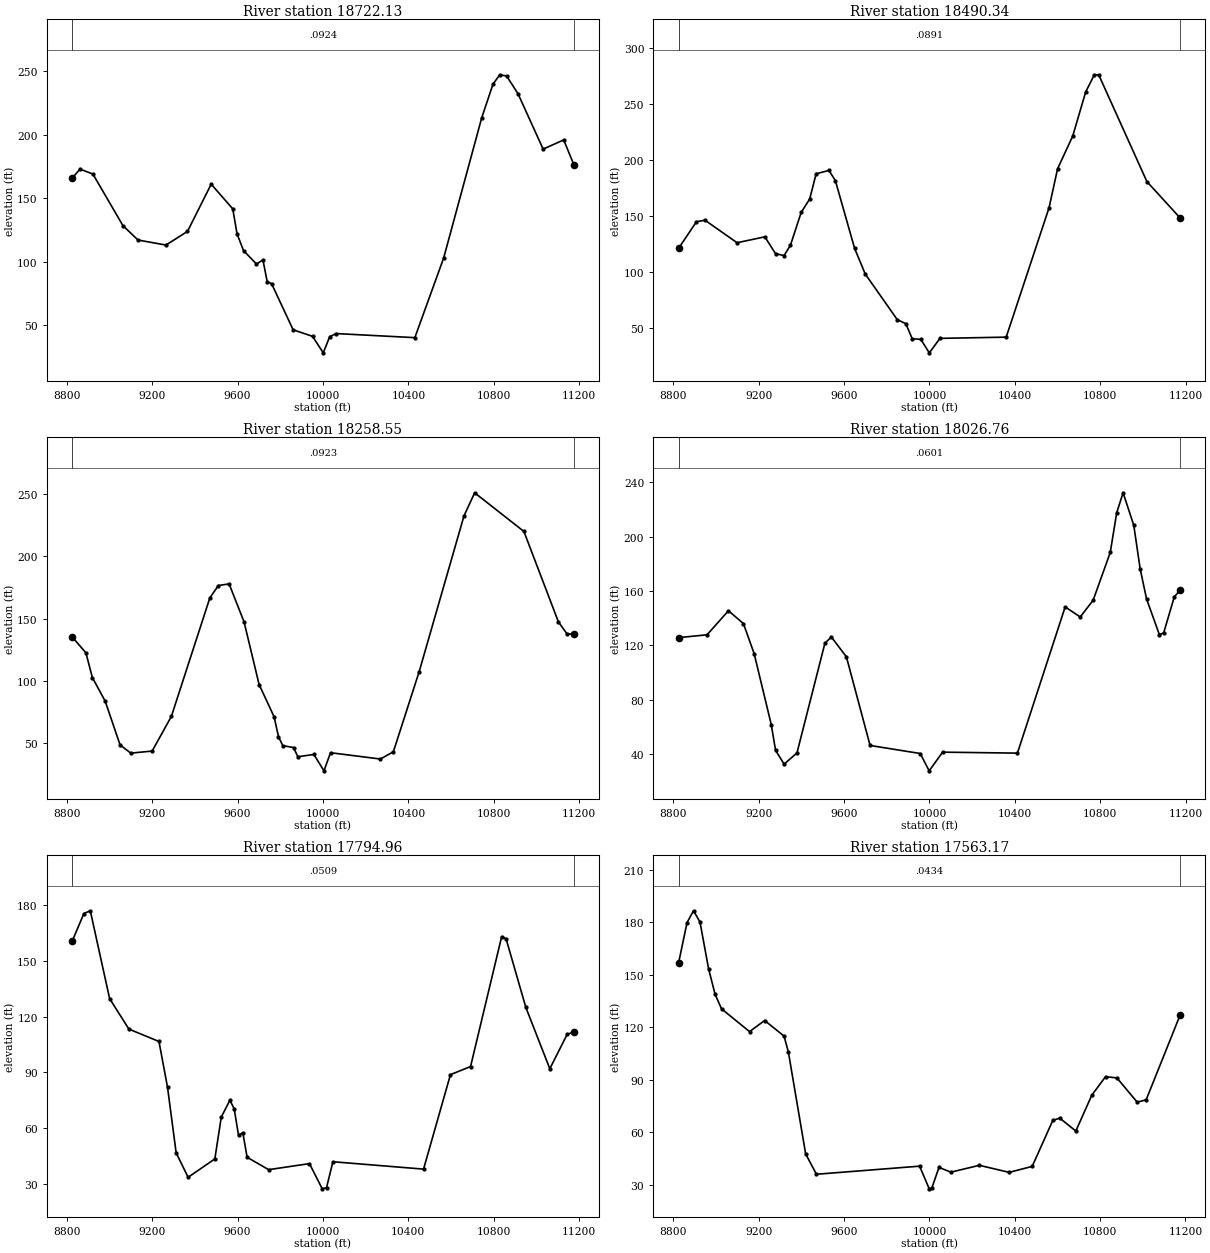
Type RM Length L Ch R = 1 ,18722.13,231.791300,231.791300,231.791300
XS GIS Cut Line= 6
 672877.97866946871249.254598994673450.760249809871314.410179694
674246.731413668871428.329085318674474.589141925871482.579664879
674670.510580751871538.576757384675169.612473947871719.629779383
#Sta/Elev= 30
8825.123165.79018862.342172.96068922.663169.06189063.411128.33099133.848116.9939
9264.835 113.0349365.594123.80149476.582161.06729577.546141.61569597.739121.8467
9628.028108.65939688.60798.051939718.896101.28149739.089 83.97799759.28282.60976
9860.24646.187639951.01940.99966 10001.427.9871210031.6440.7474910061.8943.18745
10430.1939.9740410565.09102.778210743.39213.431210796.21240.020810828.08247.3888
10859.98246.442410913.42232.393911030.99188.741411127.18195.996511174.86176.4381
#Mann= 3 , 0 , 0
8825.123  0.0924       08825.123  0.0924       011174.86  0.0924       0
#XS Ineff= 2 , 0
       09861.183                       0
Bank Sta=8825.123,11174.86
Exp/Cntr=0.3,0.1

Type RM Length L Ch R = 1 ,18490.34,231.791400,231.791400,231.791400
XS GIS Cut Line= 6
 672851.00435206871592.658488318673589.913170125871618.069333189
674326.443713043871632.008426777674509.263295802871641.643850379
674801.361120424871681.055082932675186.671759156871773.146632705
#Sta/Elev= 30
8824.881121.05788908.926144.8588 8948.95146.15719099.038126.09229229.115131.3749
9279.145116.35379319.168114.66359349.186123.93829399.216153.06619439.239165.1087
9469.257187.59579529.292190.5426 9559.31181.54029649.326121.19879699.33398.21802
9849.35557.528619889.36153.937919919.36640.456749959.38339.966069999.40127.92564
10049.4240.8327410359.5141.92188 10560.1157.197410600.35192.153110671.07221.1476
10731.87 260.59510772.41275.819610792.81275.845411018.54180.613511175.09147.9946
#Mann= 3 , 0 , 0
8824.881  0.0891       08824.881  0.0891       011175.09  0.0891       0
#XS Ineff= 2 , 0
       09538.124                       0
Bank Sta=8824.881,11175.09
Exp/Cntr=0.3,0.1

Type RM Length L Ch R = 1 ,18258.55,231.791300,231.791300,231.791300
XS GIS Cut Line= 6
672880.101884149871943.917384701673737.836901966871904.053661219
674319.347749014871805.966867018674576.779683743871781.825026277
 674900.84597751871788.862404953675216.610894297871830.706376552
#Sta/Elev= 30
8824.757135.46338889.684122.60358919.697 102.7958979.72483.853969049.75548.57894
9099.77742.05321 9199.8343.701119289.89971.55937 9470.13166.7312 9510.19176.6671
9560.332177.98859630.562147.36899700.84697.169989771.29771.151869791.426  55.394
 9811.6448.07729 9862.1946.51999 9882.4139.144629957.45440.9784510004.6727.82822
10035.3342.3851610269.2237.3146810329.6743.1237510450.28107.289510660.51232.5568
10710.51251.1599 10941.2220.102211102.76147.507711143.23137.799411175.22137.6544
#Mann= 3 , 0 , 0
8824.757  0.0923       08824.757  0.0923       011175.22  0.0923       0
#XS Ineff= 2 , 0
       09576.174                       0
Bank Sta=8824.757,11175.22
Exp/Cntr=0.3,0.1

Type RM Length L Ch R = 1 ,18026.76,231.791300,231.791300,231.791300
XS GIS Cut Line= 6
672941.798479365872225.821909604673861.713086113872136.544291472
674425.365492239871994.118246111674732.730849024871935.571483597
675029.776968909871909.193063779675263.066707054871910.463788719
#Sta/Elev= 30
8824.464125.64518958.038127.72569058.318145.43719128.513135.96699178.653113.9162
9258.97161.631699279.05142.731899319.21132.551749379.45140.860979510.214121.4994
9540.397 126.1289610.901111.5491 9721.9846.304559956.82540.391369998.78427.63975
10061.8441.38864 10412.340.66328   10636 148.25710706.56140.829110766.99153.1325
10847.29188.339310877.34 217.49310907.38232.215910957.42208.289810987.42176.1906
11017.43154.032111077.44127.820411097.44 129.08111147.45155.719611175.53160.7191
#Mann= 3 , 0 , 0
8824.464  0.0601       08824.464  0.0601       011175.53  0.0601       0
#XS Ineff= 2 , 0
       09572.532                       0
Bank Sta=8824.464,11175.53
Exp/Cntr=0.3,0.1

Type RM Length L Ch R = 1 ,17794.96,231.791400,231.791400,231.791400
XS GIS Cut Line= 6
672980.004115606872432.957610351674005.346867987872311.701987304
674263.534223869872301.237169996674414.453377395872263.432519155
 674966.43435417872092.048873698675286.137687505872026.955387455
#Sta/Elev= 30
8824.229160.51728879.509175.57728909.664177.05989000.128129.77969090.593113.3394
9231.445106.68269271.69281.936519311.93946.743489368.06533.545019493.27643.43032
9523.52365.970639563.87875.039149584.05570.411879604.23356.20718 9624.4157.52726
9644.58844.314949745.47537.649479936.62340.902479996.64527.3257710016.6627.95781
10046.6641.9192610471.3937.9408410597.4288.8292810691.66 93.173810837.44163.1618
10858.13161.959810950.78125.007611063.1191.9945411144.32110.506811175.76111.8461
#Mann= 3 , 0 , 0
8824.229  0.0509       08824.229  0.0509       011175.76  0.0509       0
#XS Ineff= 2 , 0
       09549.155                       0
Bank Sta=8824.229,11175.76
Exp/Cntr=0.3,0.1

Type RM Length L Ch R = 1 ,17563.17,231.791300,231.791300,231.791300
XS GIS Cut Line= 6
673055.495761232872744.400338764674066.576170781872583.008726046
674388.856164861872429.946473462  674855.4381422872243.875784718
675074.990323055872162.781499729675299.365223369872097.804384138
#Sta/Elev= 30
8824.137156.54488864.045 179.7368894.351 186.4788924.658180.09178965.067153.2745
8995.373138.7656 9025.68130.42389157.008117.40629227.751123.7606 9318.81114.8332
9339.045105.66199419.98547.459569470.573 35.88019953.98940.503569999.07727.54478
10010.51 27.743710044.8539.8098110100.1937.0705410233.9640.9847210373.91 36.9623
10481.57 40.369110578.4666.7039110610.7667.9615510686.1260.5816910761.1581.10638
10825.3391.6472110878.6290.95157 10973.777.08713 11015.778.4200811175.87127.1739
#Mann= 3 , 0 , 0
8824.137  0.0434       08824.137  0.0434       011175.87  0.0434       0
#XS Ineff= 2 , 0
       0 9315.45                       0
Bank Sta=8824.137,11175.87
Exp/Cntr=0.3,0.1