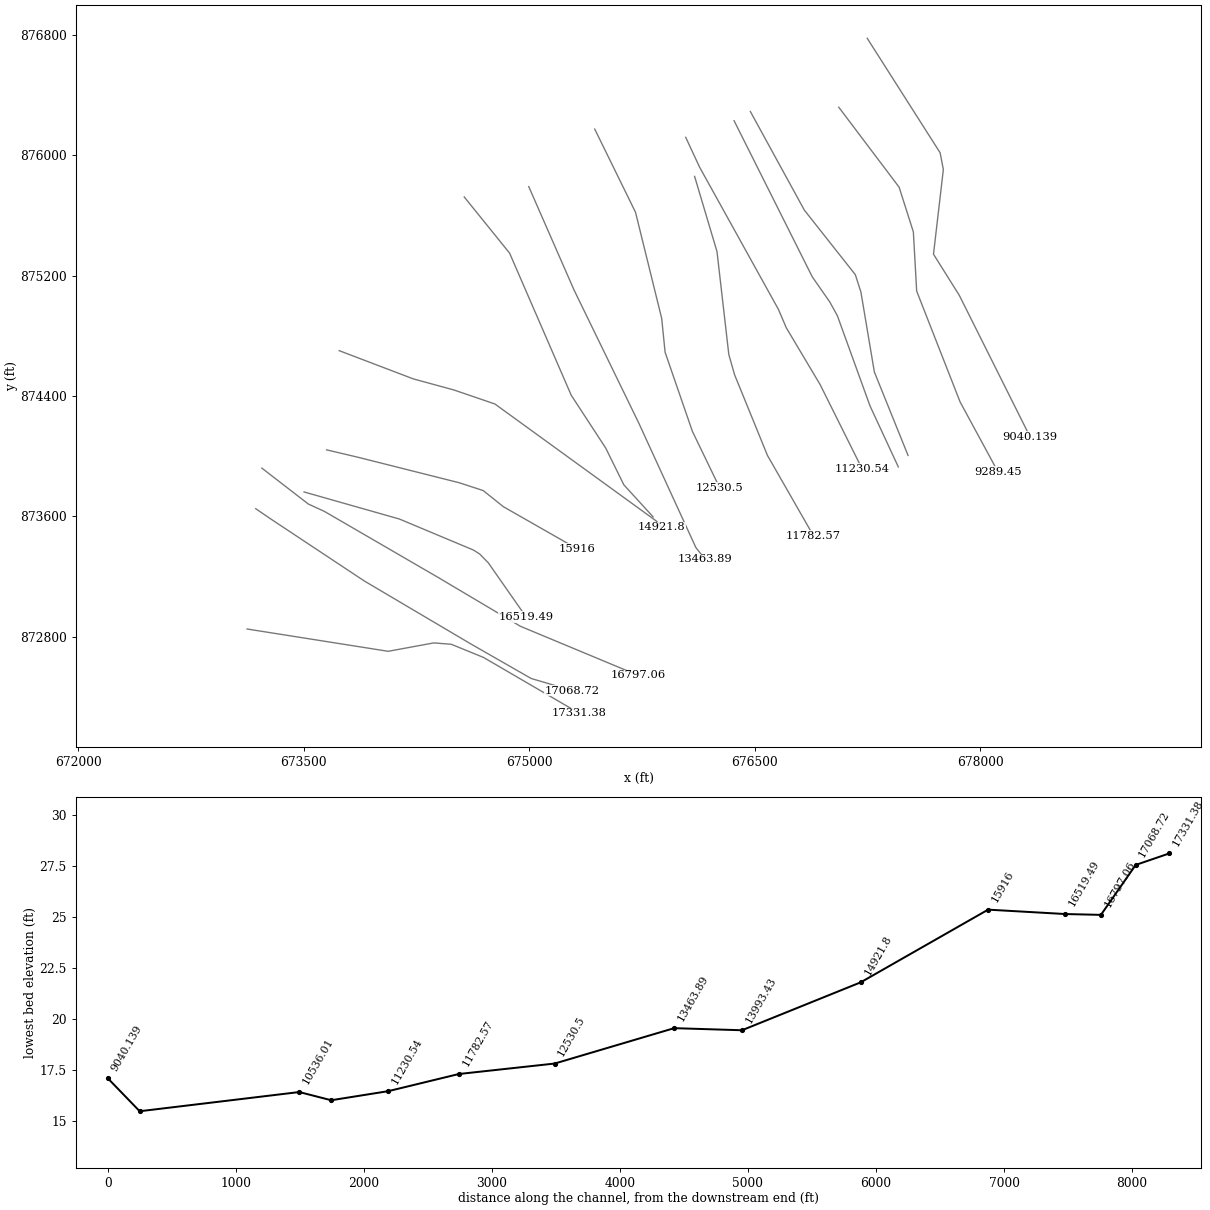
HEC-RAS study 13716_ras.prj: 13716

--- 13716_ras.g01 (geometry) --- (continued)

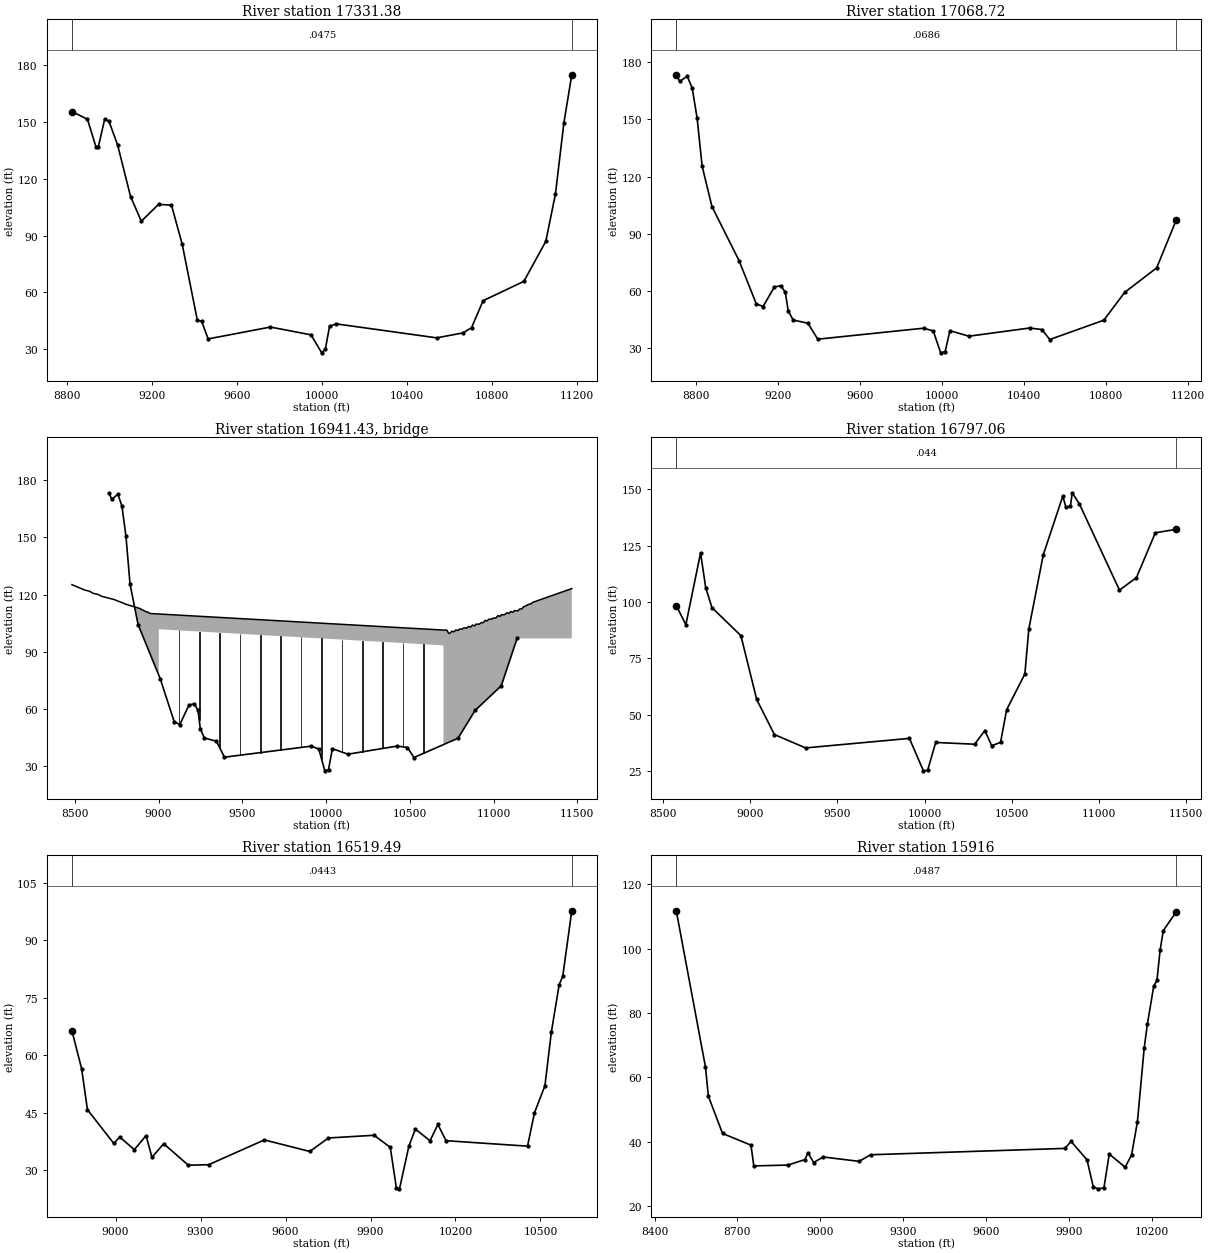
Type RM Length L Ch R = 1 ,17331.38,262.665700,262.665700,262.665700
XS GIS Cut Line= 6
673123.028820603872850.327674084674061.675786706872702.001970245
674364.849283607872757.806803924674481.136514977872748.806203705
674696.074459338872660.990085257675333.778437811872289.163279982
#Sta/Elev= 30
8824.102155.58828897.053151.49888937.597136.66498947.733136.71268978.141151.6357
8998.413150.39639038.958137.86899099.774110.67589150.45497.625329231.543106.5504
9292.359106.1303 9343.0485.354489413.99245.286419434.26444.766349464.67235.45703
9757.753  41.7239949.14437.60748    999928.1006810016.5230.0967110035.9642.10481
10067.1843.4063910540.0136.0171610664.1938.6363210704.2141.3768310758.5955.63804
10950.5265.87925 11053.887.0459211099.04112.102411138.86149.753211175.86174.9995
#Mann= 3 , 0 , 0
8824.102  0.0475       08824.102  0.0475       011175.86  0.0475       0
#XS Ineff= 2 , 0
       09181.316        10532.48       0
Bank Sta=8824.102,11175.86
Exp/Cntr=0.3,0.1

Type RM Length L Ch R = 1 ,17068.72,271.656300,271.656300,271.656300
XS GIS Cut Line= 6
673180.855416238873650.268684641673283.930550933873579.990183681
673901.986106485873170.267961472674606.847217619872753.601294786
 675013.09721759 872520.96240592675285.636440009872440.978068948
#Sta/Elev= 30
8703.473173.40658720.593 169.9438756.902172.64698781.109166.46748805.315150.5565
 8829.51125.54568877.501  104.269009.47775.958779093.46153.282539126.83251.81899
9181.12761.993979213.43962.799559235.42259.207899249.43249.543339273.42844.76129
9345.41443.063929393.40634.699819910.13740.470329956.60339.015869992.78627.53559
10014.6928.1531510037.92 39.158510130.8536.2665710425.9940.5513710486.3639.77185
10524.7134.5129810788.2144.6553510889.9559.2340311046.2872.1312111140.7497.02181
#Mann= 3 , 0 , 0
8703.473  0.0686       08703.473  0.0686       011140.74  0.0686       0
#XS Ineff= 2 , 0
       0                10587.29       0
Bank Sta=8703.473,11140.74
Exp/Cntr=0.3,0.1

Type RM Length L Ch R = 3 ,16941.43,,,
BEGIN DESCRIPTION:
END DESCRIPTION:
Bridge Culvert--1,0,-1,-1, 0
Deck Dist Width WeirC Skew NumUp NumDn MinLoCord MaxHiCord MaxSubmerge Is_Ogee
74.828150,122.000000,2.6,0, 60, 60, , , 0.95, 0, 0,0,,
 8482.84 8560.56 8585.46 8611.64 8635.25 8660.15 8734.83 8809.52 8884.21 8929.00
 8933.99 8947.82 9001.30 9001.3010701.3010701.3010720.8810731.9510739.1210752.08
10763.2110775.8710788.3310797.6810813.4510819.4810830.3810838.5710852.1810863.69
10873.9810884.8810888.8110895.7810913.9410928.4910939.0610950.2910961.1910972.09
10989.3010993.8911014.4211026.5911039.5411048.4011064.6611081.1011092.0011102.90
11114.9111124.7011146.5011157.4111168.3111179.2111211.9111222.8111233.7111467.39
  125.21  122.31  121.82  120.58  120.22  119.11  117.38  114.79  112.83  110.85
  110.91  110.09  109.82  109.82  101.38  101.38  101.37   99.71   99.66  100.81
  100.44  101.47  101.15  101.94  101.88  102.40  102.56  102.38  103.31  102.95
  104.00  103.64  103.70  104.52  104.47  105.30  105.31  106.50  106.14  107.10
  107.11  107.59  107.77  108.95  108.60  109.47  109.40  110.47  110.08  111.14
  110.66  111.58  111.51  112.50  112.46  113.54  114.95  115.09  115.91  123.15
 -874.79 -877.69 -878.18 -879.42 -879.78 -880.89 -882.62 -885.21 -887.17 -889.15
 -889.09 -889.91 -890.18  101.82   93.38 -898.62 -898.63 -900.29 -900.34 -899.19
 -899.56 -898.53 -898.85 -898.06 -898.12 -897.60 -897.44 -897.62 -896.69 -897.05
 -896.00 -896.36 -896.30 -895.48 -895.53 -894.70 -894.69 -893.50 -893.86 -892.90
 -892.89 -892.41 -892.23 -891.05 -891.40 -890.53 -890.60 -889.53 -889.92 -888.86
 -889.34 -888.42 -888.49 -887.50 -887.54 -886.46 -885.05 -884.91 -884.09 -876.85
 8482.84 8560.56 8585.46 8611.64 8635.25 8660.15 8734.83 8809.52 8884.21 8929.00
 8933.99 8947.82 8975.53 8975.5310675.5310675.5310720.8810731.9510739.1210752.08
10763.2110775.8710788.3310797.6810813.4510819.4810830.3810838.5710852.1810863.69
10873.9810884.8810888.8110895.7810913.9410928.4910939.0610950.2910961.1910972.09
10989.3010993.8911014.4211026.5911039.5411048.4011064.6611081.1011092.0011102.90
11114.9111124.7011146.5011157.4111168.3111179.2111211.9111222.8111233.7111467.39
  125.21  122.31  121.82  120.58  120.22  119.11  117.38  114.79  112.83  110.85
  110.91  110.09  109.95  109.95  101.51  101.51  101.37   99.71   99.66  100.81
  100.44  101.47  101.15  101.94  101.88  102.40  102.56  102.38  103.31  102.95
  104.00  103.64  103.70  104.52  104.47  105.30  105.31  106.50  106.14  107.10
  107.11  107.59  107.77  108.95  108.60  109.47  109.40  110.47  110.08  111.14
  110.66  111.58  111.51  112.50  112.46  113.54  114.95  115.09  115.91  123.15
 -874.79 -877.69 -878.18 -879.42 -879.78 -880.89 -882.62 -885.21 -887.17 -889.15
 -889.09 -889.91 -890.05  101.95   93.51 -898.49 -898.63 -900.29 -900.34 -899.19
 -899.56 -898.53 -898.85 -898.06 -898.12 -897.60 -897.44 -897.62 -896.69 -897.05
 -896.00 -896.36 -896.30 -895.48 -895.53 -894.70 -894.69 -893.50 -893.86 -892.90
 -892.89 -892.41 -892.23 -891.05 -891.40 -890.53 -890.60 -889.53 -889.92 -888.86
 -889.34 -888.42 -888.49 -887.50 -887.54 -886.46 -885.05 -884.91 -884.09 -876.85
Pier Skew, UpSta & Num, DnSta & Num=  ,9121.01, 2 ,9095.24, 2 , 0 , 0 , 0 ,,
    4.00    4.00
 -890.77  109.23
    4.00    4.00
 -890.64  109.36
Pier Skew, UpSta & Num, DnSta & Num=  ,9242.73, 2 ,9216.96, 2 , 0 , 0 , 0 ,,
    4.00    4.00
 -891.38  108.62
    4.00    4.00
 -891.25  108.75
Pier Skew, UpSta & Num, DnSta & Num=  ,9364.44, 2 ,9338.67, 2 , 0 , 0 , 0 ,,
    4.00    4.00
 -891.98  108.02
    4.00    4.00
 -891.85  108.15
Pier Skew, UpSta & Num, DnSta & Num=  ,9486.16, 2 ,9460.38, 2 , 0 , 0 , 0 ,,
    4.00    4.00
 -892.59  107.41
    4.00    4.00
 -892.46  107.54
Pier Skew, UpSta & Num, DnSta & Num=  ,9607.87, 2 ,9582.10, 2 , 0 , 0 , 0 ,,
    4.00    4.00
 -893.19  106.81
    4.00    4.00
 -893.06  106.94
Pier Skew, UpSta & Num, DnSta & Num=  ,9729.58, 2 ,9703.81, 2 , 0 , 0 , 0 ,,
    4.00    4.00
 -893.79  106.21
    4.00    4.00
 -893.67  106.33
Pier Skew, UpSta & Num, DnSta & Num=  ,9851.30, 2 ,9825.53, 2 , 0 , 0 , 0 ,,
    4.00    4.00
 -894.40  105.60
    4.00    4.00
 -894.27  105.73
Pier Skew, UpSta & Num, DnSta & Num=  ,9973.01, 2 ,9947.24, 2 , 0 , 0 , 0 ,,
    4.00    4.00
 -895.00  105.00
    4.00    4.00
 -894.87  105.13
Pier Skew, UpSta & Num, DnSta & Num=  ,10094.73, 2 ,10068.96, 2 , 0 , 0 , 0 ,,
    4.00    4.00
 -895.61  104.39
    4.00    4.00
 -895.48  104.52
Pier Skew, UpSta & Num, DnSta & Num=  ,10216.44, 2 ,10190.67, 2 , 0 , 0 , 0 ,,
    4.00    4.00
 -896.21  103.79
    4.00    4.00
 -896.08  103.92
Pier Skew, UpSta & Num, DnSta & Num=  ,10338.16, 2 ,10312.38, 2 , 0 , 0 , 0 ,,
    4.00    4.00
 -896.81  103.19
    4.00    4.00
 -896.69  103.31
Pier Skew, UpSta & Num, DnSta & Num=  ,10459.87, 2 ,10434.10, 2 , 0 , 0 , 0 ,,
    4.00    4.00
 -897.42  102.58
    4.00    4.00
 -897.29  102.71
Pier Skew, UpSta & Num, DnSta & Num=  ,10581.58, 2 ,10555.81, 2 , 0 , 0 , 0 ,,
    4.00    4.00
 -898.02  101.98
    4.00    4.00
 -897.89  102.11
BR Coef=-1 , 0 , 0 ,, 0 ,,,0.8,0,1,0,
WSPro=,,,, 1 ,,,, 0 ,,,, 0 ,,,,-1 ,-1 ,-1 , 0 , 0 , 0 , 0 , 0
BC Design=,, 0 ,, 0 ,,,,,,

Type RM Length L Ch R = 1 ,16797.06,277.568300,277.568300,277.568300
XS GIS Cut Line= 6
673221.430550933873920.267961457673530.539795011873681.549931407
 673638.09721759 873632.07351701674391.569439799873194.573517025
674940.589047849872868.593124777675724.902773172872541.795739248
#Sta/Elev= 30
8574.94498.396528629.99489.890368714.447 121.7288743.708106.3784 8779.8997.45306
8945.86785.051749036.45456.748779138.12841.185739317.04435.253999912.88439.48184
 9993.5125.0876610017.3125.2905110063.8337.6703210287.3236.8940610346.08 42.9749
10385.2536.2136410435.9937.7125510470.88 52.163610575.5468.0442310598.4588.07301
10681.02120.851710793.45146.974210811.02141.891710837.02142.533410847.62148.3962
10889.02143.357411118.45105.225611215.95 110.78111324.29130.653311443.35132.1784
#Mann= 3 , 0 , 0
8574.944   0.044       08574.944   0.044       011443.35   0.044       0
#XS Ineff= 2 , 0
       0                               0
Bank Sta=8574.944,11443.35
Exp/Cntr=0.3,0.1

Type RM Length L Ch R = 1 ,16519.49,603.488900,603.488900,603.488900
XS GIS Cut Line= 6
673502.098682702873761.783994302674136.438089877873581.624352843
674627.208672255873376.004128426674669.582000047873349.550790504
674727.196257412873290.911085784674979.302515775872930.005470142
#Sta/Elev= 30
8845.91766.332258879.91656.497368900.584 45.79138993.604 36.96679014.32438.67334
9066.124 35.35739107.56439.026549128.28433.336899169.72436.903739256.59831.29643
9328.41731.422969525.206 37.89649685.75334.878079751.29938.403989912.76539.10856
9969.90335.954829991.47425.2558610002.3625.1282310035.4136.2457310058.2940.72298
10110.1737.6795910137.8441.9270510166.9337.69152 10454.536.2680210478.84 44.9546
10515.8752.03204 10538.566.0258410566.1678.4339410578.7380.57493 10610.797.69966
#Mann= 3 , 0 , 0
8845.917  0.0443       08845.917  0.0443       0 10610.7  0.0443       0
#XS Ineff= 2 , 0
       0                               0
Bank Sta=8845.917,10610.7
Exp/Cntr=0.3,0.1

Type RM Length L Ch R = 1 ,   15916,994.198500,994.198500,994.198500
XS GIS Cut Line= 6
673651.986106485874041.795739233673862.718044221873992.056082651
674533.930550933873823.045739248674693.652773172873770.962405905
674827.899653673873663.564901516675315.180550933873385.545739248
#Sta/Elev= 30
8478.733111.77928584.57763.176018594.85254.177828646.22642.557528749.16938.92393
8759.48132.471898883.22732.72816  8945.134.459678955.41236.584128976.03633.52995
 9010.8335.24332 9141.0333.887419182.27935.937779885.87437.913129908.21140.08389
9965.77634.374489988.80325.8757510006.9525.3436710027.1325.6686810046.3736.14207
10103.9332.0829910126.9635.81695 10148.246.0749310173.01 69.194410184.5376.60788
10207.5588.3939510219.0790.1391510230.58 99.587310242.09105.622510288.35 111.375
#Mann= 3 , 0 , 0
8478.733  0.0487       08478.733  0.0487       010288.35  0.0487       0
#XS Ineff= 2 , 0
       0                               0
Bank Sta=8478.733,10288.35
Exp/Cntr=0.3,0.1

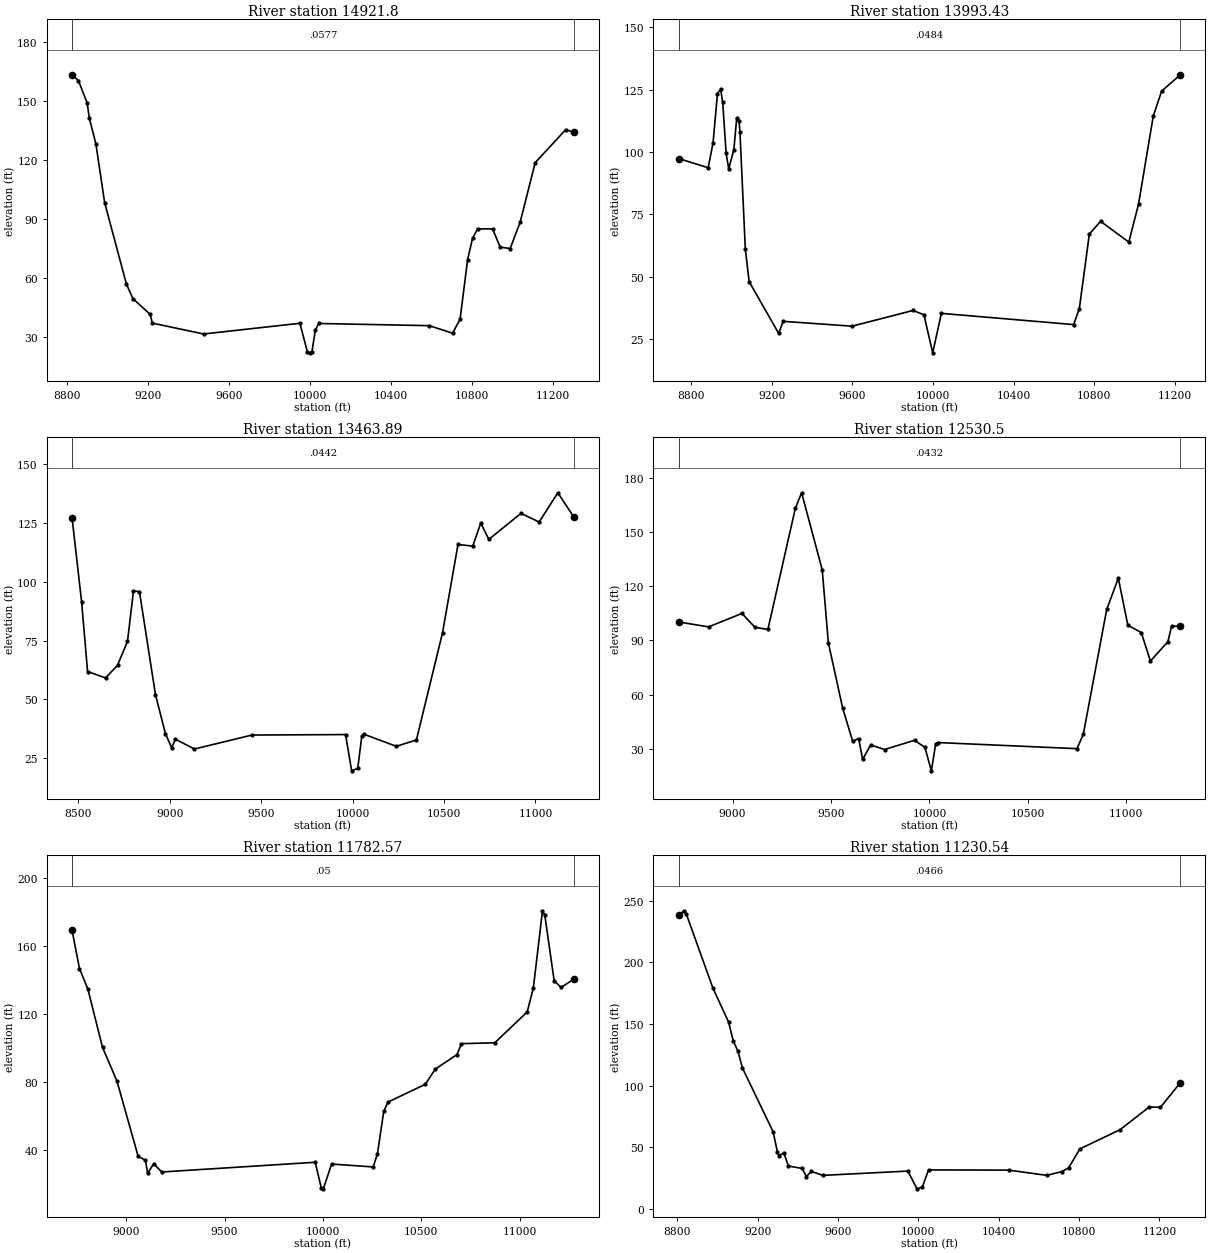
Type RM Length L Ch R = 1 , 14921.8,928.370700,928.370700,928.370700
XS GIS Cut Line= 6
673736.026705563   874701.403081674228.800424784874513.653151289
 674498.49747628874440.069234133674771.563941091874346.742720827
675846.083167762873567.421083912675881.120950431873526.644751519
#Sta/Elev= 30
8824.884163.5424 8856.15160.61518899.316149.17858910.108141.40288942.482128.3501
8985.64898.388679093.08956.862269125.20749.435889210.60941.364479221.201 36.9352
9473.80531.394019949.53836.853019986.59722.205329998.951 21.783110008.7222.25931
10025.7533.4745910042.7836.7511610587.82 35.636510703.0831.7938110740.1438.93502
 10777.269.2378310801.9180.2961410826.6284.9566710900.7484.97606 10937.875.68954
10987.2174.9423411036.6288.3909311110.74118.720311261.65 135.58511301.73134.1726
#Mann= 3 , 0 , 0
8824.884  0.0577       08824.884  0.0577       011301.73  0.0577       0
#XS Ineff= 2 , 0
       0                               0
Bank Sta=8824.884,11301.73
Exp/Cntr=0.3,0.1

Type RM Length L Ch R = 1 ,13993.43,529.539900,529.539900,529.539900
XS GIS Cut Line= 6
674567.505869895875723.586177155 674869.18287918875350.141631648
675279.254555941874404.580892146675508.398678154 874053.70395495
675628.952291012873809.200852871675823.996609449873595.600370958
#Sta/Elev= 30
8735.89997.34654 8883.0593.646498907.191103.51088929.359123.37088944.796125.2082
8955.378119.8101 8972.3499.372238985.101  93.1749010.623100.84489024.827 113.521
9036.146112.58269040.924108.02069067.56961.143039086.61247.987649233.23427.24098
9255.53332.061489598.14530.122179900.95336.431369955.02634.664689998.28419.43143
10041.5435.2598710698.5530.75669 10726.7  37.12510776.5967.0686910832.34  72.159
10972.6163.8342211020.8379.0506511094.13114.443911135.78124.384511228.44130.9186
#Mann= 3 , 0 , 0
8735.899  0.0484       08735.899  0.0484       011228.44  0.0484       0
#XS Ineff= 2 , 0
       0                               0
Bank Sta=8735.899,11228.44
Exp/Cntr=0.3,0.1

Type RM Length L Ch R = 1 ,13463.89,933.390100,933.390100,933.390100
XS GIS Cut Line= 5
 674996.49016282875792.697003648675297.436745048875105.535640955
675729.106999487874218.213451251676107.771904618873392.513588637
676168.902688771873314.220842361
#Sta/Elev= 30
 8465.26127.19028517.33191.547148550.08261.793318648.33559.090628713.83764.44284
8768.422 74.62368801.173 96.13748833.92495.77207 8921.2652.011578975.84435.39585
9009.94229.342689030.42933.001839134.57828.823129449.56134.769959961.10734.97099
9994.46819.5338310027.8320.5805810050.0734.3541310061.1935.1231110238.7329.97872
10348.74 32.669710491.7678.3933410576.16115.876310656.78115.166710700.78124.9905
10744.79118.033510920.81129.124111019.83125.412711122.32137.8699 11209.9127.5022
#Mann= 3 , 0 , 0
 8465.26  0.0442       0 8465.26  0.0442       0 11209.9  0.0442       0
#XS Ineff= 2 , 0
       0                               0
Bank Sta=8465.26,11209.9
Exp/Cntr=0.3,0.1

Type RM Length L Ch R = 1 , 12530.5,747.935300,747.935300,747.935300
XS GIS Cut Line= 6
675435.286484607876175.219490397675706.660201472875621.684372661
675880.614648331874916.347128002675903.402621074874690.576915593
676084.954896318874164.593525005676266.161278839873789.458800102
#Sta/Elev= 30
8725.739100.23888878.314 97.4984 9047.84104.94539113.91297.261829179.54496.08707
9318.955163.16139350.775171.75079455.479 129.0959486.62788.676229558.788 52.7895
9609.945 34.22119640.46435.64144 9660.8124.109499701.45332.143299772.21229.61071
9924.38534.710849977.08530.7704910009.8417.7989910031.83 32.826110042.6133.46441
10749.6630.0813310781.7738.1827610900.37  107.18 10959.3124.466811007.5998.45593
11076.0394.3206511122.2678.5839311211.0789.2978311229.6397.8666311274.1897.95163
#Mann= 3 , 0 , 0
8725.739  0.0432       08725.739  0.0432       011274.18  0.0432       0
#XS Ineff= 2 , 0
       0                               0
Bank Sta=8725.739,11274.18
Exp/Cntr=0.3,0.1

Type RM Length L Ch R = 1 ,11782.57,552.029200,552.029200,552.029200
XS GIS Cut Line= 6
676099.675998807875860.280921485676248.512753172875360.320053387
676327.162382291874675.441136396676365.717538278874540.635763183
676584.183275112874004.455041623  676890.0774893873470.372558058
#Sta/Elev= 30
8724.794169.0594 8762.41146.63618805.057134.66258879.485100.38528953.05580.52212
9060.81836.326569097.88134.086749108.87126.456539139.65532.038189180.70227.18374
9960.68932.895359991.52217.8327410001.9517.2866310043.9431.8460710255.4830.14833
10276.8837.8282710308.9762.7628210330.3768.2217310520.4778.6929210570.51 87.5449
10681.4196.1684210703.91102.542910873.37103.059311038.17121.192411069.37135.2375
11115.91180.587411127.75177.965711175.13139.5925 11209.9135.565611275.36140.4065
#Mann= 3 , 0 , 0
8724.794    0.05       08724.794    0.05       011275.36    0.05       0
#XS Ineff= 2 , 0
       0                               0
Bank Sta=8724.794,11275.36
Exp/Cntr=0.3,0.1

Type RM Length L Ch R = 1 ,11230.54,445.217800,445.217800,445.217800
XS GIS Cut Line= 6
676040.465882063876120.286020994676133.316732377875920.774172753
676657.317679852874975.517561674676709.296722651874853.739699528
676934.307575941874475.788758814677212.846378207873917.031969965
#Sta/Elev= 30
8806.475238.33728834.677241.74078845.829238.82668978.096178.8808 9056.04151.3981
9078.907136.18929101.775128.11969124.642114.30119277.54962.616529298.17446.59429
9307.58243.257679330.44945.608849353.31734.925349421.91932.976869442.55326.36211
9467.65430.521719525.05527.35774 9947.8730.840139993.60516.4452110020.0717.84956
10050.7731.7837910450.2131.6066910639.3327.3803310714.4630.4027710748.0833.41502
10804.0748.76619 11004.464.3752811149.0882.7267811205.3482.5088111304.31102.4455
#Mann= 3 , 0 , 0
8806.475  0.0466       08806.475  0.0466       011304.31  0.0466       0
#XS Ineff= 2 , 0
       0                11248.98       0
Bank Sta=8806.475,11304.31
Exp/Cntr=0.3,0.1

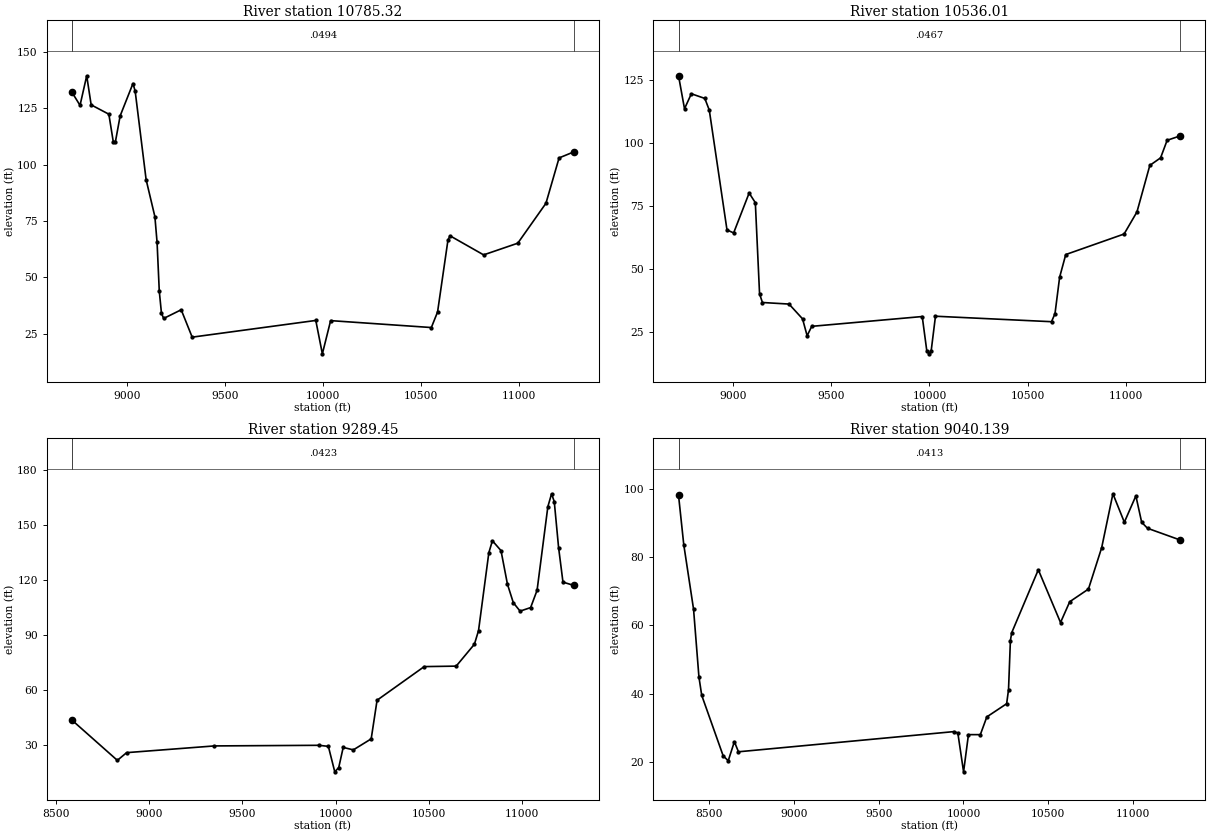
Type RM Length L Ch R = 1 ,10785.32,249.311800,249.311800,249.311800
XS GIS Cut Line= 6
676362.119920621876230.772321077676882.034939782875192.574792522
676998.311412218875025.725387522677048.993215233874934.095266778
677266.336765742    874333.42554677454.472350794873928.033137052
#Sta/Elev= 30
8722.086132.1283 8762.64 126.394 8796.65139.53728819.324126.61488909.444122.4715
8931.776110.32598942.942110.25948966.987121.72329032.268136.09939043.434132.7305
9099.262  93.3789143.92576.946859155.09165.468359166.257 43.87319177.42334.03367
9188.58931.720689277.91535.577839333.84623.413479963.472 30.83689996.919 16.0003
10039.0430.7570710552.0427.6847110583.6934.5852510636.6366.5331610647.2868.43557
10818.3659.9658910992.2565.1555911135.6982.8793211202.63103.0443 11277.9105.7346
#Mann= 3 , 0 , 0
8722.086  0.0494       08722.086  0.0494       0 11277.9  0.0494       0
#XS Ineff= 2 , 0
       0                11085.51       0
Bank Sta=8722.086,11277.9
Exp/Cntr=0.3,0.1

Type RM Length L Ch R = 1 ,10536.01,1246.558800,1246.558800,1246.558800
XS GIS Cut Line= 6
676470.228544355876292.157785993676829.503327923875635.968134294
677168.534592444875206.710400384677205.621927972875091.362164434
677295.058754755874559.618036965 677519.13826975874004.573021596
#Sta/Elev= 30
8720.958126.75398751.388113.66498786.335119.61728854.963117.76258877.706113.1342
 8968.0165.562449001.874 64.3917 9080.8980.217529112.46176.390739134.018 40.2105
9148.61736.774549284.225 36.15519353.17830.289389376.50223.574799399.98227.31788
9963.28931.206489986.35917.714899997.827  16.40210008.9817.6378610030.7431.32946
10622.3629.1552610640.0732.3550110663.7246.8166710694.9255.8068810992.3363.95816
 11057.972.7156111123.4791.1885411178.3894.1827111211.76101.1518   11279102.9235
#Mann= 3 , 0 , 0
8720.958  0.0467       08720.958  0.0467       0   11279  0.0467       0
#XS Ineff= 2 , 0
       0                11109.41       0
Bank Sta=8720.958,11279
Exp/Cntr=0.3,0.1

Type RM Length L Ch R = 1 , 9289.45,249.311700,249.311700,249.311700
XS GIS Cut Line= 6
677058.373925865876320.350860968677459.804942191875788.540540203
677554.485211909875490.973978162677576.454488873 875097.59003292
677865.317563206874360.395068124 678117.38498798873895.263450861
#Sta/Elev= 30
8584.08443.55866 8827.4621.711828877.25525.906999348.556 29.56799910.17329.90335
9961.46729.340659995.95415.4613210017.3217.8204510041.2328.7473310095.8527.42291
10191.7333.4062410223.3154.4471610476.6672.7412310648.5273.0078610746.4684.92506
10768.5592.3289710824.01134.757710843.12141.242510889.32135.884710923.99117.6068
10955.48107.542710991.91102.940511048.55104.8674 11083.2114.265711141.13 159.783
11161.12166.817411175.59162.562311198.84137.545411222.38118.730911280.92116.9289
#Mann= 3 , 0 , 0
8584.084  0.0423       08584.084  0.0423       011280.92  0.0423       0
#XS Ineff= 2 , 0
       0                10663.03       0
Bank Sta=8584.084,11280.92
Exp/Cntr=0.3,0.1

Type RM Length L Ch R = 1 ,9040.139,249.311800,249.311800,249.311800
XS GIS Cut Line= 6
677247.729378551876778.591056511677732.479337454876017.382136658
677753.878473043875906.163018689677688.322043598875342.861216351
677859.538940758 875070.18670103678330.521675527874128.579818681
#Sta/Elev= 30
8317.19498.058098348.12883.591048405.89764.712128437.68544.860518454.11139.48867
8580.97521.746958610.80720.328648646.96725.909068671.07422.950419944.28528.86319
9966.83428.4506310000.7317.07814 10029.527.9762510099.7327.9698510138.07   33.17
10255.06 37.023810266.1841.1068210277.3155.5224110285.0557.8199710442.1376.25537
10573.36 60.809210627.7966.8999110738.2170.6009110816.4882.73709 10882.898.50958
10950.3190.17906 11018.497.8960111052.6290.1613411087.1888.4069811280.9484.95317
#Mann= 3 , 0 , 0
8317.194  0.0413       08317.194  0.0413       011280.94  0.0413       0
#XS Ineff= 2 , 0
       08650.971        10726.11       0
Bank Sta=8317.194,11280.94
Exp/Cntr=0.3,0.1