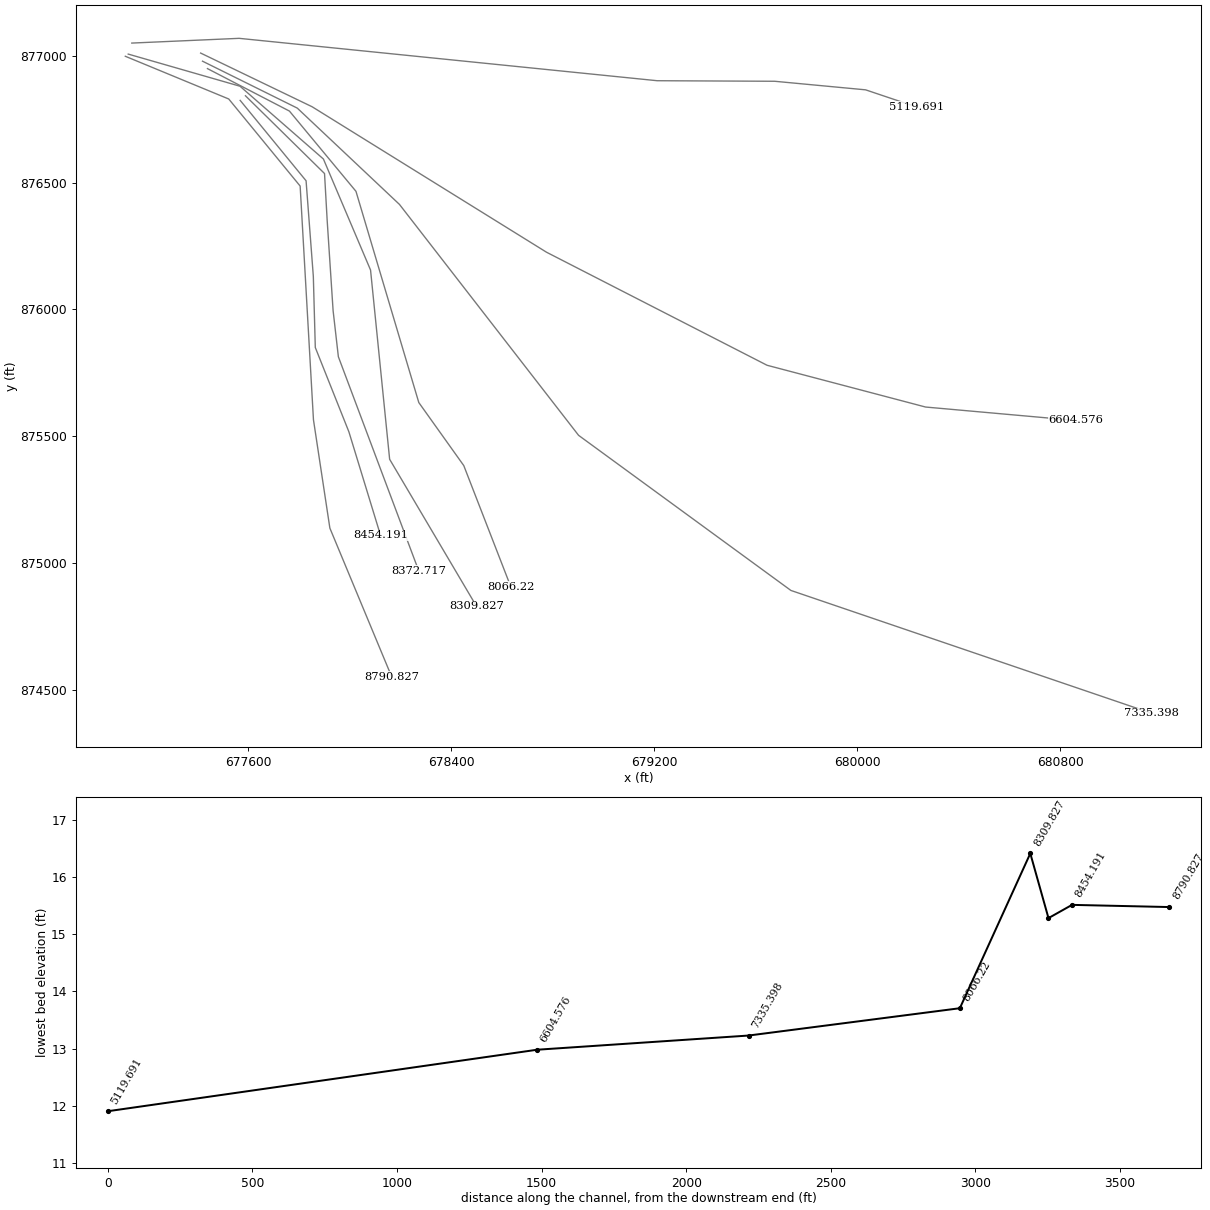
HEC-RAS study 13716_ras.prj: 13716

--- 13716_ras.g01 (geometry) --- (continued)

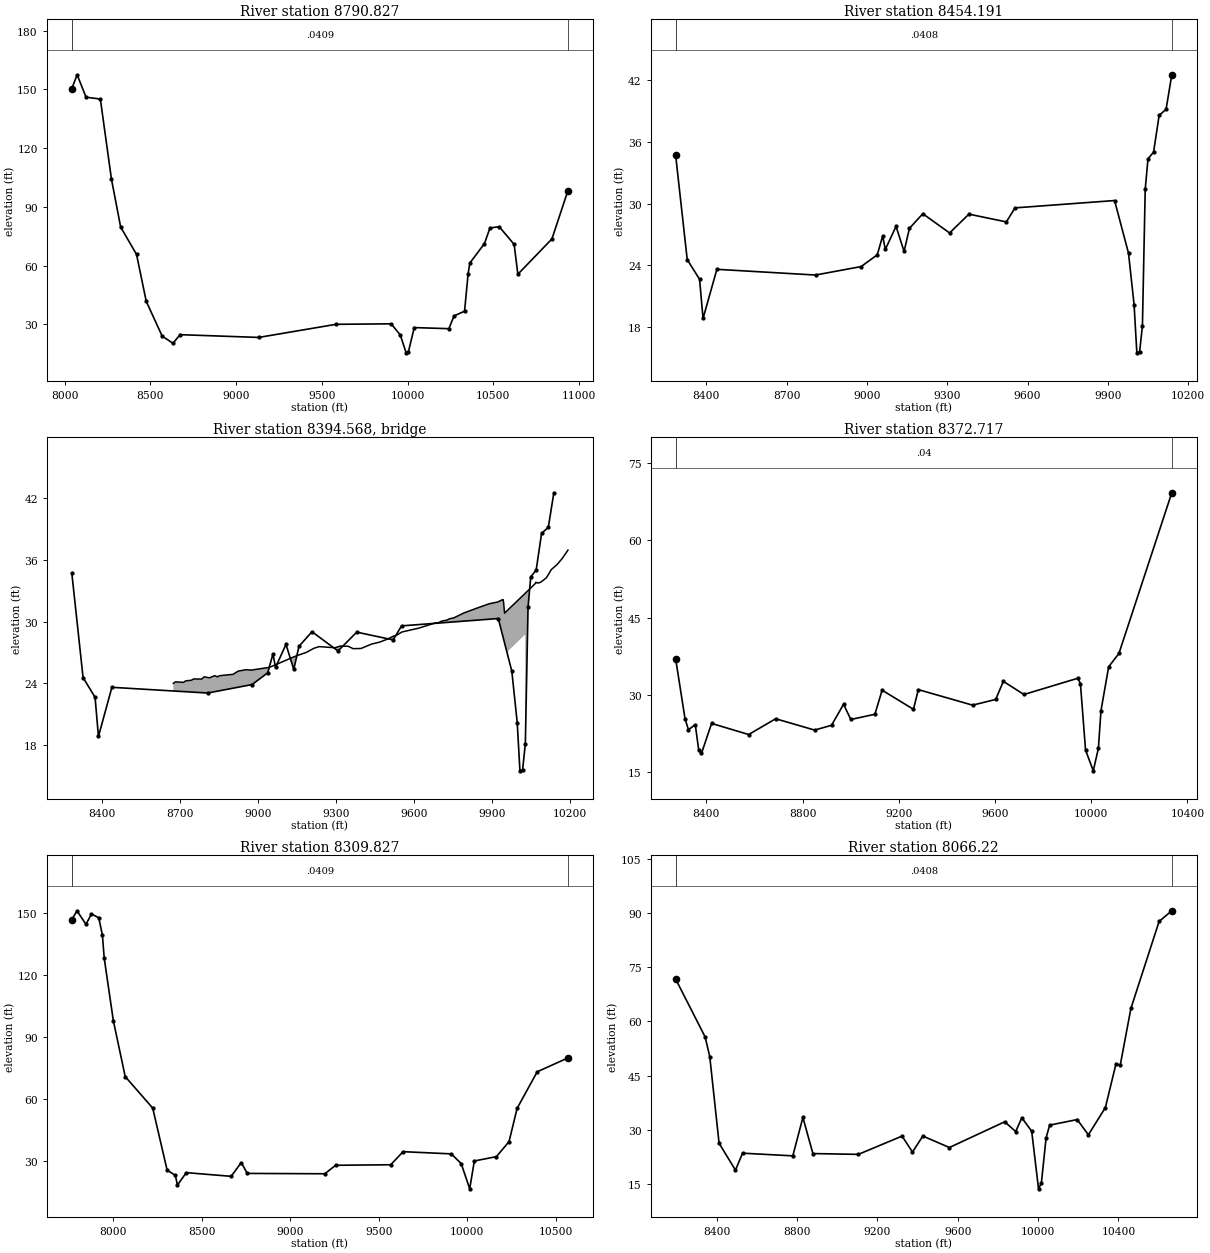
Type RM Length L Ch R = 1 ,8790.827,336.636400,336.636400,336.636400
XS GIS Cut Line= 6
677114.736319659876998.061558805677522.435824829876829.691625583
677803.908348769876486.492670983  677856.4066993875565.000969334
677921.063570188875138.147330561678165.214541498874550.998255622
#Sta/Elev= 30
8041.947150.34868073.282157.43518125.051145.98758208.507145.04848273.079104.2659
8326.88979.691038419.44765.722418476.08941.781418569.001 24.00478632.07820.34835
8673.24224.746179131.88223.339819582.81530.031779904.11730.291579957.27624.64962
9991.78115.4720610004.2415.7306710038.9528.3703410240.7727.8060110271.0134.31615
10332.3736.7431710353.1655.9602210363.6161.3750610448.4771.2585810480.4579.23374
10534.5479.8757110621.3970.8484810643.2655.6009510841.8173.6263910935.3398.34223
#Mann= 3 , 0 , 0
8041.947  0.0409       08041.947  0.0409       010935.33  0.0409       0
#XS Ineff= 2 , 0
       08686.789        10822.33       0
Bank Sta=8041.947,10935.33
Exp/Cntr=0.3,0.1

Type RM Length L Ch R = 1 ,8454.191,81.473100,81.473100,81.473100
XS GIS Cut Line= 6
677567.498843551876824.220535576677827.289508611876507.275924206
677855.866481751876130.579459846677863.660201699875850.005541578
677996.153440922875517.473490313 678120.85296011875109.602146164
#Sta/Elev= 30
8285.63534.729568329.01724.564058375.13722.648328388.06818.845718439.78823.61943
8808.04523.063648978.53323.886319038.705 25.02589058.76326.855589068.79225.54984
9108.81827.78652 9138.8325.358649158.83727.601849208.85729.013689308.89527.14683
9380.82428.976169520.76328.220099553.05729.583699924.87230.296459976.87225.18638
9997.67320.1946810008.0715.5102610018.4715.6273410028.8718.1423510039.2731.37998
10049.6734.3481310070.4734.9981910091.2738.5592710117.1839.1539210138.4942.50544
#Mann= 3 , 0 , 0
8285.635  0.0408       08285.635  0.0408       010138.49  0.0408       0
#XS Ineff= 2 , 0
       08450.411                       0
Bank Sta=8285.635,10138.49
Exp/Cntr=0.3,0.1

Type RM Length L Ch R = 3 ,8394.568,,,
BEGIN DESCRIPTION:
END DESCRIPTION:
Bridge Culvert--1,0,-1,-1, 0
Deck Dist Width WeirC Skew NumUp NumDn MinLoCord MaxHiCord MaxSubmerge Is_Ogee
17.770700,45.931700,2.6,0, 60, 60, , , 0.95, 0, 0,0,,
 8675.91 8684.10 8714.23 8724.27 8744.35 8754.39 8784.52 8794.56 8814.64 8834.73
 8844.77 8854.81 8905.02 8925.10 8955.22 8975.31 9045.60 9146.03 9186.24 9216.39
 9236.49 9296.80 9316.90 9347.06 9367.16 9397.32 9438.23 9469.56 9500.89 9521.77
 9532.22 9554.47 9618.50 9683.13 9694.47 9708.86 9727.03 9737.89 9753.68 9792.11
 9835.49 9889.70 9922.23 9941.46 9943.91 9945.69 9949.05 9962.88 9962.8810028.50
10028.5010068.5510069.0710079.2410089.4110109.7410128.7710150.0910170.1310192.69
   24.00   24.15   24.10   24.25   24.30   24.43   24.42   24.64   24.54   24.75
   24.64   24.75   24.88   25.19   25.33   25.29   25.56   26.65   27.00   27.41
   27.57   27.46   27.62   27.61   27.37   27.39   27.82   28.01   28.32   28.59
   28.65   28.99   29.36   29.87   29.89   30.06   30.14   30.28   30.36   30.83
   31.24   31.73   31.90   32.13   32.12   31.75   30.82   31.16   31.16   32.75
   32.75   33.73   33.81   33.74   33.85   34.25   35.05   35.52   36.11   36.94
 -976.00 -975.85 -975.90 -975.75 -975.70 -975.57 -975.58 -975.36 -975.46 -975.25
 -975.36 -975.25 -975.12 -974.81 -974.67 -974.71 -974.44 -973.35 -973.00 -972.59
 -972.43 -972.54 -972.38 -972.39 -972.63 -972.61 -972.18 -971.99 -971.68 -971.41
 -971.35 -971.01 -970.64 -970.13 -970.11 -969.94 -969.86 -969.72 -969.64 -969.17
 -968.76 -968.27 -968.10 -967.87 -967.88 -968.25 -969.18 -968.84   27.16   28.75
 -967.25 -966.27 -966.19 -966.26 -966.15 -965.75 -964.95 -964.48 -963.89 -963.06
 8675.91 8684.10 8714.23 8724.27 8744.35 8754.39 8784.52 8794.56 8814.64 8834.73
 8844.77 8854.81 8905.02 8925.10 8955.22 8975.31 9045.60 9146.03 9186.24 9216.39
 9236.49 9296.80 9316.90 9347.06 9367.16 9397.32 9438.23 9469.56 9500.89 9521.77
 9532.22 9554.47 9618.50 9683.13 9694.47 9708.86 9727.03 9737.89 9753.68 9792.11
 9835.49 9889.70 9922.23 9941.46 9943.91 9945.69 9949.05 9980.96 9980.9610046.58
10046.5810068.5510069.0710079.2410089.4110109.7410128.7710150.0910170.1310192.69
   24.00   24.15   24.10   24.25   24.30   24.43   24.42   24.64   24.54   24.75
   24.64   24.75   24.88   25.19   25.33   25.29   25.56   26.65   27.00   27.41
   27.57   27.46   27.62   27.61   27.37   27.39   27.82   28.01   28.32   28.59
   28.65   28.99   29.36   29.87   29.89   30.06   30.14   30.28   30.36   30.83
   31.24   31.73   31.90   32.13   32.12   31.75   30.82   31.60   31.60   33.19
   33.19   33.73   33.81   33.74   33.85   34.25   35.05   35.52   36.11   36.94
 -976.00 -975.85 -975.90 -975.75 -975.70 -975.57 -975.58 -975.36 -975.46 -975.25
 -975.36 -975.25 -975.12 -974.81 -974.67 -974.71 -974.44 -973.35 -973.00 -972.59
 -972.43 -972.54 -972.38 -972.39 -972.63 -972.61 -972.18 -971.99 -971.68 -971.41
 -971.35 -971.01 -970.64 -970.13 -970.11 -969.94 -969.86 -969.72 -969.64 -969.17
 -968.76 -968.27 -968.10 -967.87 -967.88 -968.25 -969.18 -968.40   27.60   29.19
 -966.81 -966.27 -966.19 -966.26 -966.15 -965.75 -964.95 -964.48 -963.89 -963.06
BR Coef=-1 , 0 , 0 ,, 0 ,,,0.8,0,1,0,
WSPro=,,,, 1 ,,,, 0 ,,,, 0 ,,,,-1 ,-1 ,-1 , 0 , 0 , 0 , 0 , 0
BC Design=,, 0 ,, 0 ,,,,,,

Type RM Length L Ch R = 1 ,8372.717,62.890500,62.890500,62.890500
XS GIS Cut Line= 6
677588.282096744876842.405882135677900.030894816876535.852897361
677910.422521412 876351.40152517677933.803681284875995.488314018
677954.586934477 875813.63484849678271.531545877874969.315187022
#Sta/Elev= 30
8271.82237.051438310.90925.407548325.17223.266338353.69724.227018367.95919.29919
8379.41718.652368421.49124.471688575.76422.318928687.96225.376968850.11923.17752
8920.24524.113438970.35228.182739000.41725.236059100.63326.248429130.69730.91548
9261.023 27.20719281.15331.028959506.80628.014329602.92629.119199634.96632.62476
9720.40630.082089944.68633.230169955.36632.186469976.72619.3170310008.7715.27896
10030.1319.6398910040.8126.9114510072.8535.4570710115.5738.0364210335.3569.19159
#Mann= 3 , 0 , 0
8271.822    0.04       08271.822    0.04       010335.35    0.04       0
#XS Ineff= 2 , 0
       08433.963                       0
Bank Sta=8271.822,10335.35
Exp/Cntr=0.3,0.1

Type RM Length L Ch R = 1 ,8309.827,243.607200,243.607200,243.607200
XS GIS Cut Line= 6
677126.272179863 877006.66101823677566.849823721876879.991226441
677895.690501679876592.989289454678081.428165522876155.481364807
678156.702512255875409.412282341678498.951155905 874830.16158717
#Sta/Elev= 30
7764.505146.71067793.773151.03167844.712144.46147875.584149.47457916.855147.6617
7937.491139.28877947.808128.05437999.39797.806258066.45370.755788221.90955.50437
8303.28725.486398349.89222.911738361.54318.244028411.90924.25009 8665.3522.46409
8722.29429.123568756.31423.875189194.72223.705819255.63427.810129567.05128.07236
9637.196 34.40569909.30333.337199965.63928.6226510013.5916.4090110039.7229.90235
 10164.631.9944310235.9239.2790210281.7255.4032610395.0873.0837710568.9679.80451
#Mann= 3 , 0 , 0
7764.505  0.0409       07764.505  0.0409       010568.96  0.0409       0
#XS Ineff= 2 , 0
       08432.674        10423.58       0
Bank Sta=7764.505,10568.96
Exp/Cntr=0.3,0.1

Type RM Length L Ch R = 1 , 8066.22,730.821700,730.821700,730.821700
XS GIS Cut Line= 6
677438.556760734876949.447975743677761.669405555876782.033145849
678023.973256718876465.668436834678271.630572898875633.126096816
678448.931784787875384.526052163678634.180425742874907.241205518
#Sta/Elev= 30
8194.075 71.6998 8341.1155.696868364.31750.221828410.704 26.29448492.29418.87508
8527.786 23.56038778.048 22.82248828.33933.445348878.08723.452219104.64523.23037
9322.37728.279059374.37523.873029425.86528.295349558.16825.124869833.80532.23516
 9888.6329.529849919.09633.347379968.28929.6335110002.38 13.705210016.5215.26274
   10040 27.788510057.8431.3143710195.0532.8482510250.7928.6431310335.4236.15325
10388.3148.2468710409.4747.8795410462.6763.5732110603.1587.6103510666.3190.55364
#Mann= 3 , 0 , 0
8194.075  0.0408       08194.075  0.0408       010666.31  0.0408       0
#XS Ineff= 2 , 0
       08556.101        10470.33       0
Bank Sta=8194.075,10666.31
Exp/Cntr=0.3,0.1

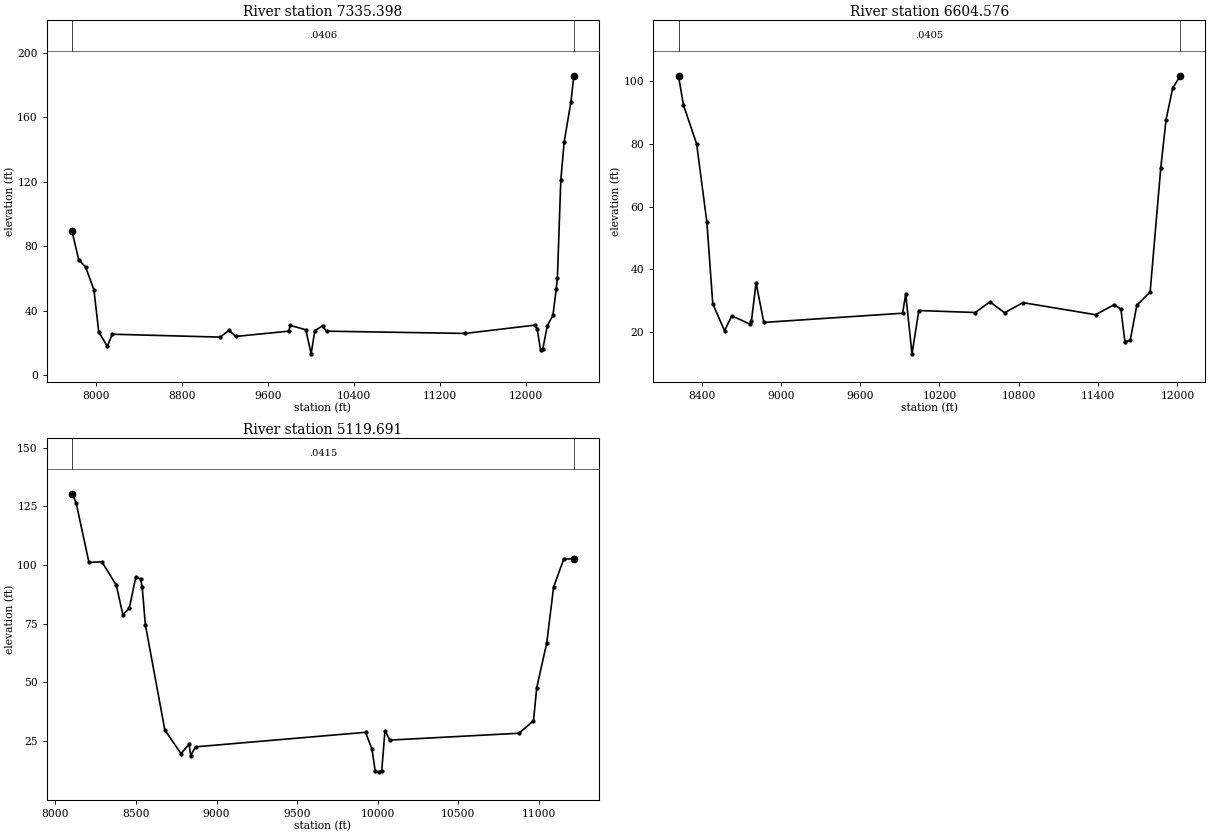
Type RM Length L Ch R = 1 ,7335.398,730.821700,730.821700,730.821700
XS GIS Cut Line= 6
677419.066004254876978.684110462677792.650613196876793.732418714
678195.413319462876414.108601201678901.531635186875503.814983435
679738.476816936874892.380967449681161.277781663874407.803520765
#Sta/Elev= 30
7775.36989.14545 7836.7371.754827902.55266.911917978.88552.946638023.96226.80654
8103.89317.865268149.56825.399159154.32223.610889238.70427.791519299.14424.01406
9795.38427.315939806.30530.925149952.342 28.146210002.3513.2280910036.3827.61984
10108.2230.5740510145.4427.2920611437.2125.8939112086.7231.0309212107.6728.65754
 12139.115.7066712160.0516.2452512201.9530.6257312254.3337.0384112285.7653.70394
12296.2460.5267512327.67120.840212359.09144.637612421.95 169.49512449.48 185.737
#Mann= 3 , 0 , 0
7775.369  0.0406       07775.369  0.0406       012449.48  0.0406       0
#XS Ineff= 2 , 0
       08175.079        10278.53       0
Bank Sta=7775.369,12449.48
Exp/Cntr=0.3,0.1

Type RM Length L Ch R = 1 ,6604.576,1484.885700,1484.885700,1484.885700
XS GIS Cut Line= 6
677411.649274677877010.734751731  677851.1750961 876799.04476427
 678775.04908746876225.680343403679644.395969031875780.072881972
680269.383835093875615.380133482680862.581580994875562.329928564
#Sta/Elev= 30
 8226.12101.63698263.13892.455058363.03380.021788440.72854.952558485.12628.94298
8573.92120.369478629.41825.132568765.54722.478478777.31623.357728812.624 35.6086
 8871.4723.012889921.33725.948379944.65432.020949992.39212.9803710043.9426.81163
 10471.226.1773110581.8429.5784510692.4826.1149210832.6529.3246611380.75  25.476
11522.6428.6883911572.8427.1978311602.9616.8411511643.1217.2888411693.3228.53753
11793.7232.6900511874.0472.31144 11914.287.75064 11964.497.8309612022.21101.7721
#Mann= 3 , 0 , 0
 8226.12  0.0405       0 8226.12  0.0405       012022.21  0.0405       0
#XS Ineff= 2 , 0
       08656.315        11062.21       0
Bank Sta=8226.12,12022.21
Exp/Cntr=0.3,0.1

Type RM Length L Ch R = 1 ,5119.691,0.000000,0.000000,0.000000
XS GIS Cut Line= 6
677140.286688834877050.133506939 677563.42673263877068.801450044
 679211.32011947876901.733917743679674.401137233 876899.55982846
680032.912255019876865.787041992 680234.33720544876798.017899796
#Sta/Elev= 30
8103.009130.41888127.747126.69078207.824101.17768287.902101.4269 8377.9991.44805
8418.02978.894728458.06881.597628498.10794.737128528.14294.169688538.19490.76849
8558.296 74.51778678.91129.750278779.42419.65278 8829.6823.722668839.73118.82012
8869.88522.561379925.26828.750219965.473 21.43419985.575 12.121410005.6811.90612
10025.7812.4434710045.8829.4617610076.0425.4374210877.61 28.355510968.0133.65944
10988.0947.7580411050.4966.93687 11092.790.60655   11156 102.62411218.61102.6837
#Mann= 3 , 0 , 0
8103.009  0.0415       08103.009  0.0415       011218.61  0.0415       0
#XS Ineff= 2 , 0
       08900.772                       0
Bank Sta=8103.009,11218.61
Exp/Cntr=0.3,0.1